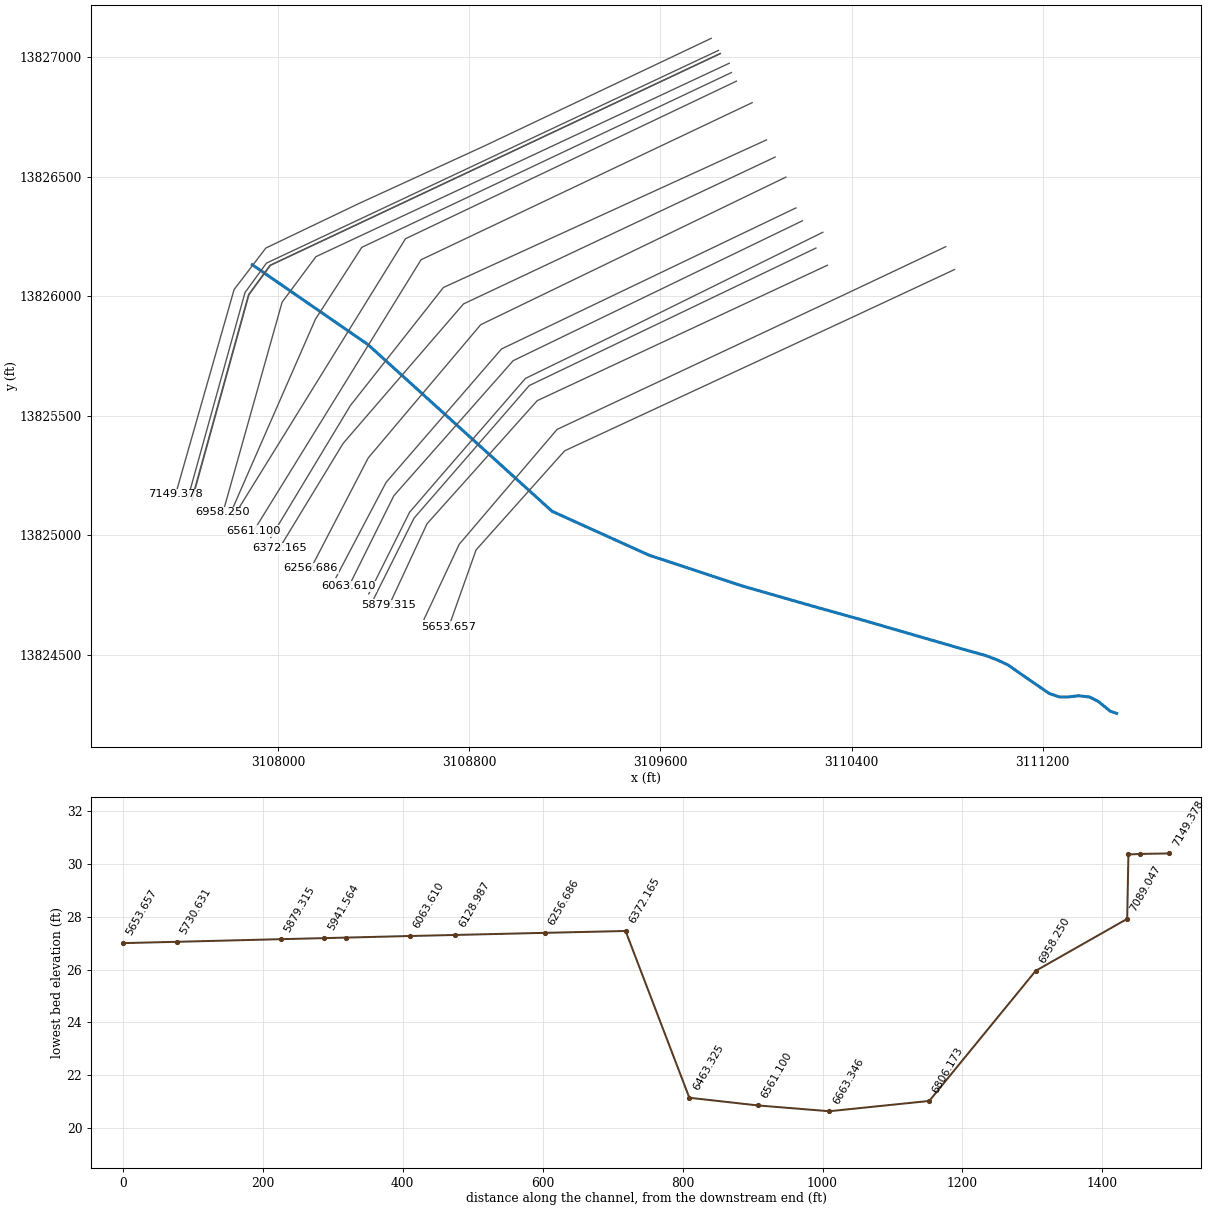
--- D109-00-00.prj (project) ---

Proj Title=D109-00-00
Current Plan=p01
Default Exp/Contr=.3,.1
English Units
Geom File=g01
Flow File=f01
Plan File=p01
Y Axis Title=Elevation
X Axis Title(PF)=Main Channel Distance
X Axis Title(XS)=Station
BEGIN DESCRIPTION:
HCFCD MODEL SUMMARY METADATA
The purpose of this summary is to document the high points of hydrologic and hydraulic models filed within the HCFCD Model and Map Management (M3) system.  The document includes references to the project that prompted the creation or update of the model.
DESCRIPTION OF PROJECT:
The following model was the hydraulic model which represented the effective condition of Harris County’s watersheds.
PURPOSE OF PROJECT:
Development of effective models to support the National Flood Insurance Program.
HCFCD Watershed Unit ID: D
M3 Study Identifier: 2007_Effective_D
Engineer: HCFCD
Project Name: Effective FEMA Study for watershed Brays Bayou (D)
Study Completion Date: 6/18/2007
FEMA Case Number: [No Data]
FEMA Approval Date: [No Date in Database]
Vertical Datum: NAVD 1988
Datum Note: 2001 ADJ
HYDRAULICS
HCFCD Unit No.:  D109-00-00
Hydraulic Program Name: HEC-RAS
Hydraulic Program Version: 3.0.1
Steady Hydraulic Model: Yes
Unsteady Hydraulic Model: No
Update 1:
The effective FEMA hydraulic model for unit number D109-00-00 has been updated by FEMA LOMR 15-06-1456P with an effective date of 09/25/2015.
END DESCRIPTION:
DSS File=dss
DSS Export Rating Curves= 0
DSS Export Rating Curve Sorted= 0
DSS Export Volume Flow Curves= 0
DXF OffsetX= 0
DXF OffsetY= 0
DXF ScaleX= 1
DXF ScaleY= 10

--- D109-00-00.p01 (plan) ---

Plan Title=Effective Multi-Profile 2015
Version=Version 3.0.1  Mar 2001
Short Identifier=Eff+LOMR MP
Geom File=g01
Flow File=f01
Subcritical Flow
K Sum by GR= 0
Std Step Tol= 0.01
Critical Tol= 0.01
Num of Std Step Trials= 20
Max Error Tol= 0.3
Flow Tol Ratio= 0.001
Split Flow NTrial= 30
Split Flow Tol= 0.02
Split Flow Ratio= 0.02
Log Output Level= 0
Friction Slope Method= 1
Unsteady Friction Slope Method= 2
Parabolic Critical Depth
Global Vel Dist= 0 , 0 , 0
Global Log Level= 0
CheckData=True
Encroach Param=-1 ,0,0, 0
BEGIN DESCRIPTION:
FEMA Effective Multi-Profile June 2007 + LOMR 15-06-1456P
END DESCRIPTION:
Computation Interval=1HOUR
Output Interval=1HOUR
Run HTab= 0
Run UNet= 0
Run PostProcess= 0
UNET Theta= 1
UNET ZTol= 0.02
UNET ZSATol= 0.05
UNET MxIter= 20
UNET MaxInSteps= 0
UNET DtIC= 0
UNET DtMin= 0
UNET MaxCRTS= 20
UNET WFStab= 2
UNET SFStab= 1
UNET WFX= 1
UNET SFX= 1
UNET Convert EG Bridges= 0
UNET Use Existing IB Tables=-1
Instantaneous Interval=1HOUR
Write IC File= 0
IC Time=0
Write Velocity= 0
Write Detailed= 0

--- D109-00-00.f01 (steady flow) ---

Flow Title=Effective Multi-Profile 2015
Version=Version 3.0.1  Mar 2001
Number of Profiles= 4
Profile Names=10PCT_10yr, 2PCT_50yr, 1PCT_100yr, 0.2PCT_500yr
River Rch & RM=D109-00-00,D109-00-00_0030 ,7149.378
     744    1100    1294    1846
River Rch & RM=D109-00-00,D109-00-00_0030 ,6256.686
     928    1358    1590    2247
River Rch & RM=D109-00-00,D109-00-00_0030 ,5367.458
    1111    1616    1886    2645
River Rch & RM=D109-00-00,D109-00-00_0030 ,4441.798
    1302    1884    2193    3060
River Rch & RM=D109-00-00,D109-00-00_0030 ,3366.170
    1827    2610    3032    4224
River Rch & RM=D109-00-00,D109-00-00_0030 ,3117.041
    1948    2778    3226    4493
River Rch & RM=D109-00-00,D109-00-00_0001 ,2954.708
    2028    2887    3353    4669
River Rch & RM=D109-00-00,D109-00-00_0001 ,2254.613
    2027    2887    3292    3646
River Rch & RM=D109-00-00,D109-00-00_0001 ,1581.152
    2112    3010    3432    3844
River Rch & RM=D109-00-00,D109-00-00_0001 ,976.751
    2189    3120    3558    4022
River Rch & RM=D109-00-00,D109-00-00_0001 ,321.835
    2385    3406    3889    5360
River Rch & RM=D109-01-99,D109-01-99_0001 ,5320.206
     410     580     670     900
River Rch & RM=D109-01-99,D109-01-99_0002 ,4062.978
     410     500     530     590
River Rch & RM=D109-01-99,D109-01-99_0002 ,3833.110
     510     650     700     820
River Rch & RM=D109-01-99,D109-01-99_0002 ,3603.866
     610     790     870    1050
River Rch & RM=D109-01-99,D109-01-99_0002 ,3377.598
     710     940    1040    1280
River Rch & RM=D109-01-99,D109-01-99_0002 ,3039.407
     730     970    1070    1340
River Rch & RM=D109-01-99,D109-01-99_0002 ,2288.246
     750    1000    1110    1400
River Rch & RM=D109-01-99,D109-01-99_0002 ,1747.652
     770    1020    1150    1450
River Rch & RM=D109-01-99,D109-01-99_0003 ,1115.599
     780    1040    1170    1490
River Rch & RM=D109-01-99,D109-01-99_0003 ,754.537
     790    1060    1190    1520
River Rch & RM=D109-01-99,D109-01-99_0003 ,304.962
     800    1070    1210    1550
River Rch & RM=D109-03-99,D109-03-99_0001 ,4975.566
   .0001      82     140     310
River Rch & RM=D109-03-99,D109-03-99_0001 ,4758.453
      27     110     180     370
River Rch & RM=D109-03-99,D109-03-99_0001 ,3847.611
      55     140     220     420
River Rch & RM=D109-03-99,D109-03-99_0001 ,3106.822
      82     170     260     480
River Rch & RM=D109-03-99,D109-03-99_0001 ,2268.024
     110     200     300     540
River Rch & RM=D109-03-99,D109-03-99_0001 ,1332.440
     130     220     320     570
River Rch & RM=D109-03-99,D109-03-99_0001 ,1091.193
     140     240     340     600
River Rch & RM=D109-03-99,D109-03-99_0001 ,765.138
     150     250     360     630
River Rch & RM=D109-03-99,D109-03-99_0001 ,481.309
     170     270     380     660
River Rch & RM=D109-03-99,D109-03-99_0001 ,258.765
     180     290     400     680
River Rch & RM=D109-02-99,D109-02-99_0001 ,3078.014
   .0001   .0001     280    1490
River Rch & RM=D109-02-99,D109-02-99_0001 ,2971.038
      26      37     300    1540
River Rch & RM=D109-02-99,D109-02-99_0001 ,2308.779
      52      73     330    1590
River Rch & RM=D109-02-99,D109-02-99_0001 ,1498.599
      78     110     350    1640
River Rch & RM=D109-02-99,D109-02-99_0001 ,709.549
     100     150     380    1680
Boundary for River Rch & Prof#=D109-01-99,D109-01-99_0001 , 1
Up Type= 0
Dn Type= 0
Boundary for River Rch & Prof#=D109-01-99,D109-01-99_0001 , 2
Up Type= 0
Dn Type= 0
Boundary for River Rch & Prof#=D109-01-99,D109-01-99_0001 , 3
Up Type= 0
Dn Type= 0
Boundary for River Rch & Prof#=D109-01-99,D109-01-99_0001 , 4
Up Type= 0
Dn Type= 0
Boundary for River Rch & Prof#=D109-01-99,D109-01-99_0002 , 1
Up Type= 0
Dn Type= 0
Boundary for River Rch & Prof#=D109-01-99,D109-01-99_0002 , 2
Up Type= 0
Dn Type= 0
Boundary for River Rch & Prof#=D109-01-99,D109-01-99_0002 , 3
Up Type= 0
Dn Type= 0
Boundary for River Rch & Prof#=D109-01-99,D109-01-99_0002 , 4
Up Type= 0
Dn Type= 0
Boundary for River Rch & Prof#=D109-01-99,D109-01-99_0003 , 1
Up Type= 0
Dn Type= 0
Boundary for River Rch & Prof#=D109-01-99,D109-01-99_0003 , 2
Up Type= 0
Dn Type= 0
Boundary for River Rch & Prof#=D109-01-99,D109-01-99_0003 , 3
Up Type= 0
Dn Type= 0
Boundary for River Rch & Prof#=D109-01-99,D109-01-99_0003 , 4
Up Type= 0
Dn Type= 0
Boundary for River Rch & Prof#=D109-00-00,D109-00-00_0030 , 1
Up Type= 0
Dn Type= 0
Boundary for River Rch & Prof#=D109-00-00,D109-00-00_0030 , 2
Up Type= 0
Dn Type= 0
Boundary for River Rch & Prof#=D109-00-00,D109-00-00_0030 , 3
Up Type= 0
Dn Type= 0
Boundary for River Rch & Prof#=D109-00-00,D109-00-00_0030 , 4
Up Type= 0
Dn Type= 0
Boundary for River Rch & Prof#=D109-00-00,D109-00-00_0001 , 1
Up Type= 0
Dn Type= 3
Dn Slope=.000018
Boundary for River Rch & Prof#=D109-00-00,D109-00-00_0001 , 2
Up Type= 0
Dn Type= 3
Dn Slope=.000019
Boundary for River Rch & Prof#=D109-00-00,D109-00-00_0001 , 3
Up Type= 0
Dn Type= 3
Dn Slope=.000019
Boundary for River Rch & Prof#=D109-00-00,D109-00-00_0001 , 4
Up Type= 0
Dn Type= 3
Dn Slope=.000029
Boundary for River Rch & Prof#=D109-03-99,D109-03-99_0001 , 1
Up Type= 0
Dn Type= 3
Dn Slope=.000012
Boundary for River Rch & Prof#=D109-03-99,D109-03-99_0001 , 2
Up Type= 0
Dn Type= 3
Dn Slope=.000004
Boundary for River Rch & Prof#=D109-03-99,D109-03-99_0001 , 3
Up Type= 0
Dn Type= 3
Dn Slope=.000004
Boundary for River Rch & Prof#=D109-03-99,D109-03-99_0001 , 4
Up Type= 0
Dn Type= 3
Dn Slope=.000004
Boundary for River Rch & Prof#=D109-02-99,D109-02-99_0001 , 1
Up Type= 0
Dn Type= 3
Dn Slope=.000379
Boundary for River Rch & Prof#=D109-02-99,D109-02-99_0001 , 2
Up Type= 0
Dn Type= 3
Dn Slope=.000379
Boundary for River Rch & Prof#=D109-02-99,D109-02-99_0001 , 3
Up Type= 0
Dn Type= 3
Dn Slope=.000379
Boundary for River Rch & Prof#=D109-02-99,D109-02-99_0001 , 4
Up Type= 0
Dn Type= 3
Dn Slope=.000379
DSS Import GetInterval= 0
DSS Import GetPeak= 0
DSS Import FillOption= 0

--- D109-00-00.g01 (geometry) ---

Geom Title=D109-00-00 June 2007
Program Version=4.00

Junct Name=1
Junct Desc=, 0 , 0 ,-1
Up River,Reach=D109-00-00      ,D109-00-00_0030
Up River,Reach=D109-01-99      ,D109-01-99_0003
Dn River,Reach=D109-00-00      ,D109-00-00_0001
Junc L&A=0,0
Junc L&A=49.09,0

Junct Name=4
Junct Desc=, 0 , 0 ,-1
Up River,Reach=D109-01-99      ,D109-01-99_0002
Dn River,Reach=D109-01-99      ,D109-01-99_0003
Dn River,Reach=D109-02-99      ,D109-02-99_0001
Junc L&A=0,0
Junc L&A=0,0

Junct Name=5
Junct Desc=, 0 , 0 ,-1
Up River,Reach=D109-01-99      ,D109-01-99_0001
Dn River,Reach=D109-01-99      ,D109-01-99_0002
Dn River,Reach=D109-03-99      ,D109-03-99_0001
Junc L&A=0,0
Junc L&A=0,0

River Reach=D109-00-00      ,D109-00-00_0030
Reach XY= 30
     3107891.688    13826132.049     3107927.789    13826107.131
     3107942.367    13826097.067     3107977.073    13826073.112
     3108375.542    13825798.062     3109146.282    13825100.114
       3109376.3       13824996.     3109385.641    13824991.773
     3109386.626    13824991.326     3109407.279    13824981.979
     3109527.474    13824927.575     3109553.062    13824915.992
     3109567.073    13824911.374      3109723.28    13824859.876
     3109942.714    13824787.536     3110244.587    13824700.965
     3110449.234    13824643.784     3110864.547    13824523.403
     3110960.852    13824496.318     3111009.004    13824478.261
     3111054.147    13824457.194     3111101.863    13824423.792
     3111227.095    13824337.417     3111269.921    13824322.856
     3111305.895    13824322.856     3111349.578    13824327.995
     3111395.831    13824322.856     3111432.661    13824304.012
     3111483.196    13824262.899     3111509.049    13824254.283

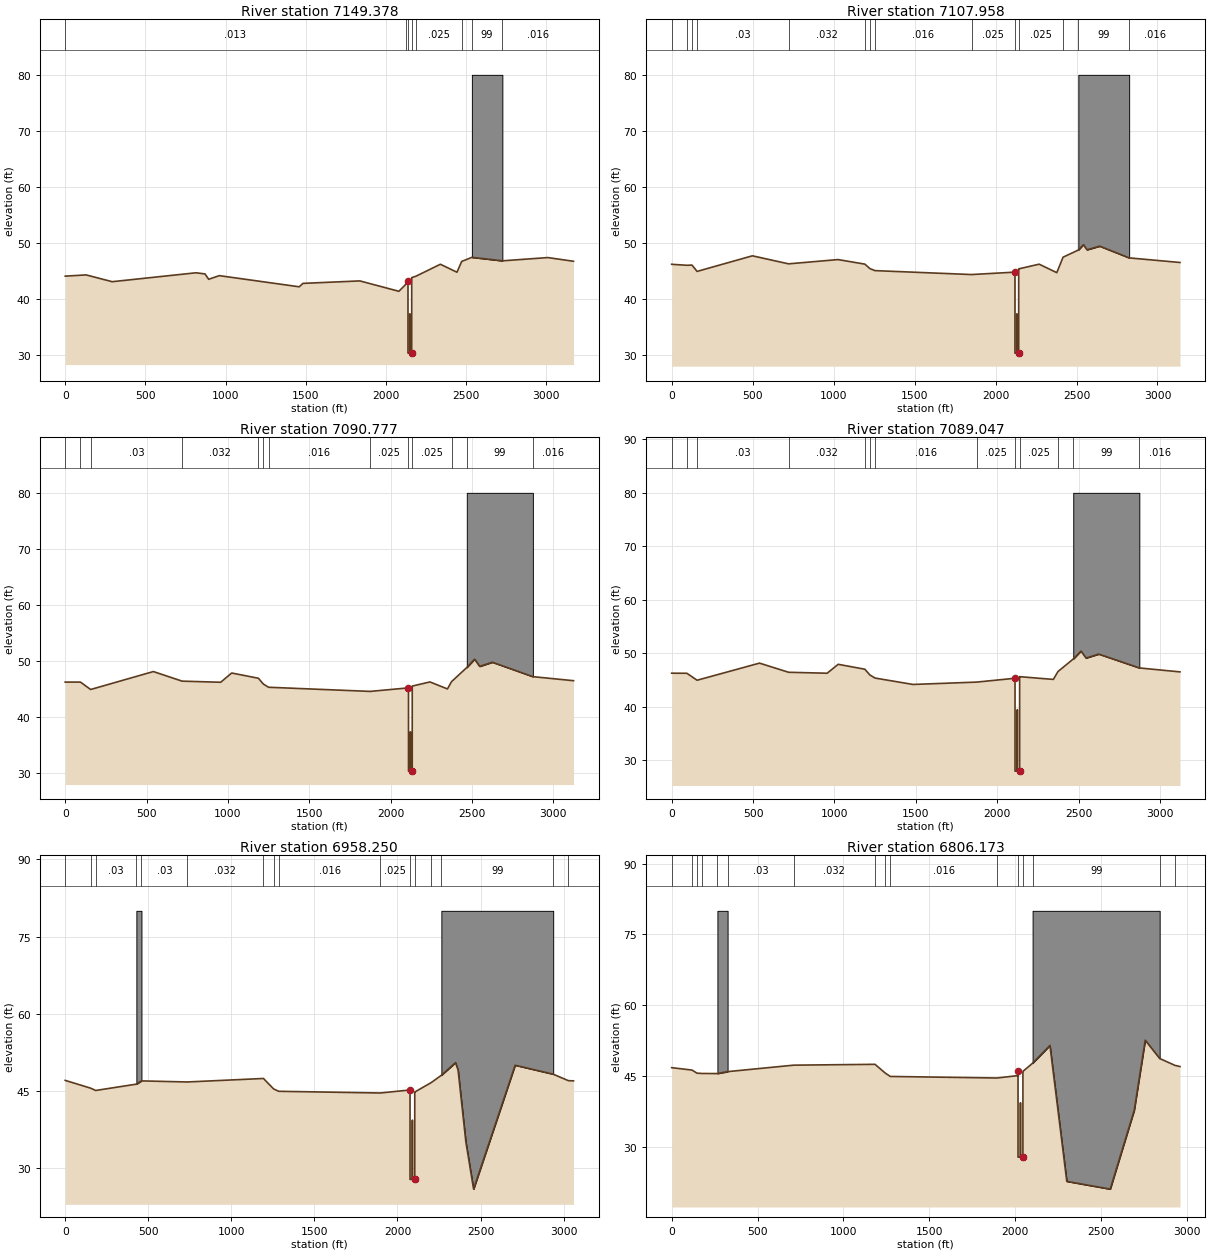
Type RM Length L Ch R = 1 ,7149.378,58.03,41.42,47.71
XS GIS Cut Line= 6
     3109812.523    13827079.458     3108863.918    13826629.323
     3108333.726     13826386.13     3107948.544    13826201.847
     3107815.618    13826028.137     3107570.914    13825171.673
#Sta/Elev= 30
       0   44.12  130.56   44.34  293.03   43.13  815.81   44.72  872.11   44.51
  894.63   43.56  960.71   44.21 1459.57   42.22 1482.19   42.83 1837.44   43.27
 2080.72   41.42 2123.74   42.66  2137.5    43.2  2137.6    43.2  2137.6    30.4
  2148.6    30.4  2148.6    37.4  2149.6    37.4  2149.6    30.4  2160.6    30.4
  2160.6   43.86  2160.7   43.86 2187.13   44.11 2339.46   46.24 2442.86   44.82
 2472.41   46.74 2535.81   47.47 2725.99   46.85 3009.87   47.43 3169.76   46.77
#Mann= 8 ,-1 , 0
       0    .013       0 2123.74     .03       0  2137.5    .011       0
  2160.7     .03       0 2187.13    .025       0 2472.41    .016       0
 2535.81      99       0 2725.99    .016       0
#Block Obstruct= 1 ,-1
 2535.81 2725.99      80
#XS Lid=4
  2137.6    43.2    37.4  2149.1   43.69    37.4 2153.16   43.74    37.4
  2160.6   43.86    37.4
Bank Sta=2137.6,2160.6
XS Rating Curve= 0 ,0
Exp/Cntr=0.3,0.1

Type RM Length L Ch R = 1 ,7107.958,14.73,17.18,16.53
XS GIS Cut Line= 4
     3109842.948    13827029.124     3107951.295    13826138.758
     3107861.359    13826015.846      3107621.53    13825152.461
#Sta/Elev= 30
       0   46.22   94.17   46.04  125.56   46.08  156.95   44.95  498.36   47.73
  721.99    46.3 1027.22   47.06 1192.86   46.25 1224.25   45.45 1255.64   45.09
 1852.07   44.39 2119.85   44.82 2119.95   44.82 2119.95   30.38 2130.95   30.38
 2130.95   37.38 2131.95   37.38 2131.95   30.38 2142.95   30.38 2142.95    45.4
 2143.05    45.4  2269.2   46.24 2378.18   44.73  2417.1   47.49 2511.28   48.76
 2542.56   49.72 2564.99    48.8 2642.83   49.45 2825.19   47.36  3139.1   46.54
#Mann= 14 ,-1 , 0
       0    .016       0   94.17     .03       0  125.56    .013       0
  156.95     .03       0  721.99    .032       0 1192.86     .03       0
 1224.25    .013       0 1255.64    .016       0 1852.07    .025       0
 2119.85    .011       0 2143.05    .025       0  2417.1    .016       0
 2511.28      99       0 2825.19    .016       0
#Block Obstruct= 1 ,-1
 2511.28 2825.19      80
#XS Lid=4
 2119.95   44.82   37.38 2125.58    45.1   37.38 2129.97   45.15   37.38
 2142.95    45.4   37.38
Bank Sta=2119.95,2142.95
XS Rating Curve= 0 ,0
Exp/Cntr=0.3,0.1

Type RM Length L Ch R = 1 ,7090.777,1.05,1.73,1.94
XS GIS Cut Line= 4
     3109850.288    13827016.284     3107965.885    13826129.614
     3107875.949    13826006.701     3107638.503    13825149.741
#Sta/Elev= 30
       0   46.24   93.72   46.24  156.21   44.92  541.77   48.12  718.55   46.41
   955.5   46.21 1023.14   47.86 1187.17   46.93 1218.41   45.88 1249.65   45.32
 1874.48   44.58 2109.69   45.21 2109.79   45.21 2109.79   30.36 2120.79   30.36
 2120.79   37.36 2121.79   37.36 2121.79   30.36 2132.79   30.36 2132.79   45.53
 2132.89   45.53 2241.64   46.27 2349.29   45.02 2374.34   46.32 2468.07   48.84
 2516.18   50.33 2547.31   49.04 2625.14   49.78 2874.21   47.21 3124.14   46.49
#Mann= 13 ,-1 , 0
       0    .016       0   93.72    .013       0  156.21     .03       0
  718.55    .032       0 1187.17     .03       0 1218.41    .013       0
 1249.65    .016       0 1874.48    .025       0 2109.69    .011       0
 2132.89    .025       0 2374.34    .016       0 2468.07      99       0
 2874.21    .016       0
#Block Obstruct= 1 ,-1
 2468.07 2874.21      80
#XS Lid=5
 2109.79   45.21   37.36    2115   45.37   37.36 2124.71    45.4   37.36
 2127.14   45.42   37.36 2132.79   45.53   37.36
Bank Sta=2109.79,2132.79
XS Rating Curve= 0 ,0
Exp/Cntr=0.3,0.1

Type RM Length L Ch R = 1 ,7089.047,51.81,130.8,141.75
XS GIS Cut Line= 4
     3109850.666    13827015.303     3107967.823    13826129.334
     3107877.887    13826006.422     3107640.441    13825149.462
#Sta/Elev= 30
       0   46.25   93.67   46.23  156.12   44.93  539.45   48.13  718.16   46.42
  955.04   46.24 1022.68   47.91 1186.52   46.99 1217.75   45.91 1248.97   45.34
 1482.14   44.14 1873.45   44.58  2108.9    45.3    2109    45.3    2109   27.92
 2122.75   27.92 2122.75   39.42 2123.75   39.42 2123.75   27.92  2137.5   27.92
  2137.5    45.6  2137.6    45.6  2344.4   45.08 2373.04   46.56 2466.72    48.9
 2514.18   50.39 2545.31   49.08 2623.14   49.82 2872.63   47.23 3122.42   46.49
#Mann= 13 ,-1 , 0
       0    .016       0   93.67    .013       0  156.12     .03       0
  718.16    .032       0 1186.52     .03       0 1217.75    .013       0
 1248.97    .016       0 1873.45    .025       0  2108.9    .011       0
  2137.6    .025       0 2373.04    .016       0 2466.72      99       0
 2872.63    .016       0
#Block Obstruct= 1 ,-1
 2466.72 2872.63      80
#XS Lid=5
    2109    45.3   39.42 2114.48   45.42   39.42 2122.65   45.44   39.42
 2128.71   45.48   39.42  2137.5    45.6   39.42
Bank Sta=2109,2137.5
XS Rating Curve= 0 ,0
Exp/Cntr=0.3,0.1

Type RM Length L Ch R = 1 ,6958.250,39.77,152.08,150.85
XS GIS Cut Line= 4
     3109887.916    13826975.162     3108158.148    13826165.739
     3108016.526    13825975.224     3107769.367    13825096.594
#Sta/Elev= 30
       0   47.07     153   45.56  183.59   45.11  428.39   46.34  458.99   46.97
  734.38   46.76 1193.36   47.44 1254.56   45.41 1285.16   44.95 1897.14   44.62
 2075.56   45.21 2075.66   45.21 2075.66   27.84 2089.41   27.84 2089.41   39.34
 2090.41   39.34 2090.41   27.84 2104.16   27.84 2104.16   44.81 2104.26   44.81
 2203.13   46.64 2264.33   48.06 2349.32   50.52 2364.91   49.08 2411.65   35.16
  2458.4   25.95 2708.31   50.01  2937.5   48.27  3029.3   47.01  3059.9   46.98
#Mann= 16 ,-1 , 0
       0    .016       0     153    .013       0  183.59     .03       0
  428.39      99       0  458.99     .03       0  734.38    .032       0
 1193.36     .03       0 1254.56    .013       0 1285.16    .016       0
 1897.14    .025       0 2075.56    .011       0 2104.26    .025       0
 2203.13     .03       0 2264.33      99       0  2937.5    .016       0
  3029.3     .03       0
#Block Obstruct= 2 ,-1
  428.39  458.99      80 2264.33  2937.5      80
#XS Lid=5
 2075.66   45.21   39.34 2083.95   45.06   39.34  2090.6   44.95   39.34
 2100.16   44.84   39.34 2104.16   44.81   39.34
Bank Sta=2075.66,2104.16
XS Rating Curve= 0 ,0
Exp/Cntr=0.3,0.1

Type RM Length L Ch R = 1 ,6806.173,41.95,142.83,143.35
XS GIS Cut Line= 4
     3109896.909     13826936.19     3108350.011    13826204.711
     3108156.049    13825903.986     3107798.404    13825086.508
#Sta/Elev= 30
       0   46.76  118.45   46.25  148.06   45.59  177.68   45.53  266.51   45.51
  325.74   45.92   710.7   47.29 1184.51   47.47 1243.73   45.63 1273.34    44.9
 1895.21   44.57 2017.58   45.08 2017.68   46.08 2017.68   27.81 2031.43   27.81
 2031.43   39.31 2032.43   39.31 2032.43   27.81 2046.18   27.81 2046.18   45.97
 2046.28   45.97  2102.5   47.71 2203.63   51.47 2301.87   22.66 2554.82   21.02
 2694.81   37.74 2758.76   52.58 2842.82   48.71 2931.65   47.25 2961.27      47
#Mann= 16 ,-1 , 0
       0    .016       0  118.45     .03       0  148.06    .013       0
  177.68     .03       0  266.51      99       0  325.74     .03       0
   710.7    .032       0 1184.51     .03       0 1243.73    .013       0
 1273.34    .016       0 1895.21    .025       0 2017.58    .011       0
 2046.28     .03       0  2102.5      99       0 2842.82    .016       0
 2931.65     .03       0
#Block Obstruct= 2 ,-1
  266.51  325.74      80  2102.5 2842.82      80
#XS Lid=6
 2017.68   46.08   39.31 2019.43   46.11   39.31 2020.93   46.12   39.31
 2025.58   45.93   39.31 2037.28   45.68   39.31 2046.18   45.97   39.31
Bank Sta=2017.68,2046.18
XS Rating Curve= 0 ,0
Exp/Cntr=0.3,0.1

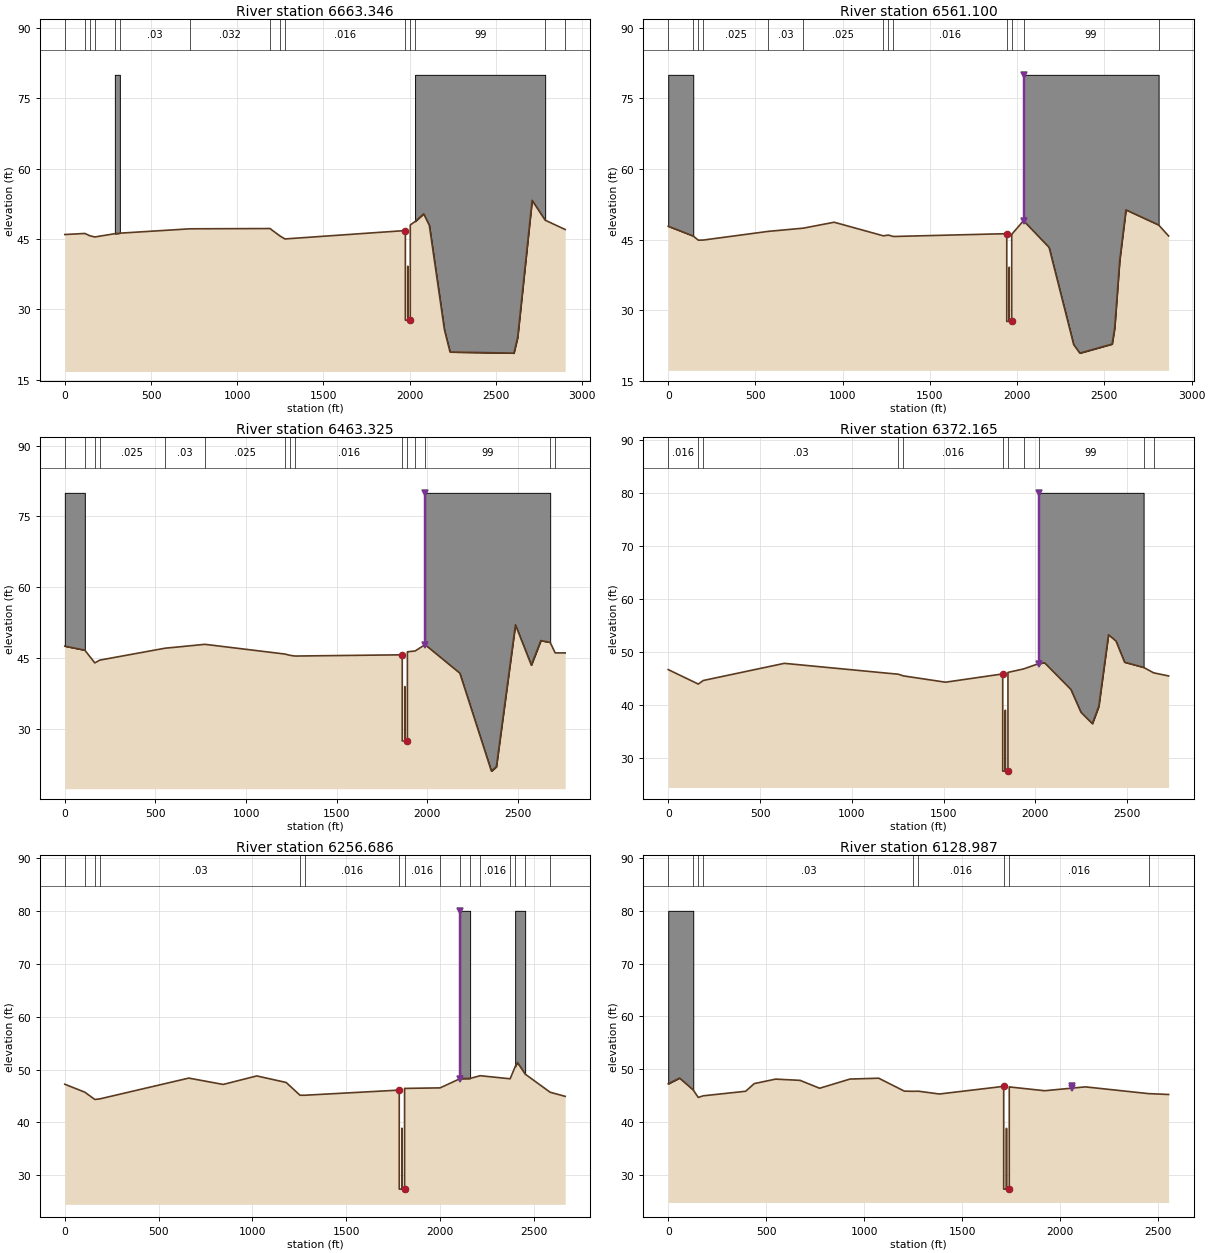
Type RM Length L Ch R = 1 ,6663.346,109.29,102.25,102.59
XS GIS Cut Line= 3
     3109917.894    13826900.216     3108532.881    13826240.686
     3107813.393    13825077.514
#Sta/Elev= 30
       0   45.93  116.07   46.16  145.09   45.67   174.1   45.41  290.17   46.11
  319.19   46.22  725.43   47.15 1189.71   47.21 1247.75   45.62 1276.77   44.99
 1974.79   46.78 1974.89   46.78 1974.89   27.65 1988.64   27.65 1988.64   39.15
 1989.64   39.15 1989.64   27.65 2003.39   27.65 2003.39   47.98 2003.49   47.98
 2031.22   48.71 2081.34   50.35 2114.03   47.86 2201.21   25.66 2234.16   20.86
  2604.4   20.63  2626.2   23.99 2709.95   53.22 2785.67   48.99 2901.74      47
#Mann= 15 ,-1 , 0
       0    .016       0  116.07     .03       0  145.09    .013       0
   174.1     .03       0  290.17      99       0  319.19     .03       0
  725.43    .032       0 1189.71     .03       0 1247.75    .013       0
 1276.77    .016       0 1974.79    .011       0 2003.49    .016       0
 2031.22      99       0 2785.67    .016       0 2901.74     .03       0
#Block Obstruct= 2 ,-1
  290.17  319.19      80 2031.22 2785.67      80
#XS Lid=6
 1974.89   46.78   39.15 1977.54   46.94   39.15 1984.62   47.16   39.15
 2001.84   47.86   39.15 2004.44   47.96   39.15 2003.39   47.98   39.15
Bank Sta=1974.89,2003.39
XS Rating Curve= 0 ,0
Exp/Cntr=0.3,0.1

Type RM Length L Ch R = 1 ,6561.100,164.02,97.78,92.94
XS GIS Cut Line= 3
     3109983.847     13826810.28     3108598.036    13826152.738
     3107897.334    13825017.557
#Sta/Elev= 30
       0   47.81   143.4   45.74  172.08   44.86  200.75   44.88  573.58   46.73
  774.34   47.41  951.09   48.67 1233.21   45.78 1261.88   45.94 1290.56   45.64
 1940.14   46.24 1940.24   46.24 1940.24   27.59 1953.99   27.59 1953.99   39.09
 1954.99   39.09 1954.99   27.59 1968.74   27.59 1968.74    46.1 1968.84    46.1
 2036.22      49 2182.72   43.33 2323.74   22.67 2359.07   20.85 2544.34   22.78
 2559.04   26.23  2587.6   40.51 2623.41    51.3 2810.56   48.09 2867.92   45.75
#Mann= 13 ,-1 , 0
       0      99       0   143.4     .03       0  172.08    .013       0
  200.75    .025       0  573.58     .03       0  774.34    .025       0
 1233.21     .03       0 1261.88    .013       0 1290.56    .016       0
 1940.14    .011       0 1968.84     .03       0 2036.22      99       0
 2810.56    .016       0
Levee=0,,,-1,2036.22,80,,
#Block Obstruct= 2 ,-1
       0   143.4      80 2036.22 2810.56      80
#XS Lid=6
 1940.24   46.24   39.09 1944.27    46.1   39.09 1950.18   45.99   39.09
 1953.57   45.92   39.09 1959.33   45.76   39.09 1968.74    46.1   39.09
Bank Sta=1940.24,1968.74
XS Rating Curve= 0 ,0
Exp/Cntr=0.3,0.1

Type RM Length L Ch R = 1 ,6463.325,82.49,91.16,89.64
XS GIS Cut Line= 4
     3110043.804    13826654.391     3108691.768    13826036.831
     3108302.045    13825542.183     3107969.282    13824990.576
#Sta/Elev= 30
       0   47.57  110.41   46.72  165.62   44.03  193.22   44.62  552.07   47.13
  772.89   47.96 1214.55    45.9 1242.15   45.63 1269.75   45.48  1861.3   45.74
  1861.4   45.74  1861.4   27.52 1875.15   27.52 1875.15   39.02 1876.15   39.02
 1876.15   27.52  1889.9   27.52  1889.9   46.38    1890   46.38 1932.23   46.55
 1987.44   47.89 2178.99   41.87 2353.23   21.14 2380.73   22.07 2485.83   52.09
 2573.42   43.56 2625.98   48.75 2677.53   48.36 2705.13   46.15 2760.34   46.14
#Mann= 15 ,-1 , 0
       0      99       0  110.41     .03       0  165.62    .013       0
  193.22    .025       0  552.07     .03       0  772.89    .025       0
 1214.55     .03       0 1242.15    .013       0 1269.75    .016       0
  1861.3    .011       0    1890    .016       0 1932.23     .03       0
 1987.44      99       0 2677.53     .03       0 2705.13    .016       0
Levee=0,,,-1,1987.44,80,,
#Block Obstruct= 2 ,-1
       0  110.41      80 1987.44 2677.53      80
#XS Lid=5
  1861.4   45.74   39.02 1869.87    45.9   39.02 1873.34   46.01   39.02
 1877.75   46.14   39.02  1889.9   46.38   39.02
Bank Sta=1861.4,1889.9
XS Rating Curve= 0 ,0
Exp/Cntr=0.3,0.1

Type RM Length L Ch R = 1 ,6372.165,96.9,115.48,115.99
XS GIS Cut Line= 4
     3110079.779    13826582.442     3108775.708     13825967.88
     3108271.731    13825383.996     3108005.257    13824945.608
#Sta/Elev= 30
       0   46.63  163.56    43.9  190.82   44.57  632.68   47.81 1253.94   45.75
  1281.2   45.44 1510.66   44.25 1822.08   45.81 1822.18   45.81 1822.18   27.46
 1835.93   27.46 1835.93   38.96 1836.93   38.96 1836.93   27.46 1850.68   27.46
 1850.68    46.1 1850.78    46.1 1935.43   46.75 2017.21   47.74 2050.24   47.92
 2193.28   42.89 2248.34   38.58  2310.5   36.43 2345.61    39.7 2398.27   53.21
 2438.95   52.04 2486.04   48.02 2589.66   47.05 2644.18   46.02 2725.96   45.43
#Mann= 11 ,-1 , 0
       0    .016       0  163.56    .013       0  190.82     .03       0
 1253.94    .013       0  1281.2    .016       0 1822.08    .011       0
 1850.78    .016       0 1935.43     .03       0 2017.21      99       0
 2589.66     .03       0 2644.18    .016       0
Levee=0,,,-1,2017.21,80,,
#Block Obstruct= 1 ,-1
 2017.21 2589.66      80
#XS Lid=5
 1822.18   45.81   38.96 1825.97   45.84   38.96 1837.54   45.84   38.96
 1848.93   46.07   38.96 1850.68    46.1   38.96
Bank Sta=1822.18,1850.68
XS Rating Curve= 0 ,0
Exp/Cntr=0.3,0.1

Type RM Length L Ch R = 1 ,6256.686,133.75,127.7,127.3
XS GIS Cut Line= 4
     3110124.747    13826498.502     3108847.657    13825880.942
     3108376.992    13825323.339     3108137.163    13824861.668
#Sta/Elev= 30
       0   47.22  106.74   45.72  160.11   44.34   186.8   44.45  661.11   48.38
  844.39   47.18 1023.74   48.79 1180.69   47.55  1254.2   45.14 1280.88   45.14
 1783.39   46.11 1783.49   46.11 1783.49   27.39 1797.24   27.39 1797.24   38.89
 1798.24   38.89 1798.24   27.39 1811.99   27.39 1811.99   46.43 1812.09   46.43
 2001.38   46.53 2108.12   48.28 2161.49   48.32 2214.86   48.83 2374.97   48.25
 2401.66   50.53 2413.82   51.33 2455.03   49.14 2588.45    45.7 2668.51   44.93
#Mann= 16 ,-1 , 0
       0    .016       0  106.74     .03       0  160.11    .013       0
   186.8     .03       0  1254.2    .013       0 1280.88    .016       0
 1783.39    .011       0 1812.09    .016       0 2001.38     .03       0
 2108.12      99       0 2161.49     .03       0 2214.86    .016       0
 2374.97     .03       0 2401.66      99       0 2455.03     .03       0
 2588.45    .016       0
Levee=0,,,-1,2108.12,80,,
#Block Obstruct= 2 ,-1
 2108.12 2161.49      80 2401.66 2455.03      80
#XS Lid=6
 1783.49   46.11   38.89 1783.78   46.13   38.89  1785.4   46.12   38.89
 1804.19   46.52   38.89 1805.03   46.52   38.89 1811.99   46.43   38.89
Bank Sta=1783.49,1811.99
XS Rating Curve= 0 ,0
Exp/Cntr=0.3,0.1

Type RM Length L Ch R = 1 ,6128.987,60.92,65.38,64.97
XS GIS Cut Line= 4
     3110166.717    13826369.594       3108934.7    13825779.347
     3108451.939    13825221.412     3108242.088    13824822.696
#Sta/Elev= 30
       0   47.25   57.82   48.34  127.72   46.08  153.27   44.67  178.81   44.98
  395.34   45.84  439.12   47.29  548.32   48.14  673.23    47.9  773.07   46.41
  927.85   48.15 1074.45   48.31 1205.47   45.86 1251.69   45.83 1277.24   45.85
 1384.26   45.32 1712.48   46.77 1712.58   46.77 1712.58   27.31 1726.33   27.31
 1726.33   38.81 1727.33   38.81 1727.33   27.31 1741.08   27.31 1741.08   46.66
 1741.18   46.66 1921.82   45.94 2129.46   46.67  2452.3   45.39 2554.48   45.23
#Mann= 9 ,-1 , 0
       0      99       0  127.72     .03       0  153.27    .013       0
  178.81     .03       0 1251.69    .013       0 1277.24    .016       0
 1712.48    .011       0 1741.18    .016       0  2452.3     .03       0
Levee=0,,,-1,2060.07,46.78,,
#Block Obstruct= 1 ,-1
       0  127.72      80
#XS Lid=7
 1712.58   46.77   38.81 1717.81   46.73   38.81 1721.47   46.77   38.81
 1730.41   46.75   38.81 1735.38   46.79   38.81 1740.74   46.68   38.81
 1741.08   46.66   38.81
Bank Sta=1712.58,1741.08
XS Rating Curve= 0 ,0
Exp/Cntr=0.3,0.1

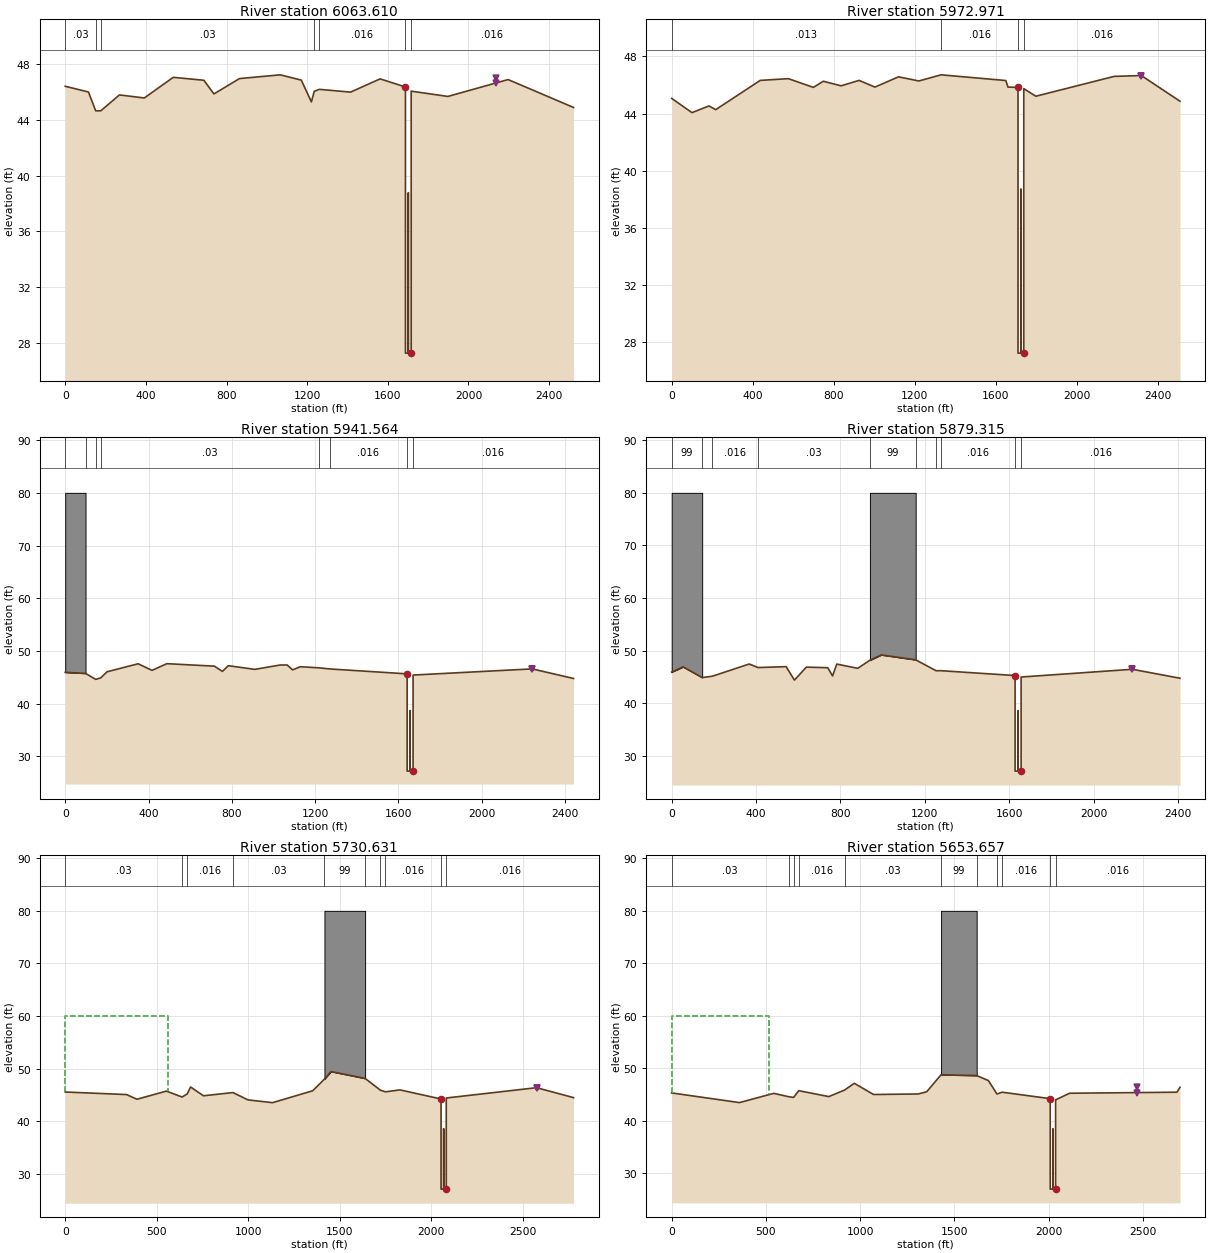
Type RM Length L Ch R = 1 ,6063.610,82.25,90.64,91.08
XS GIS Cut Line= 4
     3110193.698    13826315.632      3108983.67    13825730.378
     3108484.199    13825165.085      3108296.05    13824786.721
#Sta/Elev= 30
       0    46.4  115.27   45.99  151.26   44.64  176.47   44.64  268.89   45.78
  392.42   45.56  535.94   47.04  687.74   46.83  737.73   45.85   864.1   46.95
 1066.25   47.22 1170.95   46.84 1220.94   45.28 1235.31   46.04 1260.52   46.18
  1415.1   45.98 1561.76   46.93 1687.35   46.35 1687.45   46.35 1687.45   27.27
  1701.2   27.27  1701.2   38.77  1702.2   38.77  1702.2   27.27 1715.95   27.27
 1715.95   46.05 1716.05   46.05 1897.59   45.67 2196.75   46.88 2521.03   44.88
#Mann= 7 ,-1 , 0
       0     .03       0  151.26    .013       0  176.47     .03       0
 1235.31    .013       0 1260.52    .016       0 1687.35    .011       0
 1716.05    .016       0
Levee=0,,,-1,2136.15,46.96,,
#XS Lid=3
 1687.45   46.35   38.77 1697.43   46.12   38.77 1715.95   46.05   38.77
Bank Sta=1687.45,1715.95
XS Rating Curve= 0 ,0
Exp/Cntr=0.3,0.1

Type RM Length L Ch R = 1 ,5972.971,44.59,31.41,31.39
XS GIS Cut Line= 6
     3110279.535    13826267.767     3109458.819    13825862.387
     3109034.949    13825656.142     3108680.775    13825247.917
     3108549.915    13825095.722     3108379.229     13824754.35
#Sta/Elev= 30
       0   45.06  100.34   44.06  183.99   44.53  217.45   44.27  437.22   46.32
  576.44   46.44  699.62   45.83  748.61   46.26  836.46   45.94  925.39   46.32
  1003.5   45.85 1119.84   46.57 1220.36   46.28 1330.08   46.71 1649.68   46.31
 1660.31   45.85 1709.74   45.83 1709.84   45.83 1709.84   27.21 1723.59   27.21
 1723.59   38.71 1724.59   38.71 1724.59   27.21 1738.34   27.21 1738.34   45.74
 1738.44   45.74 1797.86   45.21 2184.16    46.6 2318.76   46.66 2509.59   44.86
#Mann= 4 ,-1 , 0
       0    .013       0 1330.08    .016       0 1709.74    .011       0
 1738.44    .016       0
Levee=0,,,-1,2318.1,46.66,,
#XS Lid=5
 1709.84   45.83   38.71 1718.42   45.71   38.71 1724.11   45.69   38.71
 1730.67   45.71   38.71 1738.34   45.74   38.71
Bank Sta=1709.84,1738.34
XS Rating Curve= 0 ,0
Exp/Cntr=0.3,0.1

Type RM Length L Ch R = 1 ,5941.564,83.81,62.25,61.6
XS GIS Cut Line= 4
     3110250.657    13826201.713     3109051.002    13825626.318
     3108568.855    13825071.519     3108400.975    13824735.758
#Sta/Elev= 30
       0   45.94   97.64   45.74  146.46    44.6  170.86   44.89  200.84   46.04
  350.18   47.56  417.11   46.31  488.12   47.58  716.56   47.11  754.94   46.11
   783.1    47.2  910.39    46.5 1032.64   47.33 1065.91   47.33 1092.24    46.4
 1128.59      47 1220.46   46.79 1269.28   46.58 1641.82   45.65 1641.92   45.65
 1641.92   27.19 1655.67   27.19 1655.67   38.69 1656.67   38.69 1656.67   27.19
 1670.42   27.19 1670.42   45.42 1670.52   45.42 2242.67   46.59 2440.93   44.77
#Mann= 8 ,-1 , 0
       0      99       0   97.64     .03       0  146.46    .013       0
  170.86     .03       0 1220.46    .013       0 1269.28    .016       0
 1641.82    .011       0 1670.52    .016       0
Levee=0,,,-1,2242.67,46.59,,
#Block Obstruct= 1 ,-1
       0   97.64      80
#XS Lid=6
 1641.92   45.65   38.69 1652.83   45.54   38.69 1658.08   45.52   38.69
 1662.65   45.53   38.69 1670.19   45.44   38.69 1670.42   45.42   38.69
Bank Sta=1641.92,1670.42
XS Rating Curve= 0 ,0
Exp/Cntr=0.3,0.1

Type RM Length L Ch R = 1 ,5879.315,141.88,148.68,149.94
XS GIS Cut Line= 4
     3110298.623    13826129.765     3109084.488    13825563.168
     3108622.817    13825047.536      3108463.93    13824705.779
#Sta/Elev= 30
       0   45.96   54.13   46.95  144.53   44.92  192.71   45.17  367.32   47.49
   409.5   46.82  542.33   46.99  581.76   44.44  638.19    46.9  739.76   46.79
  762.33   45.23  782.46   47.48  881.78   46.67  939.44   48.21  992.98   49.22
 1156.24   48.29 1252.59   46.22 1276.68   46.22 1627.27    45.3 1627.37    45.3
 1627.37   27.15 1641.12   27.15 1641.12   38.65 1642.12   38.65 1642.12   27.15
 1655.87   27.15 1655.87   45.02 1655.97   45.02 2182.93   46.49 2408.83   44.79
#Mann= 10 ,-1 , 0
       0      99       0  144.53     .03       0  192.71    .016       0
   409.5     .03       0  939.44      99       0 1156.24     .03       0
 1252.59    .013       0 1276.68    .016       0 1627.27    .011       0
 1655.97    .016       0
Levee=0,,,-1,2182.93,46.49,,
#Block Obstruct= 2 ,-1
       0  144.53      80  939.44 1156.24      80
#XS Lid=5
 1627.37    45.3   38.65 1639.54   45.08   38.65  1646.1   45.02   38.65
 1648.13      45   38.65 1655.87   45.02   38.65
Bank Sta=1627.37,1655.87
XS Rating Curve= 0 ,0
Exp/Cntr=0.3,0.1

Type RM Length L Ch R = 1 ,5730.631,99.22,76.97,75.83
XS GIS Cut Line= 5
     3110794.234    13826207.584     3110369.311     13826006.63
     3109167.304    13825442.683     3108757.792     13824961.96
      3108610.43    13824647.822
#Sta/Elev= 30
       0   45.53  335.42   45.04  391.75   44.15   552.6    45.7  638.54   44.57
   666.3   45.16  684.88   46.48  754.94   44.81  916.16   45.42  998.02   44.03
 1132.51    43.5 1351.49   45.76 1415.89   47.98 1451.77   49.42 1637.99   48.11
 1721.28   45.88 1749.04   45.56 1828.15   45.93 2052.57    44.2 2052.67    44.2
 2052.67   27.05 2066.42   27.05 2066.42   38.55 2067.42   38.55 2067.42   27.05
 2081.17   27.05 2081.17   44.39 2081.27   44.39 2574.26   46.35 2776.26   44.46
#Mann= 10 ,-1 , 0
       0     .03       0  638.54    .013       0   666.3    .016       0
  916.16     .03       0 1415.89      99       0 1637.99     .03       0
 1721.28    .013       0 1749.04    .016       0 2052.57    .011       0
 2081.27    .016       0
Levee=0,,,-1,2574.26,46.35,,
#XS Ineff= 1 ,-1
       0  561.04      60
Permanent Ineff=
       F
#Block Obstruct= 1 ,-1
 1415.89 1637.99      80
#XS Lid=5
 2052.67    44.2   38.55 2061.36   44.19   38.55  2072.7   44.24   38.55
 2077.82   44.35   38.55 2081.17   44.39   38.55
Bank Sta=2052.67,2081.17
XS Rating Curve= 0 ,0
Exp/Cntr=0.3,0.1

Type RM Length L Ch R = 1 ,5653.657,52.19,56.37,55.25
XS GIS Cut Line= 5
     3110830.916    13826111.948     3110421.542    13825920.718
     3109199.055    13825353.135     3108828.247    13824938.245
     3108714.152    13824616.705
#Sta/Elev= 30
       0   45.32  359.69   43.48  542.21   45.24  620.38    44.6  647.35   44.47
  674.32   45.75  833.63   44.62  917.08   45.86  969.16   47.15 1071.42   45.02
 1307.98   45.12 1353.16   45.54 1429.56   48.78 1618.37   48.63 1680.69   47.67
 1726.26   45.11 1753.24   45.46 2008.62   44.23 2008.72   44.23 2008.72      27
 2022.47      27 2022.47    38.5 2023.47    38.5 2023.47      27 2037.22      27
 2037.22      44 2037.32      44  2111.5   45.26 2681.08   45.46 2697.29    46.4
#Mann= 11 ,-1 , 0
       0     .03       0  620.38    .013       0  647.35     .03       0
  674.32    .016       0  917.08     .03       0 1429.56      99       0
 1618.37     .03       0 1726.26    .013       0 1753.24    .016       0
 2008.62    .011       0 2037.32    .016       0
Levee=0,,,-1,2469.51,46.51,,
#XS Ineff= 1 ,-1
       0  517.29      60
Permanent Ineff=
       F
#Block Obstruct= 1 ,-1
 1429.56 1618.37      80
#XS Lid=6
 2008.72   44.23    38.5 2010.91   44.28    38.5 2017.08   44.17    38.5
 2023.98   43.99    38.5  2027.7   43.85    38.5 2037.22      44    38.5
Bank Sta=2008.72,2037.22
XS Rating Curve= 0 ,0
Exp/Cntr=0.3,0.1