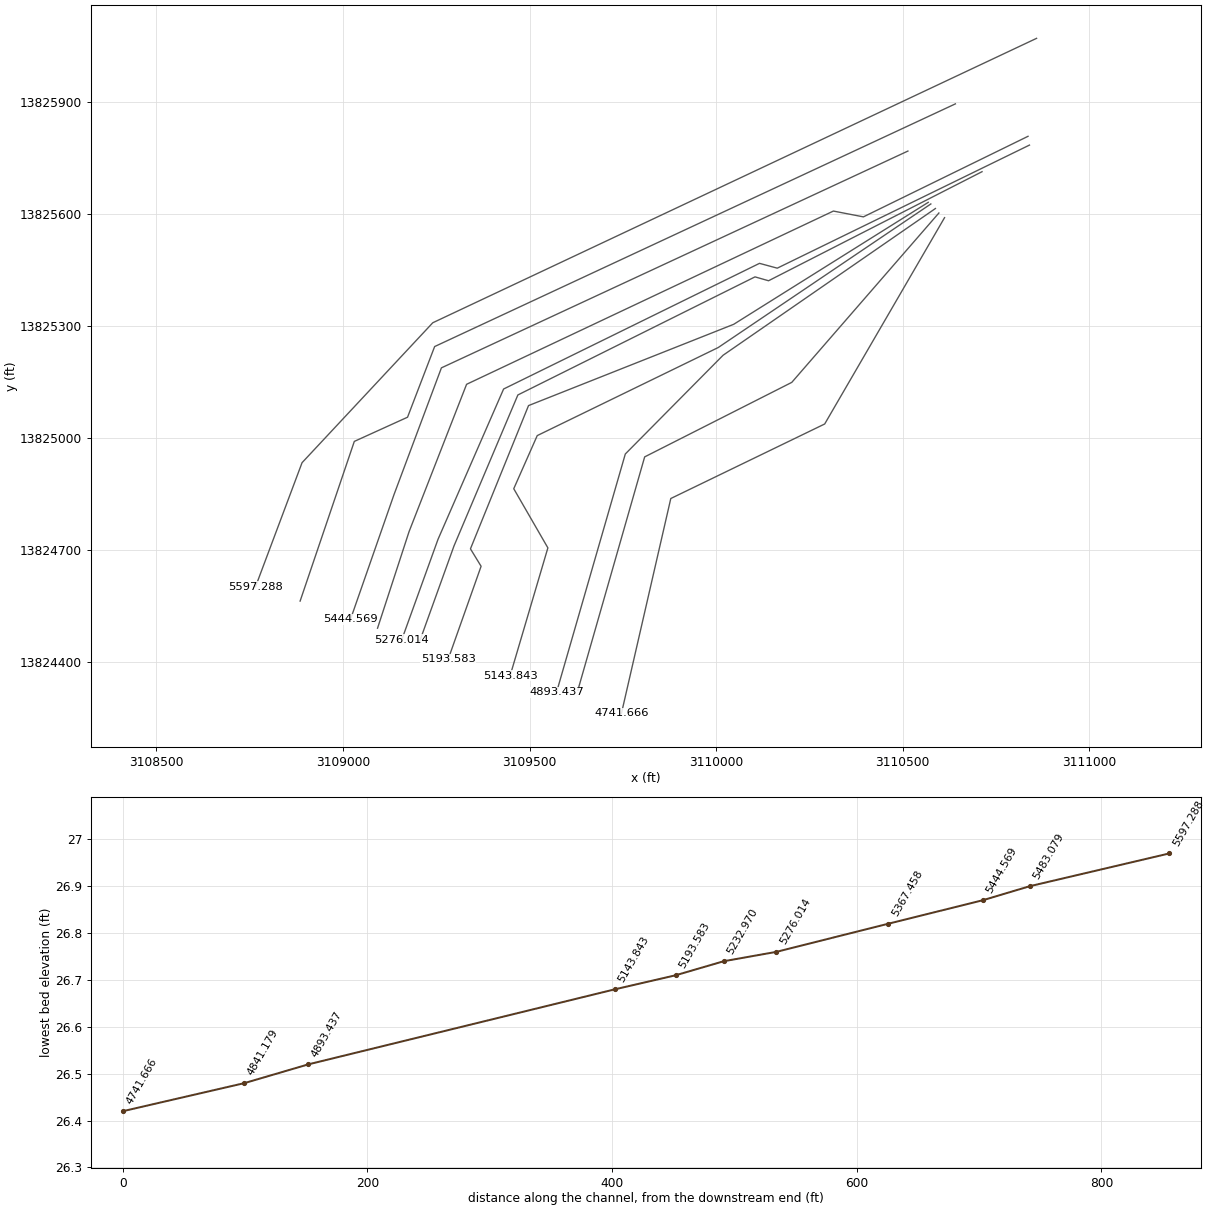
HEC-RAS study D109-00-00.prj: D109-00-00

--- D109-00-00.g01 (geometry) --- (continued)

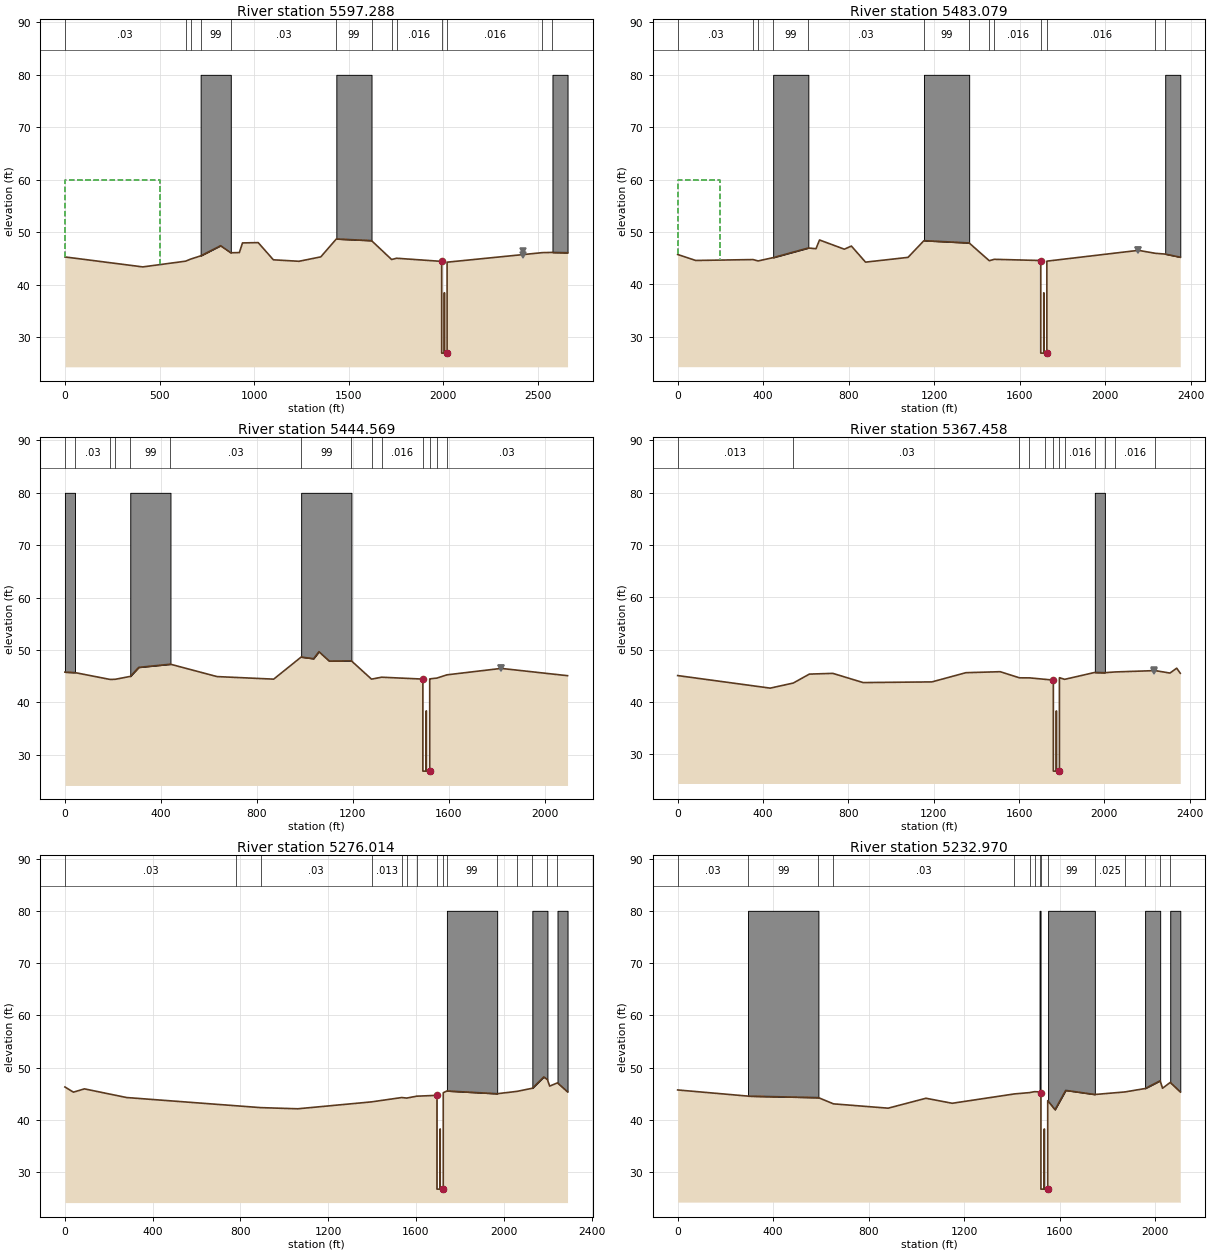
Type RM Length L Ch R = 1 ,5597.288,64.58,114.21,102.68
XS GIS Cut Line= 5
     3110858.428    13826070.025     3110439.082    13825872.455
     3109240.758    13825308.018     3108890.481    13824933.059
     3108766.014    13824601.147
#Sta/Elev= 30
       0    45.3   411.3    43.4  637.38   44.49  663.94   44.88  717.05    45.5
  822.58   47.44   876.4   46.09  921.75   46.13  938.33   47.97 1021.23   48.03
 1101.49   44.75 1236.78   44.47  1351.9   45.31 1434.11   48.72 1620.01   48.41
 1726.24   44.81  1752.8   45.05 1990.75   44.45 1990.85   44.45 1990.85   26.97
  2004.6   26.97  2004.6   38.47  2005.6   38.47  2005.6   26.97 2019.35   26.97
 2019.35    44.3 2019.45    44.3 2522.97   46.12 2576.08   46.16 2655.76    46.1
#Mann= 13 ,-1 , 0
       0     .03       0  637.38    .013       0  663.94     .03       0
  717.05      99       0   876.4     .03       0 1434.11      99       0
 1620.01     .03       0 1726.24    .013       0  1752.8    .016       0
 1990.75    .011       0 2019.45    .016       0 2522.97     .03       0
 2576.08      99       0
Levee=0,,,-1,2422.88,46.52,,
#XS Ineff= 1 ,-1
       0  503.06      60
Permanent Ineff=
       F
#Block Obstruct= 3 ,-1
  717.05   876.4      80 1434.11 1620.01      80 2576.08 2655.76      80
#XS Lid=3
 1990.85   44.45   38.47 2017.14    44.3   38.47 2019.35    44.3   38.47
Bank Sta=1990.85,2019.35
XS Rating Curve= 0 ,0
Exp/Cntr=0.3,0.1

Type RM Length L Ch R = 1 ,5483.079,60.66,38.51,149.03
XS GIS Cut Line= 5
     3110640.954    13825894.474      3109245.73    13825244.227
     3109173.124    13825054.933     3109030.506    13824990.106
     3108885.294    13824562.251
#Sta/Elev= 30
       0   45.72   84.27   44.58  352.58   44.75  376.09   44.49   446.6   45.12
  611.14   46.96  646.94   46.82  663.49   48.49  779.33   46.73  812.43   47.33
  878.62   44.26 1077.21   45.17 1151.76   48.36 1363.31   47.92 1457.33   44.53
 1480.84    44.8 1698.02   44.57 1698.12   44.57 1698.12    26.9 1711.87    26.9
 1711.87    38.4 1712.87    38.4 1712.87    26.9 1726.62    26.9 1726.62   44.45
 1726.72   44.45 2155.01   46.51 2233.01   45.95 2280.02    45.8 2350.54    45.2
#Mann= 13 ,-1 , 0
       0     .03       0  352.58    .013       0  376.09     .03       0
   446.6      99       0  611.14     .03       0 1151.76      99       0
 1363.31     .03       0 1457.33    .013       0 1480.84    .016       0
 1698.02    .011       0 1726.72    .016       0 2233.01     .03       0
 2280.02      99       0
Levee=0,,,-1,2155.01,46.51,,
#XS Ineff= 1 ,-1
       0  199.34      60
Permanent Ineff=
       F
#Block Obstruct= 3 ,-1
   446.6  611.14      80 1151.76 1363.31      80 2280.02 2350.54      80
#XS Lid=7
 1698.12   44.57    38.4 1702.34    44.5    38.4 1704.83    44.5    38.4
 1706.54    44.5    38.4 1710.08   44.47    38.4 1724.72    44.5    38.4
 1726.62   44.45    38.4
Bank Sta=1698.12,1726.62
XS Rating Curve= 0 ,0
Exp/Cntr=0.3,0.1

Type RM Length L Ch R = 1 ,5444.569,89.89,77.11,72.09
XS GIS Cut Line= 4
     3110513.738    13825768.025     3109263.882    13825187.179
     3109136.822    13824847.488     3109020.134    13824512.983
#Sta/Elev= 30
       0   45.77    41.9   45.68  188.57   44.37  209.52    44.4  272.37   44.95
  307.84   46.68  439.99   47.28  633.79   44.92  870.22   44.43  984.74   48.65
 1036.34   48.33 1058.93   49.67 1101.79   47.88 1194.25   47.92 1278.06   44.43
 1319.96    44.8 1492.09   44.44 1492.19   44.44 1492.19   26.87 1505.94   26.87
 1505.94   38.37 1506.94   38.37 1506.94   26.87 1520.69   26.87 1520.69   44.48
 1520.79   44.48 1550.43   44.63 1592.34   45.25 1818.73   46.48 2095.18   45.09
#Mann= 14 ,-1 , 0
       0      99       0    41.9     .03       0  188.57    .013       0
  209.52     .03       0  272.37      99       0  439.99     .03       0
  984.74      99       0 1194.25     .03       0 1278.06    .013       0
 1319.96    .016       0 1492.09    .011       0 1520.79    .016       0
 1550.43    .013       0 1592.34     .03       0
Levee=0,,,-1,1817.02,46.48,,
#Block Obstruct= 3 ,-1
       0    41.9      80  272.37  439.99      80  984.74 1194.25      80
#XS Lid=6
 1492.19   44.44   38.37 1497.34   44.37   38.37 1509.99   44.39   38.37
 1513.35   44.41   38.37 1518.98   44.46   38.37 1520.69   44.48   38.37
Bank Sta=1492.19,1520.69
XS Rating Curve= 0 ,0
Exp/Cntr=0.3,0.1

Type RM Length L Ch R = 1 ,5367.458,255.43,91.44,77.92
XS GIS Cut Line= 6
     3110835.512    13825807.543     3110394.457    13825591.697
     3110314.072    13825607.255     3109331.301    13825143.097
     3109177.188    13824748.378     3109092.739    13824489.645
#Sta/Elev= 30
       0   45.08  433.93   42.68  541.81   43.65  617.14   45.36  727.19    45.5
  869.44   43.74 1191.68   43.87 1350.79   45.63 1511.51   45.82 1601.87   44.65
 1648.98   44.64 1719.65   44.37 1760.66   44.22 1760.76   44.22 1760.76   26.82
 1774.51   26.82 1774.51   38.32 1775.51   38.32 1775.51   26.82 1789.26   26.82
 1789.26   44.67 1789.36   44.67 1813.88   44.36 1955.22   45.68 2002.33   45.63
 2049.45   45.77  2237.9   46.03 2307.32   45.56 2338.88   46.49 2355.69   45.52
#Mann= 12 ,-1 , 0
       0    .013       0  541.81     .03       0 1601.87    .013       0
 1648.98    .016       0 1719.65    .013       0 1760.66    .011       0
 1789.36     .03       0 1813.88    .016       0 1955.22      99       0
 2002.33    .025       0 2049.45    .016       0  2237.9     .03       0
Levee=0,,,-1,2234.5,46.09,,
#Block Obstruct= 1 ,-1
 1955.22 2002.33      80
#XS Lid=8
 1760.76   44.22   38.32 1764.43   44.27   38.32 1766.77   44.33   38.32
 1774.52   44.55   38.32 1778.84   44.74   38.32 1780.53   44.79   38.32
 1784.38   44.81   38.32 1789.26   44.67   38.32
Bank Sta=1760.76,1789.26
XS Rating Curve= 0 ,0
Exp/Cntr=0.3,0.1

Type RM Length L Ch R = 1 ,5276.014,44.06,43.04,46.36
XS GIS Cut Line= 6
     3110839.408    13825784.039     3110163.674    13825454.265
     3110116.084    13825467.168     3109430.514    13825130.504
     3109254.733    13824727.673     3109157.566    13824458.529
#Sta/Elev= 30
       0    46.3   38.76   45.31   88.83   45.94   281.4   44.28  778.82   42.71
  893.35   42.35 1061.27   42.13  1397.3   43.45 1534.74   44.28 1557.64   44.18
 1603.46   44.54 1695.62    44.7 1695.72    44.7 1695.72   26.76 1709.47   26.76
 1709.47   38.26 1710.47   38.26 1710.47   26.76 1724.22   26.76 1724.22    45.2
 1724.32    45.2 1740.89   45.54 1969.96   45.01 2061.58   45.47  2130.3   46.06
 2182.36   48.22 2199.02   47.71 2209.33   46.47 2244.84   47.09 2290.65   45.37
#Mann= 15 ,-1 , 0
       0     .03       0  778.82    .013       0  893.35     .03       0
  1397.3    .013       0 1534.74     .03       0 1557.64    .013       0
 1603.46    .016       0 1695.62    .011       0 1724.32    .016       0
 1740.89      99       0 1969.96    .025       0 2061.58    .016       0
  2130.3      99       0 2199.02     .03       0 2244.84      99       0
#Block Obstruct= 3 ,-1
 1740.89 1969.96      80  2130.3 2199.02      80 2244.84 2290.65      80
#XS Lid=5
 1695.72    44.7   38.26 1702.34   44.83   38.26  1717.8   45.06   38.26
 1723.07   45.24   38.26 1724.22    45.2   38.26
Bank Sta=1695.72,1724.22
XS Rating Curve= 0 ,0
Exp/Cntr=0.3,0.1

Type RM Length L Ch R = 1 ,5232.970,151.75,39.39,96.34
XS GIS Cut Line= 6
     3110712.332    13825712.739     3110140.337    13825420.555
     3110104.034    13825430.927     3109468.734    13825114.573
     3109297.591    13824710.056     3109204.241    13824450.749
#Sta/Elev= 30
       0   45.72  294.64   44.54  589.29   44.25  652.42   43.06  881.24   42.23
 1039.69   44.13 1149.71   43.17 1410.08   44.96 1473.22   45.21 1494.26   45.39
 1515.31   45.35 1520.96   45.09 1521.06   45.09 1521.06   26.74 1534.81   26.74
 1534.81   38.24 1535.81   38.24 1535.81   26.74 1549.56   26.74 1549.56   43.67
 1549.66   43.67 1580.09   41.94 1624.86   45.64 1746.81   44.85 1873.09   45.34
 1957.27   45.99 2020.41   47.48 2030.33   46.04  2062.5   47.16 2104.59   45.34
#Mann= 15 ,-1 , 0
       0     .03       0  294.64      99       0  589.29    .025       0
  652.42     .03       0 1410.08    .016       0 1473.22     .03       0
 1494.26    .016       0 1515.31      99       0 1520.96    .011       0
 1549.66      99       0 1746.81    .025       0 1873.09    .016       0
 1957.27      99       0 2020.41     .03       0  2062.5      99       0
#Block Obstruct= 5 ,-1
  294.64  589.29      80 1515.31 1519.52      80 1551.09 1746.81      80
 1957.27 2020.41      80  2062.5 2104.59      80
#XS Lid=8
 1521.06      80   38.24 1521.85      80   38.24 1529.78      80   38.24
  1533.3      80   38.24  1541.6      80   38.24 1544.74      80   38.24
 1546.07      80   38.24 1549.56      80   38.24
Bank Sta=1521.06,1549.56
XS Rating Curve= 0 ,0
Exp/Cntr=0.3,0.1

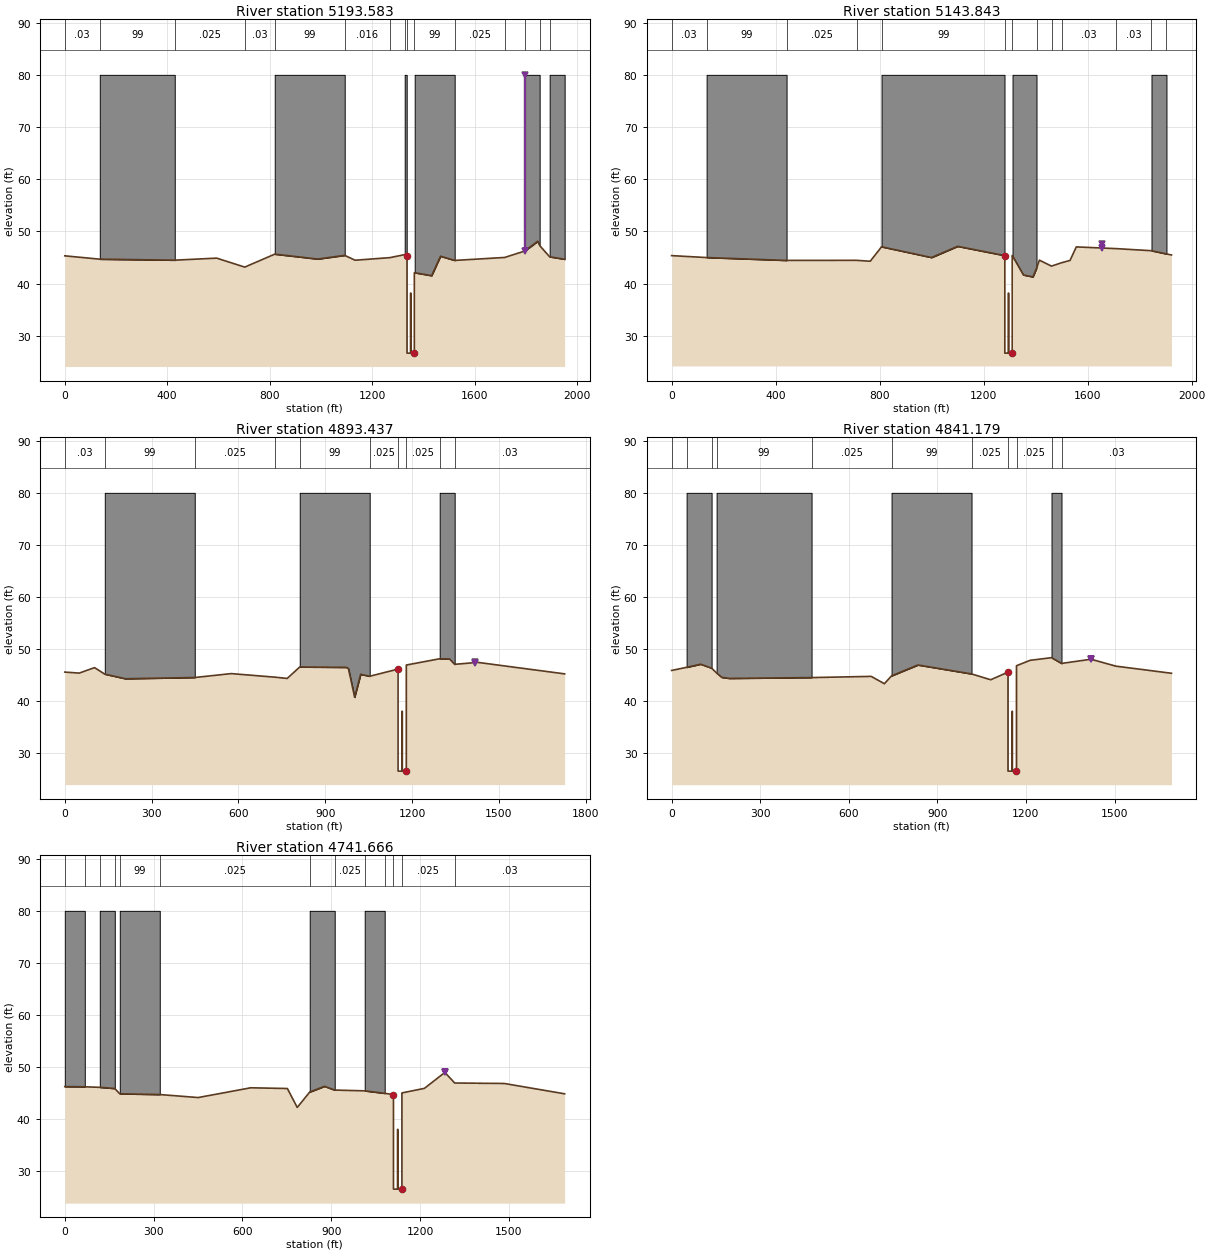
Type RM Length L Ch R = 1 ,5193.583,135.71,49.74,182.15
XS GIS Cut Line= 6
     3110568.192    13825630.593     3110046.987    13825303.867
     3109497.257     13825086.05     3109341.673    13824702.276
     3109370.197    13824655.601     3109282.033    13824406.667
#Sta/Elev= 30
       0   45.34  136.62    44.7  429.37   44.51  593.02    44.9  702.61   43.18
  819.71   45.66  987.54   44.72 1092.95   45.43 1133.64    44.5  1268.6   44.99
 1327.15   45.57 1336.23   45.37 1336.33   45.37 1336.33   26.71 1350.08   26.71
 1350.08   38.21 1351.08   38.21 1351.08   26.71 1364.83   26.71 1364.83   42.11
 1364.93   42.11 1432.33   41.54 1466.88   45.26 1522.32   44.46 1717.49   45.03
 1795.56   46.25 1846.72   48.13 1854.11   47.32 1893.15   45.15  1951.7   44.68
#Mann= 15 ,-1 , 0
       0     .03       0  136.62      99       0  429.37    .025       0
  702.61     .03       0  819.71      99       0 1092.95    .016       0
  1268.6     .03       0 1327.15      99       0 1336.23    .011       0
 1364.93      99       0 1522.32    .025       0 1717.49    .016       0
 1795.56      99       0 1854.11     .03       0 1893.15      99       0
Levee=0,,,-1,1795.56,80,,
#Block Obstruct= 6 ,-1
  136.62  429.37      80  819.71 1092.95      80 1327.15 1334.96      80
 1366.19 1522.32      80 1795.56 1854.11      80 1893.15  1951.7      80
#XS Lid=6
 1336.33      80   38.21 1343.35      80   38.21 1350.81      80   38.21
 1359.54      80   38.21 1363.23      80   38.21 1364.83      80   38.21
Bank Sta=1336.33,1364.83
XS Rating Curve= 0 ,0
Exp/Cntr=0.3,0.1

Type RM Length L Ch R = 1 ,5143.843,58.82,250.41,236.71
XS GIS Cut Line= 6
     3110575.171    13825626.318     3110005.498    13825241.634
     3109520.595    13825005.665     3109457.668    13824863.353
     3109549.118     13824704.87     3109447.989    13824362.585
#Sta/Elev= 30
       0   45.36  134.55   44.99   442.1   44.44   711.2   44.46  763.65   44.28
   807.3   47.05   999.5   44.99 1099.91   47.14 1281.18   45.36 1281.28   45.36
 1281.28   26.68 1295.03   26.68 1295.03   38.18 1296.03   38.18 1296.03   26.68
 1309.78   26.68 1309.78   45.39 1309.88   45.39 1352.83   41.65 1389.32   41.28
 1403.17   42.93 1414.28   44.49 1460.84   43.35 1499.28   43.99 1532.08   44.44
 1556.15   47.03 1710.72    46.7 1845.27    46.3 1902.93   45.68 1922.15   45.48
#Mann= 13 ,-1 , 0
       0     .03       0  134.55      99       0   442.1    .025       0
   711.2     .03       0   807.3      99       0 1281.18    .011       0
 1309.88      99       0 1403.17    .025       0 1460.84    .013       0
 1499.28     .03       0 1710.72     .03       0 1845.27      99       0
 1902.93     .03       0
Levee=0,,,-1,1653.6,47.57,,
#Block Obstruct= 4 ,-1
  134.55   442.1      80   807.3 1280.15      80 1310.91 1403.17      80
 1845.27 1902.93      80
#XS Lid=5
 1281.28      80   38.18 1281.38      80   38.18 1291.91      80   38.18
 1297.78      80   38.18 1309.78      80   38.18
Bank Sta=1281.28,1309.78
XS Rating Curve= 0 ,0
Exp/Cntr=0.3,0.1

Type RM Length L Ch R = 1 ,4893.437,142.4,52.26,52.35
XS GIS Cut Line= 4
     3110587.414    13825614.076     3110018.463    13825220.889
     3109756.564    13824956.397     3109572.456    13824318.503
#Sta/Elev= 30
       0   45.55   50.05   45.36  102.82   46.41  138.22   45.16  209.39   44.27
  449.21   44.51  575.32   45.26  725.65   44.58  768.78   44.33  812.04   46.53
  973.71   46.46  980.47   46.21 1001.94   40.72 1022.69   45.12 1053.92   44.75
 1151.88   46.13 1151.98   46.13 1151.98   26.52 1165.73   26.52 1165.73   38.02
 1166.73   38.02 1166.73   26.52 1180.48   26.52 1180.48   46.91 1180.59   46.91
 1295.81   48.11 1330.03   48.07 1347.64   47.04 1426.97   47.42 1727.74   45.21
#Mann= 10 ,-1 , 0
       0     .03       0  138.22      99       0  449.21    .025       0
  725.65     .03       0  812.04      99       0 1053.92    .025       0
 1151.88    .011       0 1180.59    .025       0 1295.81      99       0
 1347.64     .03       0
Levee=0,,,-1,1419.33,47.44,,
#Block Obstruct= 3 ,-1
  138.22  449.21      80  812.04 1053.92      80 1295.81 1347.64      80
#XS Lid=6
 1151.98   46.13   38.02 1158.29   46.36   38.02 1162.97   46.55   38.02
 1173.91   46.84   38.02 1175.09   46.86   38.02 1180.48   46.91   38.02
Bank Sta=1151.98,1180.48
XS Rating Curve= 0 ,0
Exp/Cntr=0.3,0.1

Type RM Length L Ch R = 1 ,4841.179,136.72,99.51,102.39
XS GIS Cut Line= 4
     3110596.716    13825602.069      3110202.57    13825148.283
     3109808.425    13824948.617     3109629.503    13824323.689
#Sta/Elev= 30
       0   45.84   50.79   46.44   98.24   47.04  135.43   46.28  152.36   45.36
  169.73   44.51  196.26   44.31  474.02   44.47  675.96    44.7   720.6   43.29
  744.89    44.8  834.22   46.89 1015.76   45.17 1080.78   44.05 1139.38   45.52
 1139.48   45.52 1139.48   26.48 1153.23   26.48 1153.23   37.98 1154.23   37.98
 1154.23   26.48 1167.98   26.48 1167.98   46.75 1168.08   46.75  1214.2   47.79
 1286.63    48.3 1320.49   47.19 1420.41      48 1504.33   46.67 1692.93    45.3
#Mann= 11 ,-1 , 0
       0     .03       0   50.79      99       0  135.43     .03       0
  152.36      99       0  474.02    .025       0  744.89      99       0
 1015.76    .025       0 1139.38    .011       0 1168.08    .025       0
 1286.63      99       0 1320.49     .03       0
Levee=0,,,-1,1420.41,48,,
#Block Obstruct= 4 ,-1
   50.79  135.43      80  152.36  474.02      80  744.89 1015.76      80
 1286.63 1320.49      80
#XS Lid=4
 1139.48   45.52   37.98 1144.83   45.77   37.98 1153.56   46.07   37.98
 1167.98   46.75   37.98
Bank Sta=1139.48,1167.98
XS Rating Curve= 0 ,0
Exp/Cntr=0.3,0.1

Type RM Length L Ch R = 1 ,4741.666,77.59,196.1,195.57
XS GIS Cut Line= 4
     3110611.898    13825589.591     3110290.734    13825036.782
     3109878.437    13824837.116     3109746.191    13824261.456
#Sta/Elev= 30
       0   46.16   67.52   46.12  118.17   46.02  168.81   45.79  185.69   44.77
  320.74   44.63  450.28   44.05  628.05   45.93  751.73   45.79  785.06   42.15
  827.16   45.11  876.87   46.21  911.57   45.49 1012.85   45.34 1080.37   44.86
 1109.92   44.62 1110.02   44.62 1110.02   26.42 1123.77   26.42 1123.77   37.92
 1124.77   37.92 1124.77   26.42 1138.52   26.42 1138.52   44.94 1138.62   44.94
 1214.54   45.82 1283.65   48.89 1316.71   46.85 1484.22   46.76 1688.09   44.77
#Mann= 13 ,-1 , 0
       0      99       0   67.52     .03       0  118.17      99       0
  168.81     .03       0  185.69      99       0  320.74    .025       0
  827.16      99       0  911.57    .025       0 1012.85      99       0
 1080.37    .025       0 1109.92    .011       0 1138.62    .025       0
 1316.71     .03       0
Levee=0,,,-1,1283.65,48.89,,
#Block Obstruct= 5 ,-1
       0   67.52      80  118.17  168.81      80  185.69  320.74      80
  827.16  911.57      80 1012.85 1080.37      80
#XS Lid=5
 1110.02   44.62   37.92 1114.69   44.62   37.92 1128.19   44.66   37.92
  1131.7    44.7   37.92 1138.52   44.94   37.92
Bank Sta=1110.02,1138.52
XS Rating Curve= 0 ,0
Exp/Cntr=0.3,0.1