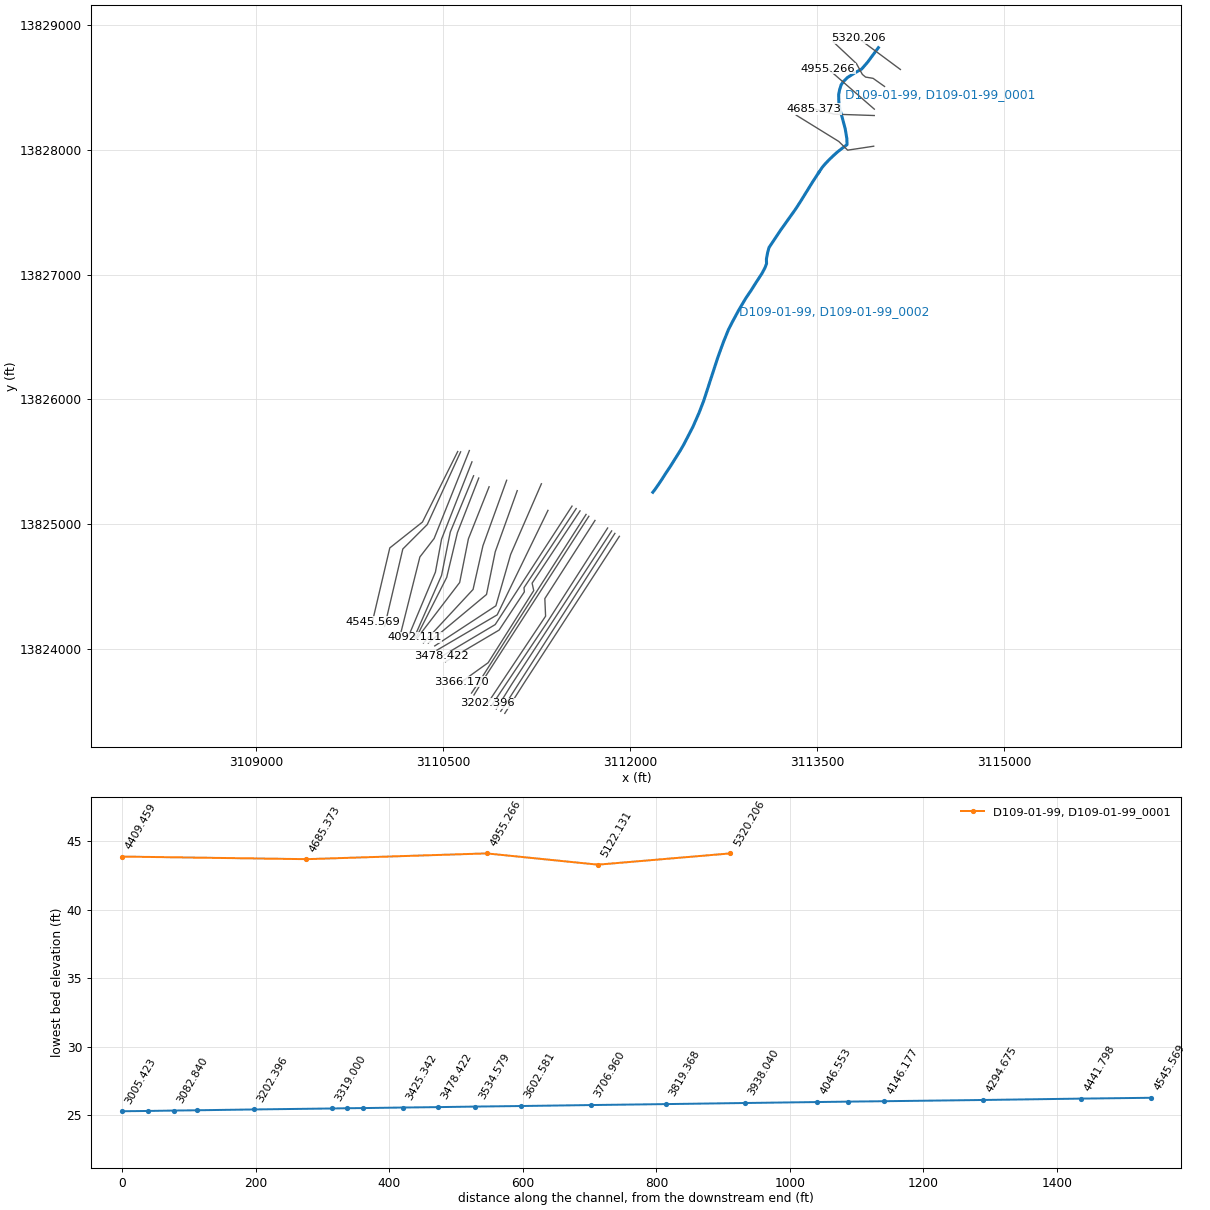
HEC-RAS study D109-00-00.prj: D109-00-00

--- D109-00-00.g01 (geometry) --- (continued)

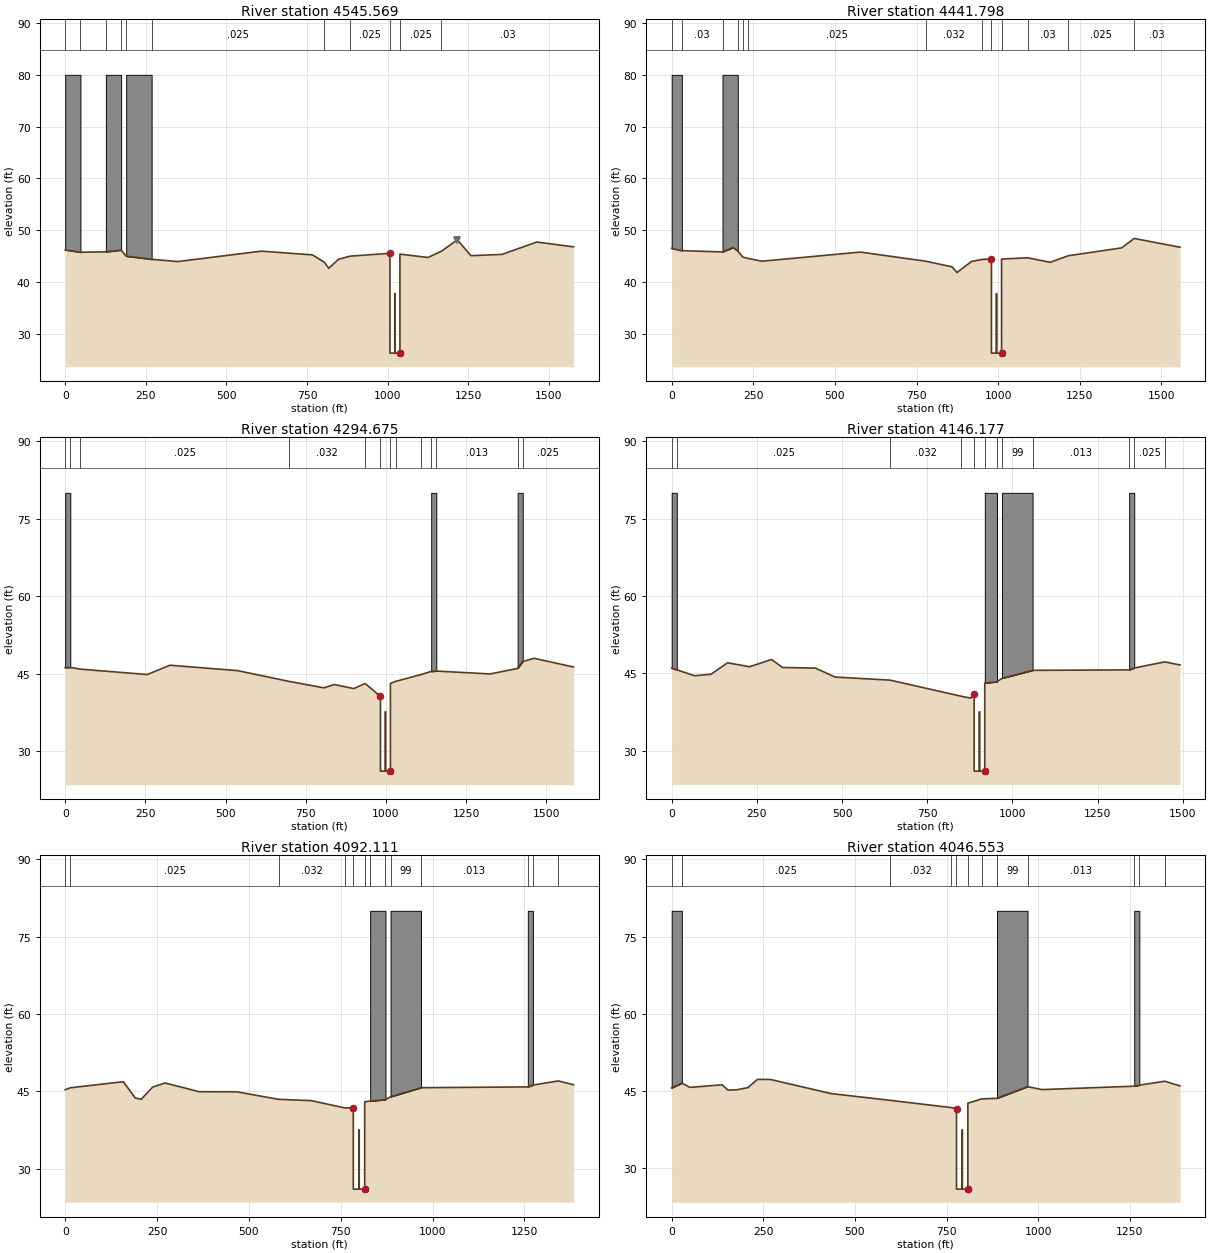
Type RM Length L Ch R = 1 ,4545.569,61.01,103.77,103.82
XS GIS Cut Line= 4
      3110617.46    13825581.325     3110334.816    13825016.037
     3110072.917    13824808.592     3109932.892    13824214.781
#Sta/Elev= 30
       0   46.21   47.29   45.76   126.1   45.84  173.38   46.17  189.15      45
  267.96    44.4  349.27   43.96  607.86   45.97  766.71   45.25  803.87   43.81
   817.3   42.66  847.16   44.39  882.68      45 1006.83   45.55 1006.93   45.55
 1006.93   26.29 1021.93   26.29 1021.93   37.79 1022.93   37.79 1022.93   26.29
 1037.93   26.29 1037.93    45.4 1038.03    45.4 1124.87   44.75  1166.4   45.95
 1215.75   48.15 1258.19    45.1 1354.45   45.34 1462.33   47.73 1576.21    46.8
#Mann= 11 ,-1 , 0
       0      99       0   47.29     .03       0   126.1      99       0
  173.38     .03       0  189.15      99       0  267.96    .025       0
  803.87    .032       0  882.68    .025       0 1006.83    .011       0
 1038.03    .025       0  1166.4     .03       0
Levee=0,,,-1,1215.75,48.15,,
#Block Obstruct= 3 ,-1
       0   47.29      80   126.1  173.38      80  189.15  267.96      80
#XS Lid=5
 1006.93   45.55   37.79 1008.78   45.53   37.79  1015.4   45.38   37.79
 1026.11    45.3   37.79 1037.93    45.4   37.79
Bank Sta=1006.93,1037.93
XS Rating Curve= 0 ,0
Exp/Cntr=0.3,0.1

Type RM Length L Ch R = 1 ,4441.798,136.53,147.12,146.32
XS GIS Cut Line= 4
     3110640.798    13825578.732     3110373.173    13824995.838
     3110177.296    13824799.961     3110031.428    13824178.478
#Sta/Elev= 30
       0   46.46   31.14   46.03  155.68   45.78  188.03   46.64  202.38   45.97
  217.95   44.78  233.52   44.53  276.28   43.99  578.32   45.75  778.39   43.99
  858.62    42.9   873.9   41.81  918.41   43.94  949.64   44.32  979.18   44.45
  979.28   44.45  979.28   26.23  994.28   26.23  994.28   37.73  995.28   37.73
  995.28   26.23 1010.28   26.23 1010.28    44.4 1010.38    44.4 1089.75   44.65
 1159.12   43.78 1214.29   45.04 1377.68   46.56 1416.67   48.39 1556.78   46.69
#Mann= 13 ,-1 , 0
       0      99       0   31.14     .03       0  155.68      99       0
  202.38     .03       0  217.95    .025       0  233.52    .025       0
  778.39    .032       0  949.64    .025       0  979.18    .011       0
 1010.38    .025       0 1089.75     .03       0 1214.29    .025       0
 1416.67     .03       0
#Block Obstruct= 2 ,-1
       0   31.14      80  155.68  202.38      80
#XS Lid=3
  979.28   44.45   37.73  983.21   44.48   37.73 1010.28    44.4   37.73
Bank Sta=979.28,1010.28
XS Rating Curve= 0 ,0
Exp/Cntr=0.3,0.1

Type RM Length L Ch R = 1 ,4294.675,138.73,148.5,146.74
XS GIS Cut Line= 4
     3110710.811    13825589.104     3110428.167    13824883.791
     3110314.072    13824735.986     3110158.488    13824116.244
#Sta/Elev= 30
       0   46.17   15.86    46.2   47.57   45.87  255.72   44.83  326.94   46.63
  537.02   45.59  697.63   43.51  806.63   42.25  839.64   42.89  900.12   42.11
  935.46   43.09  983.28    40.6  983.38    40.6  983.38   26.13  998.38   26.13
  998.38   37.63  999.38   37.63  999.38   26.13 1014.38   26.13 1014.38   43.11
 1014.48   43.11 1030.59    43.5 1109.87   44.82 1141.58   45.43 1157.44    45.5
 1325.55   44.94 1411.12   46.01 1426.98   47.33 1462.45   47.97 1585.53   46.28
#Mann= 13 ,-1 , 0
       0      99       0   15.86     .03       0   47.57    .025       0
  697.63    .032       0  935.46    .025       0  983.28    .011       0
 1014.48    .025       0 1030.59     .03       0 1109.87    .025       0
 1141.58      99       0 1157.44    .013       0 1411.12      99       0
 1426.98    .025       0
#Block Obstruct= 3 ,-1
       0   15.86      80 1141.58 1157.44      80 1411.12 1426.98      80
#XS Lid=6
  983.38    40.6   37.63  989.05   41.38   37.63  998.49   42.28   37.63
 1004.13   42.77   37.63 1013.95   43.08   37.63 1014.38   43.11   37.63
Bank Sta=983.38,1014.38
XS Rating Curve= 0 ,0
Exp/Cntr=0.5,0.3

Type RM Length L Ch R = 1 ,4146.177,57.37,54.07,55.06
XS GIS Cut Line= 4
     3110731.555    13825498.347     3110487.807    13824878.605
     3110438.539    13824614.112     3110223.315    13824100.686
#Sta/Elev= 30
       0   45.99   14.92   45.69    67.4   44.53  115.76   44.83  164.11   47.05
  228.59   46.28  293.06   47.68   325.3   46.14  422.01   46.01  479.54   44.28
  641.43   43.68  850.27   40.55  877.51    40.2  887.63   41.02  887.73   41.02
  887.73   26.04  902.73   26.04  902.73   37.54  903.73   37.54  903.73   26.04
  918.73   26.04  918.73   43.11  918.83   43.11  954.69   43.37  969.61   44.04
 1059.12   45.58 1342.54   45.67 1357.45   46.03 1446.96   47.22 1491.71   46.63
#Mann= 12 ,-1 , 0
       0      99       0   14.92    .025       0  641.43    .032       0
  850.27    .025       0  887.63    .011       0  918.83      99       0
  954.69     .03       0  969.61      99       0 1059.12    .013       0
 1342.54      99       0 1357.45    .025       0 1446.96    .016       0
#Block Obstruct= 4 ,-1
       0   14.92      80  918.89  954.69      80  969.61 1059.12      80
 1342.54 1357.45      80
#XS Lid=7
  887.73   41.02   37.54  902.04    42.2   37.54  908.03   42.73   37.54
   909.4   42.77   37.54  909.94   42.79   37.54  909.94      80   37.54
  918.73      80   37.54
Bank Sta=887.73,918.73
XS Rating Curve= 0 ,0
Exp/Cntr=0.5,0.3

Type RM Length L Ch R = 1 ,4092.111,47.48,45.56,42.91
XS GIS Cut Line= 4
      3110744.52    13825386.845      3110557.82    13824935.652
     3110487.807    13824588.182      3110269.99    13824092.907
#Sta/Elev= 30
       0   45.29   13.84   45.67  158.25   46.85  190.72   43.69  206.95   43.44
   238.2   45.81  271.88    46.6   364.5   44.91  466.68   44.89   581.2   43.43
  669.37   43.18  761.09   41.77  784.24   41.78  784.34   41.78  784.34   26.01
  799.34   26.01  799.34   37.51  800.34   37.51  800.34   26.01  815.34   26.01
  815.34   42.95  815.44   42.95  830.28   43.08   871.8   43.37  885.63   43.92
  968.66   45.69 1259.26   45.84  1273.1    46.2 1342.29      47  1383.8   46.26
#Mann= 13 ,-1 , 0
       0     .03       0   13.84    .025       0   581.2    .032       0
  761.09    .025       0  784.24    .011       0  815.44    .025       0
  830.28      99       0   871.8     .03       0  885.63      99       0
  968.66    .013       0 1259.26      99       0  1273.1    .025       0
 1342.29    .016       0
#Block Obstruct= 3 ,-1
  885.63  968.66      80 1259.26  1273.1      80  830.28   871.8      80
#XS Lid=6
  784.34   41.78    37.5  789.26   41.77    37.5  793.33   41.88    37.5
  802.05   42.33    37.5  814.18   42.95    37.5  815.34   42.95    37.5
Bank Sta=784.34,815.34
XS Rating Curve= 0 ,0
Exp/Cntr=0.5,0.3

Type RM Length L Ch R = 1 ,4046.553,107.56,108.51,104.22
XS GIS Cut Line= 4
     3110786.009    13825368.694     3110614.867    13824930.466
     3110529.296    13824572.623     3110281.355    13824083.785
#Sta/Elev= 30
       0   45.63   27.73   46.56    49.8   45.73  137.49   46.23   153.6    45.2
  177.19   45.26  207.74   45.68  234.11   47.29  269.84   47.26  434.56   44.53
   596.2   43.21  762.58   41.81   776.8   41.56   776.9   41.56   776.9   25.98
   791.9   25.98   791.9   37.48   792.9   37.48   792.9   25.98   807.9   25.98
   807.9   42.67     808   42.67  845.77   43.49  887.37   43.62  970.56   45.88
    1010    45.3 1261.73   45.96 1275.59   46.16 1344.92   46.92 1386.51   46.02
#Mann= 12 ,-1 , 0
       0      99       0   27.73    .025       0   596.2    .032       0
  762.58    .025       0   776.8    .011       0     808    .025       0
  845.77     .03       0  887.37      99       0  970.56    .013       0
 1261.73      99       0 1275.59    .025       0 1344.92    .016       0
#Block Obstruct= 3 ,-1
       0   27.73      80  887.37  970.56      80 1261.73 1275.59      80
#XS Lid=7
   776.9   41.56   37.48  777.59   41.53   37.48   783.9   41.56   37.48
  790.04   41.76   37.48  799.32   42.26   37.48  805.86   42.56   37.48
   807.9   42.67   37.48
Bank Sta=776.9,807.9
XS Rating Curve= 0 ,0
Exp/Cntr=0.5,0.3

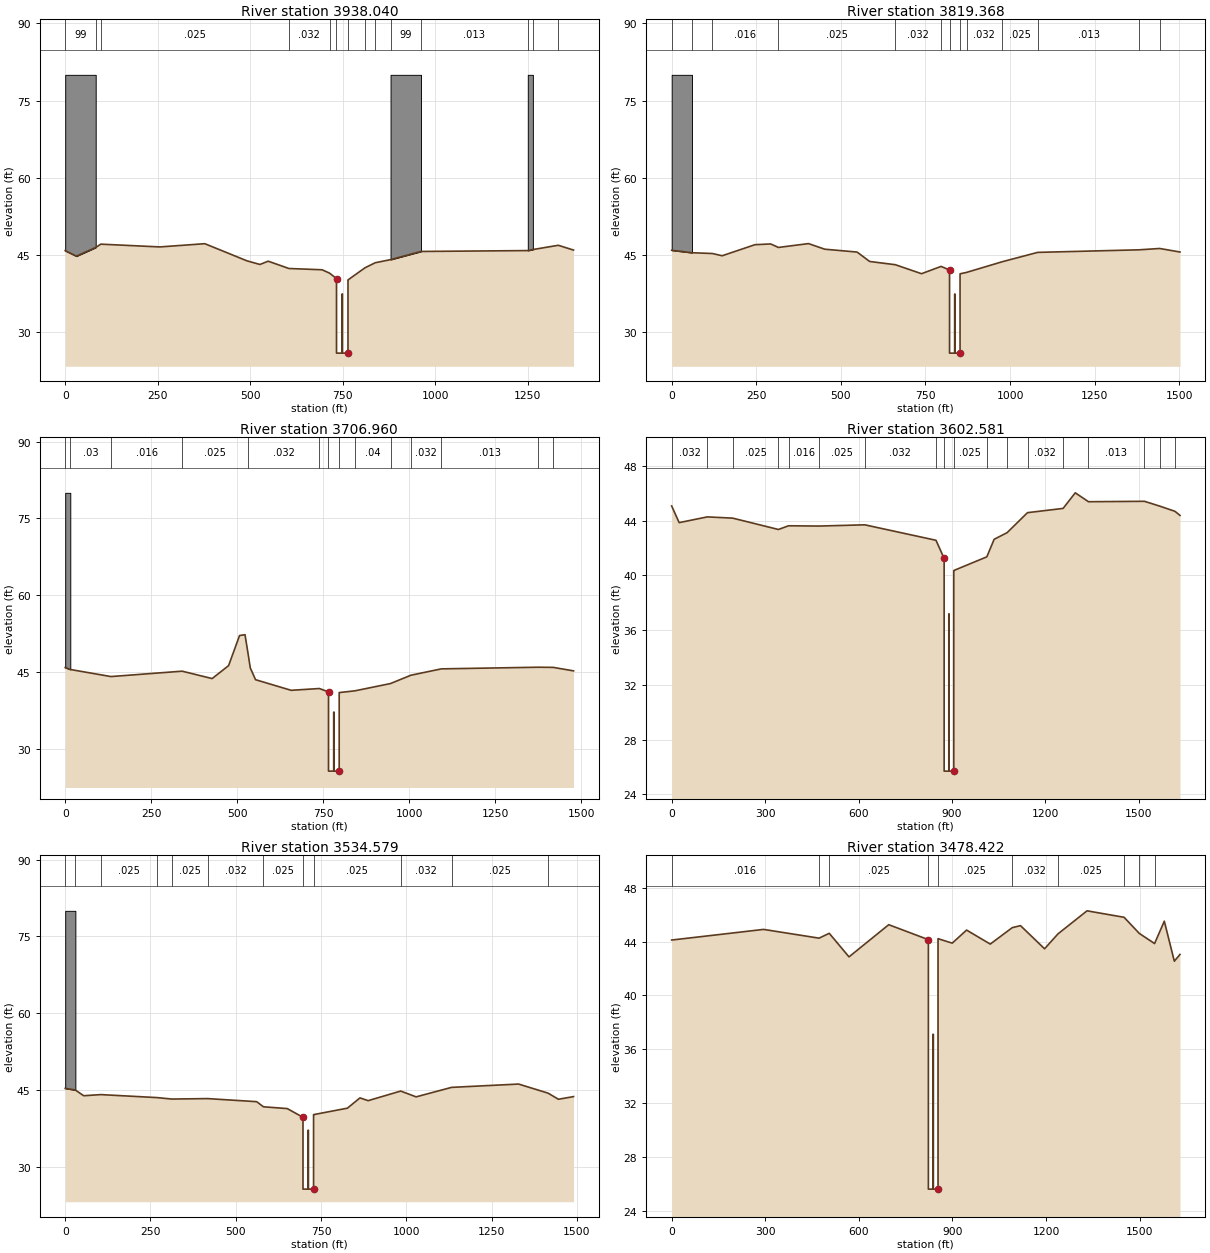
Type RM Length L Ch R = 1 ,3938.040,119.35,118.67,112.12
XS GIS Cut Line= 4
     3110868.987    13825298.681     3110703.031    13824881.198
     3110633.019    13824531.134     3110288.141    13824079.941
#Sta/Elev= 30
       0   45.82    30.2   44.75   82.45   46.44   96.19   47.09  256.18   46.55
  377.41   47.18  490.93   43.86  526.33   43.14  548.74   43.78  604.63   42.36
   694.6   42.11  714.56   41.46  733.32   40.41  733.42   40.41  733.42   25.91
  748.42   25.91  748.42   37.41  749.42   37.41  749.42   25.91  764.42   25.91
  764.42   40.14  764.52   40.14  810.75   42.51  838.24   43.48  879.46   44.08
  961.91   45.67 1250.49   45.84 1264.23   46.04 1332.94   46.87 1374.16   45.94
#Mann= 14 ,-1 , 0
       0      99       0   82.45    .016       0   96.19    .025       0
  604.63    .032       0  714.56    .025       0  733.32    .011       0
  764.52    .025       0  810.75    .025       0  838.24     .03       0
  879.46      99       0  961.91    .013       0 1250.49      99       0
 1264.23    .025       0 1332.94    .016       0
#Block Obstruct= 3 ,-1
       0   82.45      80  879.46  961.91      80 1250.49 1264.23      80
#XS Lid=3
  733.42   40.41   37.41  740.49   40.17   37.41  764.42   40.14   37.41
Bank Sta=733.42,764.42
XS Rating Curve= 0 ,0
Exp/Cntr=0.5,0.3

Type RM Length L Ch R = 1 ,3819.368,111.71,112.41,91.05
XS GIS Cut Line= 4
     3111009.774    13825350.866     3110819.624    13824825.918
     3110740.443     13824475.54     3110342.567    13824047.059
#Sta/Elev= 30
       0   45.85   60.09   45.37  120.18   45.22  149.16   44.78  246.29   46.94
  292.75   47.08  315.48    46.4  404.42   47.15  452.28   46.06  548.01    45.5
  585.14   43.67     661   43.04  738.41   41.29   796.2   42.71  821.16   42.01
  821.26   42.01  821.26   25.83  836.26   25.83  836.26   37.33  837.26   37.33
  837.26   25.83  852.26   25.83  852.26   41.27  852.36   41.27  871.31   41.54
  976.47   43.61 1081.63   45.44 1382.08   45.94 1442.17    46.2 1502.26   45.51
#Mann= 13 ,-1 , 0
       0      99       0   60.09     .03       0  120.18    .016       0
  315.48    .025       0     661    .032       0   796.2    .025       0
  821.16    .011       0  852.36    .025       0  871.31    .032       0
  976.47    .025       0 1081.63    .013       0 1382.08    .025       0
 1442.17    .016       0
#Block Obstruct= 1 ,-1
       0   60.09      80
#XS Lid=7
  821.26   42.01   37.33  823.56    41.9   37.33  825.19   41.82   37.33
  830.75   41.57   37.33  840.56   41.14   37.33   851.3   41.27   37.33
  852.26   41.27   37.33
Bank Sta=821.26,852.26
XS Rating Curve= 0 ,0
Exp/Cntr=0.5,0.3

Type RM Length L Ch R = 1 ,3706.960,106.82,104.38,103.11
XS GIS Cut Line= 4
     3111094.584    13825267.564     3110918.256    13824777.475
     3110848.243    13824435.191     3110381.492    13824046.232
#Sta/Elev= 30
       0   45.94   14.78   45.57     133   44.19  339.89   45.24  427.17    43.8
  474.99   46.32  506.87   52.19  522.74   52.35     532   48.49  538.05   45.88
  553.36   43.58  656.88   41.51  738.89   41.86  765.41    41.2  765.51    41.2
  765.51   25.76  780.51   25.76  780.51   37.26  781.51   37.26  781.51   25.76
  796.51   25.76  796.51   41.07  796.61   41.07  842.34   41.41  945.78   42.83
  1004.9   44.45 1093.56   45.69 1374.34   46.01 1418.68   45.98 1477.79    45.3
#Mann= 14 ,-1 , 0
       0      99       0   14.78     .03       0     133    .016       0
  339.89    .025       0     532    .032       0  738.89    .025       0
  765.41    .011       0  796.61    .025       0  842.34     .04       0
  945.78    .025       0  1004.9    .032       0 1093.56    .013       0
 1374.34    .025       0 1418.68    .016       0
#Block Obstruct= 1 ,-1
       0   14.78      80
#XS Lid=6
  765.51    41.2   37.26  767.71   41.09   37.26  781.55   41.03   37.26
  783.02   41.02   37.26  788.73   41.02   37.26  796.51   41.07   37.26
Bank Sta=765.51,796.51
XS Rating Curve= 0 ,0
Exp/Cntr=0.5,0.3

Type RM Length L Ch R = 1 ,3602.581,72.51,68,61.9
XS GIS Cut Line= 4
     3111288.314    13825322.656     3111041.996    13824756.651
     3110923.442    13824344.434     3110433.353    13824022.894
#Sta/Elev= 30
       0   45.08   24.03   43.86  114.27   44.28  195.88   44.19   342.8   43.36
  375.44   43.63  473.38   43.61   620.3    43.7  848.83   42.57  874.85   41.25
  874.95   41.25  874.95   25.69  889.95   25.69  889.95   37.19  890.95   37.19
  890.95   25.69  905.95   25.69  905.95   40.36  906.05   40.36 1012.06   41.36
 1035.51   42.64 1077.36   43.13 1142.65   44.59 1256.92    44.9 1296.02   46.04
 1338.53   45.39 1518.09   45.42 1567.06   45.07 1616.04   44.69 1632.36   44.39
#Mann= 18 ,-1 , 0
       0    .032       0  114.27     .03       0  195.88    .025       0
   342.8    .013       0  375.44    .016       0  473.38    .025       0
   620.3    .032       0  848.83    .025       0  874.85    .011       0
  906.05    .025       0 1012.06    .032       0 1077.36    .025       0
 1142.65    .032       0 1256.92    .025       0 1338.53    .013       0
 1518.09    .025       0 1567.06    .032       0 1616.04    .032       0
#XS Lid=6
  874.95   41.25   37.19  878.49   40.99   37.19  885.41   40.59   37.19
  894.09   40.46   37.19  899.06    40.4   37.19  905.95   40.36   37.19
Bank Sta=874.95,905.95
XS Rating Curve= 0 ,0
Exp/Cntr=0.5,0.3

Type RM Length L Ch R = 1 ,3534.579,59.51,56.16,59.74
XS GIS Cut Line= 3
     3111340.925    13825109.387     3110933.814    13824271.828
     3110451.504    13823989.184
#Sta/Elev= 30
       0   45.32   29.81      45   54.22   43.89  104.32   44.11  268.25   43.53
  312.96   43.24  417.28   43.33  561.24   42.73  581.21   41.73  651.02   41.38
  697.01   39.68  697.11   39.68  697.11   25.65  712.11   25.65  712.11   37.15
  713.11   37.15  713.11   25.65  728.11   25.65  728.11    40.2  728.21    40.2
  827.34   41.46  864.26   43.47  888.13   42.93  983.59    44.8  1028.9   43.67
 1132.62   45.52 1329.22   46.17 1415.77   44.39 1446.16    43.2 1490.29   43.72
#Mann= 12 ,-1 , 0
       0      99       0   29.81     .32       0  104.32    .025       0
  268.25    .013       0  312.96    .025       0  417.28    .032       0
  581.21    .025       0  697.01    .011       0  728.21    .025       0
  983.59    .032       0 1132.62    .025       0 1415.77    .032       0
#Block Obstruct= 1 ,-1
       0   29.81      80
#XS Lid=7
  697.11   39.68   37.15  704.67   39.37   37.15  712.21   39.67   37.15
  718.36   40.01   37.15  719.56   40.17   37.15  723.11   40.16   37.15
  728.11    40.2   37.15
Bank Sta=697.11,728.11
XS Rating Curve= 0 ,0
Exp/Cntr=0.5,0.3

Type RM Length L Ch R = 1 ,3478.422,58.24,53.08,54.01
XS GIS Cut Line= 3
     3111533.829    13825143.743     3110917.956    13824193.966
       3110490.4    13823939.916
#Sta/Elev= 30
       0   44.11  294.54    44.9   472.5   44.25  505.09   44.61  568.41   42.86
  695.81   45.25  822.69   44.14  822.79   44.14  822.79   25.61  837.79   25.61
  837.79   37.11  838.79   37.11  838.79   25.61  853.79   25.61  853.79   44.21
  853.89   44.21  899.26   43.88  945.25   44.85 1021.16   43.81 1091.64   45.03
 1118.09   45.18 1195.26   43.46 1238.28   44.57 1331.34   46.28 1450.09    45.8
 1498.97    44.6 1547.85   43.85    1579   45.51 1611.16   42.54 1629.32   43.04
#Mann= 10 ,-1 , 0
       0    .016       0   472.5    .013       0  505.09    .025       0
  822.69    .011       0  853.89    .025       0 1091.64    .032       0
 1238.28    .025       0 1450.09     .32       0 1498.97    .025       0
 1547.85     .03       0
#XS Lid=7
  822.79   44.14   37.11  825.95   44.06   37.11  832.05   44.17   37.11
  844.12   44.13   37.11  847.64   44.07   37.11  849.93   44.16   37.11
  853.79   44.21   37.11
Bank Sta=822.79,853.79
XS Rating Curve= 0 ,0
Exp/Cntr=0.8,0.6

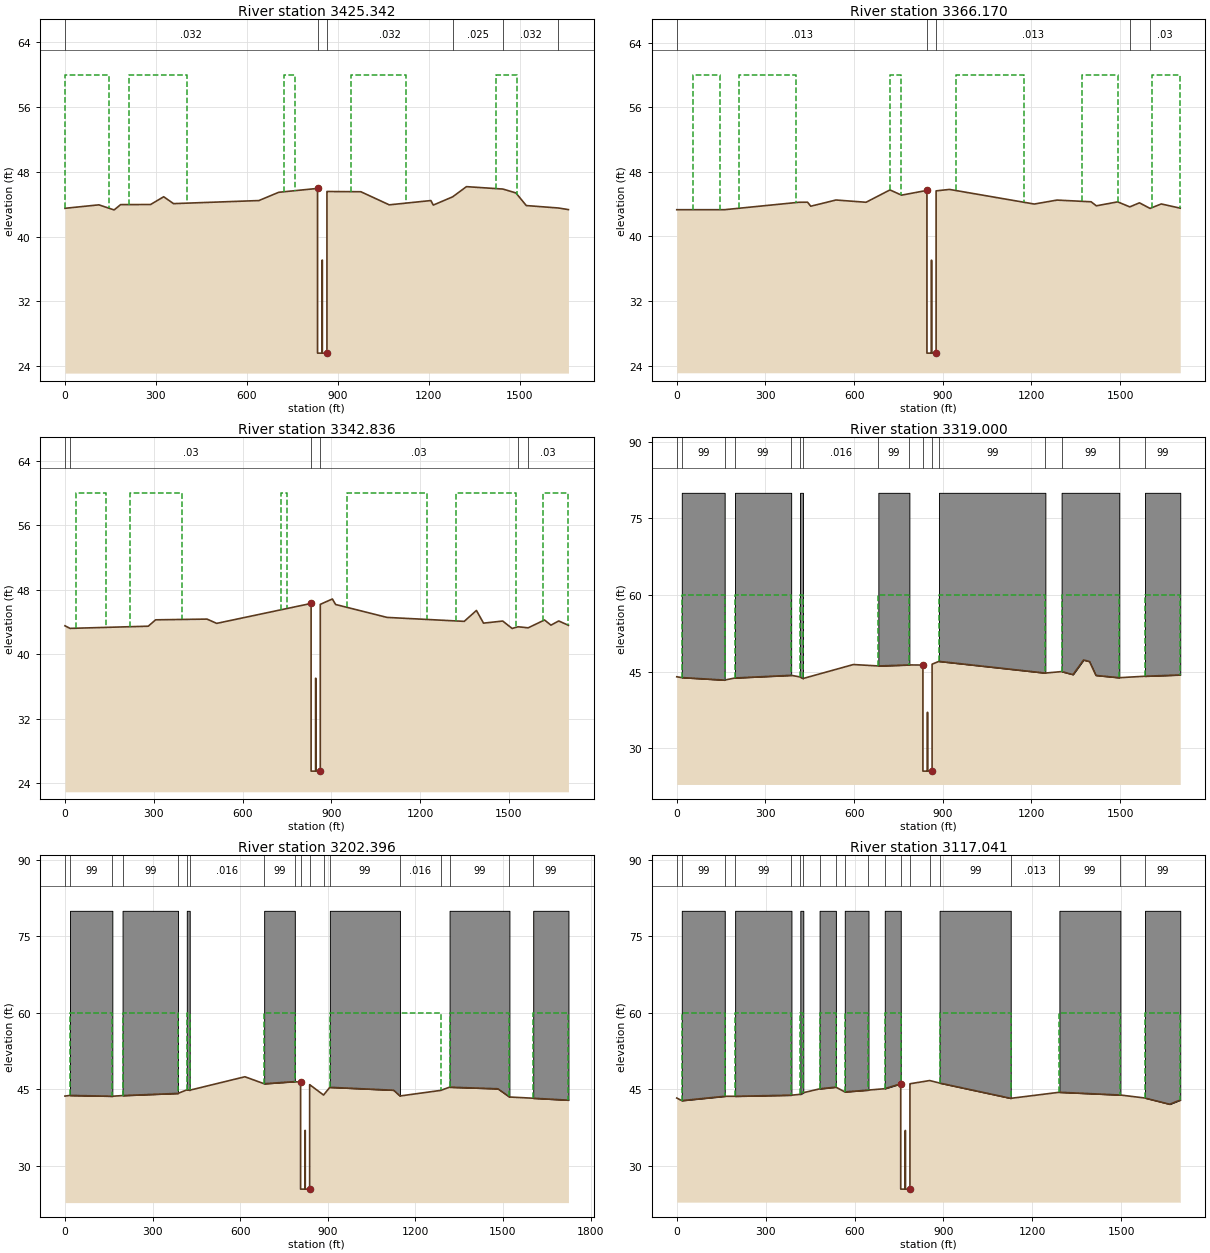
Type RM Length L Ch R = 1 ,3425.342,73.39,59.17,295.49
XS GIS Cut Line= 5
     3111567.205    13825123.965     3111149.038    13824489.645
     3111151.631    13824455.936     3110949.372    13824149.954
     3110518.924    13823895.834
#Sta/Elev= 30
       0   43.49   111.8   43.92  162.01   43.29  183.67   43.95  282.23   43.96
  325.54   44.92  358.03   44.07  639.56   44.45  704.69   45.47  832.77   45.95
  832.87   45.95  832.87   25.58  847.87   25.58  847.87   37.08  848.87   37.08
  848.87   25.58  863.87   25.58  863.87   45.57  863.97   45.57   975.7   45.54
 1069.31   43.92 1206.57   44.45 1214.48   43.89 1278.36   44.91 1324.01   46.17
 1444.39   45.87 1487.13   45.39 1521.16   43.83 1627.01   43.53 1660.21   43.33
#Mann= 6 ,-1 , 0
       0    .032       0  832.77    .011       0  863.97    .032       0
 1278.36    .025       0 1444.39    .032       0 1627.01    .013       0
#XS Ineff= 5 ,-1
       0  146.34      60  211.34  401.85      60  722.39  759.56      60
  943.83    1125      60    1420 1492.02      60
Permanent Ineff=
       F       F       F       F       F
#XS Lid=6
  832.87   45.95   37.08  834.97   45.94   37.08  841.89   45.67   37.08
   851.7   45.47   37.08  859.87   45.54   37.08  863.87   45.57   37.08
Bank Sta=832.87,863.87
XS Rating Curve= 0 ,0
Exp/Cntr=0.8,0.6

Type RM Length L Ch R = 1 ,3366.170,52.59,23.33,73.26
XS GIS Cut Line= 5
     3111598.108    13825105.423     3111213.865    13824525.948
      3111226.83    13824466.308     3110861.208    13823888.055
     3110647.526    13823734.557
#Sta/Elev= 30
       0    43.3  161.74    43.3  413.72   44.22   442.5   44.23  453.33   43.73
  538.72    44.5  640.57   44.22  721.38   45.75  760.55    45.1  846.41   45.69
  846.51   45.69  846.51   25.54  861.51   25.54  861.51   37.04  862.51   37.04
  862.51   25.54  877.51   25.54  877.51   45.63  877.61   45.63  922.78   45.81
 1209.63      44 1286.72   44.49 1401.94   44.28 1419.69   43.78 1491.74   44.27
 1532.96   43.65 1565.61   44.15 1601.36   43.46 1639.49   44.01 1703.57   43.49
#Mann= 5 ,-1 , 0
       0    .013       0  846.41    .011       0  877.61    .013       0
 1532.96    .013       0 1601.36     .03       0
#XS Ineff= 6 ,-1
      54  146.34      60  211.34  401.85      60  722.39  759.56      60
  943.83    1175      60    1370 1492.02      60 1608.16 1703.39      60
Permanent Ineff=
       F       F       F       F       F       F
#XS Lid=5
  846.51   45.69   37.04  851.79   45.69   37.04  859.94   45.78   37.04
  872.82   45.63   37.04  877.51   45.63   37.04
Bank Sta=846.51,877.51
XS Rating Curve= 0 ,0
Exp/Cntr=0.9,0.9

Type RM Length L Ch R = 1 ,3342.836,24.35,23.84,19.75
XS GIS Cut Line= 4
     3111646.317    13825076.992     3111084.212    13824199.222
     3110804.158    13823758.517     3110728.104     13823645.04
#Sta/Elev= 30
       0   43.53   17.01   43.21  281.38   43.48  306.29   44.27  480.03   44.36
   512.6   43.83  831.54    46.3  831.64    46.3  831.64   25.53  846.64   25.53
  846.64   37.03  847.64   37.03  847.64   25.53  862.64   25.53  862.64   46.19
  862.74   46.19  903.51   46.85  914.37   46.17 1088.06   44.57 1348.94   44.08
 1390.19   45.43 1414.15   43.86 1479.05   44.12 1510.78    43.2 1530.98   43.41
    1565   43.28 1620.33   44.25 1641.95   43.61 1668.35   44.13 1701.09   43.59
#Mann= 6 ,-1 , 0
       0    .016       0   17.01     .03       0  831.54    .011       0
  862.74     .03       0 1530.98    .013       0    1565     .03       0
#XS Ineff= 6 ,-1
   37.01  138.34      60  219.34  393.85      60  730.39  751.56      60
  951.83    1223      60    1320 1524.02      60 1616.16 1701.09      60
Permanent Ineff=
       F       F       F       F       F       F
#XS Lid=7
  831.64    46.3   37.03  837.68   46.43   37.03  838.36   46.45   37.03
  838.79   46.44   37.03  849.22   46.25   37.03  856.61   46.24   37.03
  862.64   46.19   37.03
Bank Sta=831.64,862.64
XS Rating Curve= 0 ,0
Exp/Cntr=0.9,0.9

Type RM Length L Ch R = 1 ,3319.000,61.35,116.6,133.48
XS GIS Cut Line= 3
     3111668.567    13825062.158     3110822.312    13823750.623
     3110747.419    13823629.346
#Sta/Elev= 30
       0   43.98   17.03   43.83  162.03   43.33  197.03   43.75  387.03   44.27
  417.03   43.95  427.03   43.64  597.58   46.38  682.03    46.1  787.03    46.3
  832.69   46.28  832.79   46.38  832.79   25.51  847.79   25.51  847.79   37.01
  848.79   37.01  848.79   25.51  863.79   25.51  863.79   46.45  863.89   46.45
  887.03      47 1247.03   44.71 1302.03      45 1340.69   44.41 1376.39   47.27
 1396.47   46.96 1418.17   44.25 1497.03    43.8 1584.16   44.09 1703.39   44.34
#Mann= 16 ,-1 , 0
       0    .016       0   17.03      99       0  162.03    .016       0
  197.03      99       0  387.03    .013       0  417.03      99       0
  427.03    .016       0  682.03      99       0  787.03    .016       0
  832.69    .011       0  863.89    .013       0  887.03      99       0
 1247.03    .013       0 1302.03      99       0 1497.03    .013       0
 1584.16      99       0
#XS Ineff= 7 ,-1
   17.03  162.03      60  197.03  387.03      60  417.03  427.03      60
  682.03  787.03      60  887.03 1247.03      60 1302.03 1497.03      60
 1584.16 1703.39      60
Permanent Ineff=
       F       F       F       F       F       F       F
#Block Obstruct= 7 ,-1
   17.03  162.03      80  197.03  387.03      80  417.03  427.03      80
  682.03  787.03      80  887.03 1247.03      80 1302.03 1497.03      80
 1584.16 1703.39      80
#XS Lid=7
  832.79   46.38   37.01  840.85   46.57   37.01   843.1   46.59   37.01
  846.58   46.53   37.01  853.95    46.4   37.01   858.7   46.34   37.01
  863.79   46.45   37.01
Bank Sta=832.79,863.79
XS Rating Curve= 0 ,0
Exp/Cntr=0.5,0.3

Type RM Length L Ch R = 1 ,3202.396,118.29,85.36,36.8
XS GIS Cut Line= 4
     3111718.012    13825028.783     3111315.832    13824402.086
     3111321.953    13824261.299     3110857.275     13823562.95
#Sta/Elev= 30
       0   43.68   17.24   43.81  162.24   43.65  197.24   43.78  387.24   44.21
  417.03   44.89  427.24   44.83  616.34   47.47  682.24    46.1  787.24   46.52
  806.93   46.37  807.03   46.37  807.03   25.44  822.03   25.44  822.03   36.94
  823.03   36.94  823.03   25.44  838.03   25.44  838.03   45.92  838.13   45.92
  885.57   43.89  907.24    45.4 1125.78   44.83 1147.24    43.7 1287.24    44.8
 1317.24   45.43 1482.79   45.11 1522.24    43.5 1603.68   43.26 1724.38   42.88
#Mann= 18 ,-1 , 0
       0    .016       0   17.24      99       0  162.24    .016       0
  197.24      99       0  387.24    .013       0  417.03      99       0
  427.24    .016       0  682.24      99       0  787.24    .016       0
  806.93    .011       0  838.13     .03       0  885.57    .013       0
  907.24      99       0 1147.24    .016       0 1287.24    .013       0
 1317.24      99       0 1522.24    .013       0 1603.68      99       0
#XS Ineff= 7 ,-1
   17.24  162.24      60  197.24  387.24      60  417.24  427.24      60
  682.24  787.24      60  907.24 1287.24      60 1317.24 1522.24      60
 1603.68 1724.38      60
Permanent Ineff=
       F       F       F       F       F       F       F
#Block Obstruct= 7 ,-1
   17.24  162.24      80  197.24  387.24      80  417.24  427.24      80
  682.24  787.24      80  907.24 1147.24      80 1317.24 1522.24      80
 1603.68 1724.38      80
#XS Lid=6
  807.03   46.37   36.94  816.79   46.05   36.94  821.18   45.91   36.94
  825.98   45.83   36.94   827.7   45.85   36.94  838.03   45.92   36.94
Bank Sta=807.03,838.03
XS Rating Curve= 0 ,0
Exp/Cntr=0.5,0.3

Type RM Length L Ch R = 1 ,3117.041,34.59,34.2,41.51
XS GIS Cut Line= 3
     3111819.375    13824968.213     3111327.959    13824201.815
     3110889.869    13823546.049
#Sta/Elev= 30
       0   43.26   16.99   42.75  161.99    43.6  196.99    43.6  386.99   43.82
  416.99   43.98  426.99    44.3  481.99   45.06  536.99    45.4  566.99   44.46
  646.99   44.82  701.99   45.09  755.77   46.06  755.87   46.06  755.87   25.38
  770.87   25.38  770.87   36.88  771.87   36.88  771.87   25.38  786.87   25.38
  786.87   46.06  786.97   46.06   853.5   46.69  886.99    46.2 1126.99    43.2
 1291.28   44.39 1496.99   43.85 1580.12   43.26 1663.49   42.04 1699.05   42.86
#Mann= 20 ,-1 , 0
       0    .016       0   16.99      99       0  161.99    .016       0
  196.99      99       0  386.99    .013       0  416.99      99       0
  426.99    .016       0  481.99      99       0  536.99    .016       0
  566.99      99       0  646.99    .016       0  701.99      99       0
  755.77    .011       0  786.97     .03       0   853.5    .013       0
  886.99      99       0 1126.99    .013       0 1291.28      99       0
 1496.99    .013       0 1580.12      99       0
#XS Ineff= 9 ,-1
   16.99  161.99      60  196.99  386.99      60  416.99  426.99      60
  481.99  536.99      60  566.99  646.99      60  701.99  755.87      60
  886.99 1126.99      60 1291.28 1496.99      60 1580.12 1699.05      60
Permanent Ineff=
       F       F       F       F       F       F       F       F       F
#Block Obstruct= 9 ,-1
   16.99  161.99      80  196.99  386.99      80  416.99  426.99      80
  481.99  536.99      80  566.99  646.99      80  701.99  755.87      80
  886.99 1126.99      80 1291.28 1496.99      80 1580.12 1699.05      80
#XS Lid=8
  755.87      80   36.88  763.34      80   36.88  765.35      80   36.88
  768.48      80   36.88  781.16      80   36.88  781.57      80   36.88
  786.87      80   36.88  786.87   46.06   36.88
Bank Sta=755.87,786.87
XS Rating Curve= 0 ,0
Exp/Cntr=0.5,0.3

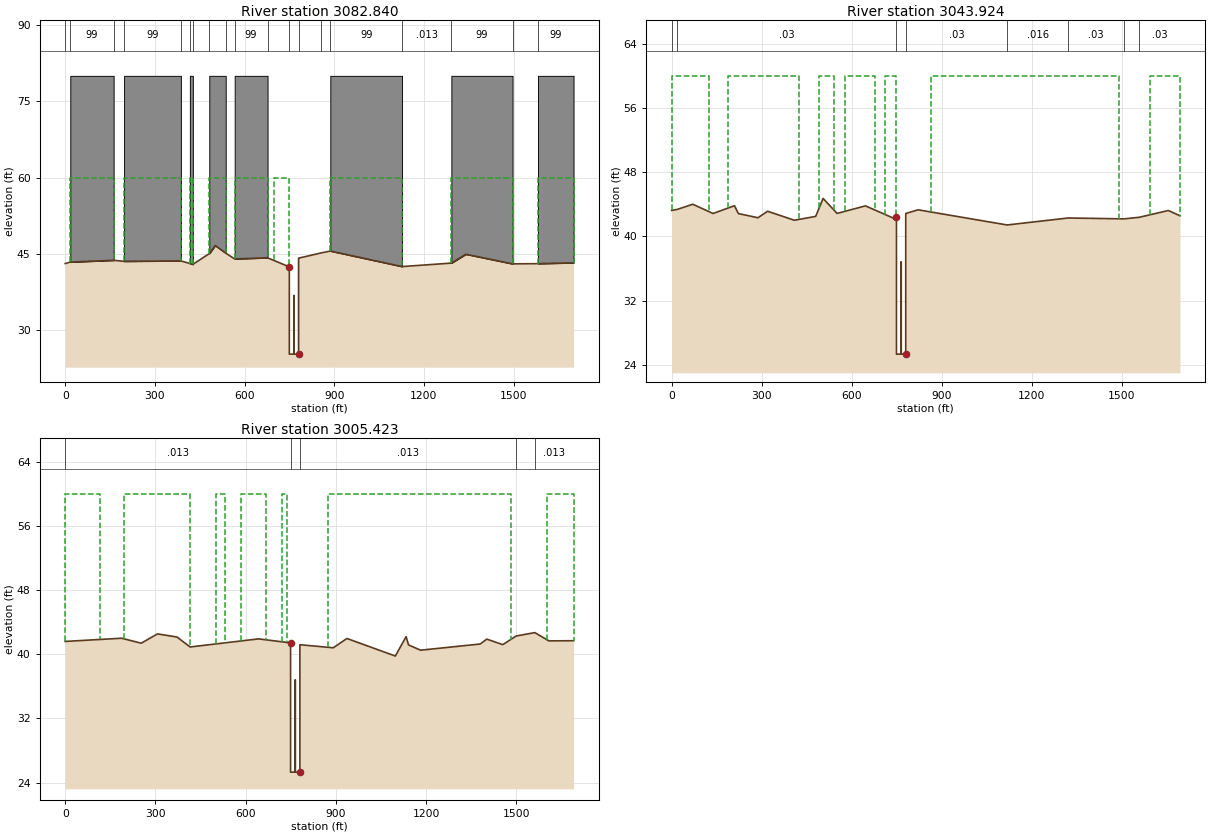
Type RM Length L Ch R = 1 ,3082.840,38.19,38.92,43.4
XS GIS Cut Line= 3
     3111851.514    13824944.726     3111047.909    13823711.727
     3110927.292    13823517.077
#Sta/Elev= 30
       0   43.15   17.01   43.43  162.01   43.78  197.01   43.58  387.01   43.67
  417.01   43.15  427.01   42.98  482.01   45.09  501.97   46.68  537.01   45.19
  567.01   44.05  677.01   44.27  749.74   42.49  749.84   42.49  749.84   25.36
  764.84   25.36  764.84   36.86  765.84   36.86  765.84   25.36  780.84   25.36
  780.84    44.2  780.94    44.2   857.1   45.24  887.01    45.6 1127.01   42.55
 1292.01   43.23 1340.51   44.97 1496.66   43.08  1581.7   43.12 1700.75   43.29
#Mann= 19 ,-1 , 0
       0    .016       0   17.01      99       0  162.01    .016       0
  197.01      99       0  387.01    .013       0  417.01      99       0
  427.01    .016       0  482.01      99       0  537.01    .016       0
  567.01      99       0  677.01    .016       0  749.74    .011       0
  780.94     .03       0   857.1    .013       0  887.01      99       0
 1127.01    .013       0 1292.01      99       0 1496.66    .013       0
  1581.7      99       0
#XS Ineff= 9 ,-1
   17.01  162.01      60  197.01  387.01      60  417.01  427.01      60
  482.01  537.01      60  567.01  677.01      60  697.31  749.74      60
  887.01 1127.01      60 1292.01 1496.66      60  1581.7 1700.75      60
Permanent Ineff=
       F       F       F       F       F       F       F       F       F
#Block Obstruct= 8 ,-1
   17.01  162.01      80  197.01  387.01      80  417.01  427.01      80
  482.01  537.01      80  567.01  677.01      80  887.01 1127.01      80
 1292.01 1496.66      80  1581.7 1700.75      80
#XS Lid=5
  749.84   42.49   36.86  756.89   42.26   36.86   763.6    42.5   36.86
   774.8   43.21   36.86  780.84    44.2   36.86
Bank Sta=749.84,780.84
XS Rating Curve= 0 ,0
Exp/Cntr=0.9,0.9

Type RM Length L Ch R = 1 ,3043.924,38.52,38.5,34.31
XS GIS Cut Line= 3
     3111877.473    13824924.948     3111014.199    13823576.887
     3110962.301    13823498.968
#Sta/Elev= 30
       0   43.23   16.94   43.34   70.45      44  137.87   42.85  209.35   43.82
   222.4   42.84  287.55   42.32  319.82   43.13  408.88   42.01  480.13   42.49
  504.72   44.73  551.38   42.86  645.88    43.8  749.13   42.11  749.23   42.44
  749.23   25.33  764.23   25.33  764.23   36.83  765.23   36.83  765.23   25.33
  780.23   25.33  780.23   42.85  780.33   42.85  821.28   43.31 1118.31   41.42
 1321.64   42.29 1508.02   42.18 1558.85   42.38 1655.52   43.22  1694.4   42.57
#Mann= 8 ,-1 , 0
       0    .016       0   16.94     .03       0  749.13    .011       0
  780.33     .03       0 1118.31    .016       0 1321.64     .03       0
 1508.02    .013       0 1558.85     .03       0
#XS Ineff= 7 ,-1
       0   125.5      60  186.38   423.6      60  491.38  542.21      60
   576.1  677.76      60  711.65  749.13      60  864.15 1491.08      60
 1592.74  1694.4      60
Permanent Ineff=
       F       F       F       F       F       F       F
#XS Lid=8
  749.23   42.44   36.83  747.31   42.44   36.83  764.18   42.74   36.83
  765.12   42.75   36.83  765.33   42.75   36.83  765.65   42.75   36.83
  776.18   42.73   36.83  780.23   42.85   36.83
Bank Sta=749.23,780.23
XS Rating Curve= 0 ,0
Exp/Cntr=0.5,0.3

Type RM Length L Ch R = 1 ,3005.423,33.27,50.72,65.89
XS GIS Cut Line= 3
      3111913.32    13824901.462     3111149.038    13823724.692
     3110994.896    13823482.068
#Sta/Elev= 30
       0    41.6  187.66      42  252.72   41.38  306.93   42.54  371.99   42.15
  415.37   40.91  643.08   41.92  749.41   41.42  749.51   41.42  749.51   25.31
  764.51   25.31  764.51   36.81  765.51   36.81  765.51   25.31  780.51   25.31
  780.51   41.19  780.61   41.19  891.58   40.81  937.04   41.97 1098.01   39.78
 1133.78    42.2 1141.88   41.17 1181.89   40.51 1380.44   41.28 1402.07   41.89
 1455.39    41.2 1499.92   42.28 1562.02    42.7  1608.6   41.67 1690.63   41.69
#Mann= 5 ,-1 , 0
       0    .013       0  749.41    .011       0  780.61    .013       0
 1499.92    .013       0 1562.02    .013       0
#XS Ineff= 7 ,-1
       0   115.5      60  196.38   413.6      60  501.38  532.21      60
   586.1  667.76      60  721.65  739.13      60  874.15 1481.08      60
 1602.74  1694.4      60
Permanent Ineff=
       F       F       F       F       F       F       F
#XS Lid=5
  749.51   41.42   36.81   756.4   41.63   36.81   768.8    41.3   36.81
   773.2   41.27   36.81  780.51   41.19   36.81
Bank Sta=749.51,780.51
XS Rating Curve= 0 ,0
Exp/Cntr=0.5,0.3

River Reach=D109-01-99      ,D109-01-99_0001
Reach XY= 30
     3113989.918    13828819.014     3113954.811    13828771.773
     3113932.073    13828741.173     3113903.669    13828702.951
     3113858.309    13828650.536     3113855.753    13828647.581
     3113805.707    13828619.897     3113741.819    13828579.434
      3113710.94    13828548.555     3113691.773    13828521.935
     3113682.329     13828492.03     3113678.996    13828481.472
     3113671.542    13828443.139     3113672.478    13828396.773
     3113672.736    13828384.042     3113675.004    13828368.841
      3113682.03    13828321.773     3113682.194    13828320.668
     3113692.599    13828286.616     3113723.813    13828169.328
     3113737.039    13828089.781     3113738.651    13828041.436
     3113696.032    13828009.765     3113660.894     13827982.08
     3113624.691    13827949.071     3113594.876    13827920.322
     3113567.191    13827891.572     3113542.073    13827862.434
     3113540.571    13827860.693     3113512.169    13827818.421

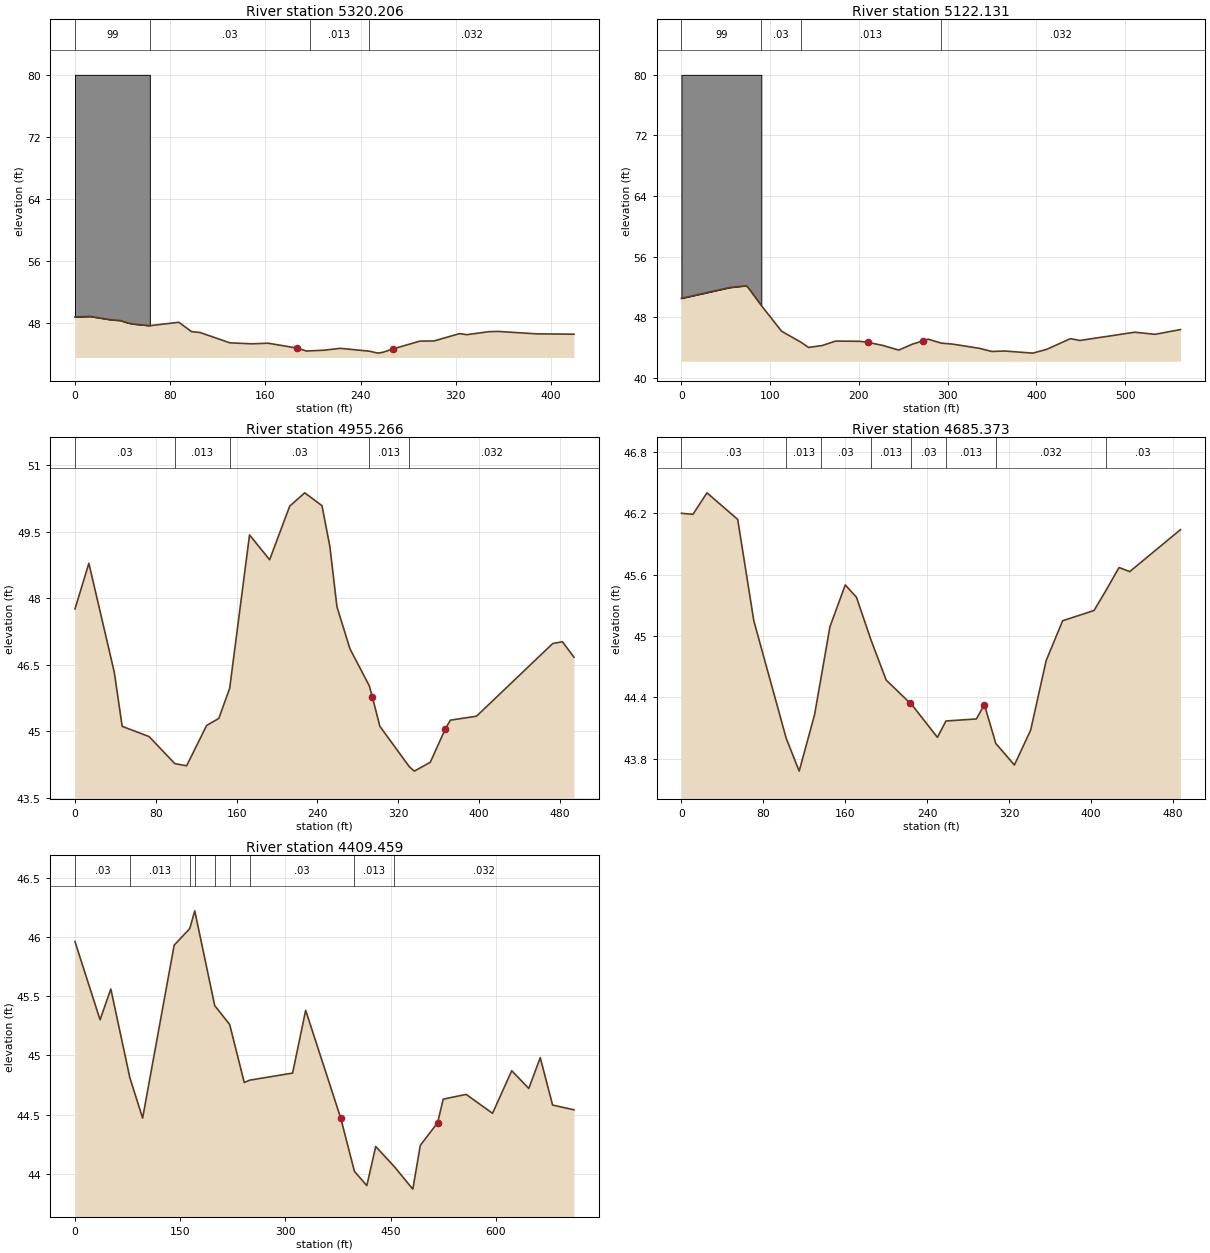
Type RM Length L Ch R = 1 ,5320.206,218.71,198.07,187.86
XS GIS Cut Line= 2
     3114166.499     13828644.13     3113829.699     13828893.91
#Sta/Elev= 30
       0   48.77   12.83   48.83   30.41   48.39   38.01   48.31   44.37   47.99
   49.09   47.85    62.9   47.64   87.26   48.08   97.98   46.87  105.11   46.76
  130.15   45.43  148.26    45.3  162.32   45.38  186.59   44.75  194.49   44.37
  197.08   44.39  209.57   44.48  222.96   44.72   247.4   44.35  254.51    44.1
  258.82   44.21  267.52   44.66  289.82   45.65  301.71   45.67  323.16   46.62
  329.21   46.48  347.88   46.87  355.33    46.9   387.5   46.59  419.31   46.54
#Mann= 4 ,-1 , 0
       0      99       0    62.9     .03       0  197.08    .013       0
   247.4    .032       0
#Block Obstruct= 1 ,-1
       0    62.9      80
Bank Sta=186.59,267.52
XS Rating Curve= 0 ,0
Exp/Cntr=0.8,0.6

Type RM Length L Ch R = 1 ,5122.131,154.98,166.86,177.57
XS GIS Cut Line= 6
     3114039.221    13828508.148      3113947.42    13828573.243
     3113887.333    13828583.257     3113861.516    13828604.686
     3113813.885    13828691.745     3113626.953    13828867.004
#Sta/Elev= 30
       0   50.51   54.56   51.94   72.28   52.16   73.72   52.09   76.19   51.77
      90   49.57  112.89   46.17     135    44.7   143.3   44.03  158.51   44.28
  173.79   44.87  200.99   44.84  209.81   44.71  226.48   44.31  244.97   43.68
  260.68   44.48  272.24    44.9  278.13   45.12  292.49   44.61  306.24   44.46
  335.52   43.92  349.85    43.5  364.14   43.56  395.98   43.28  411.53   43.77
  438.43   45.19  449.04   44.95  510.97   46.04  533.94   45.76  562.48   46.39
#Mann= 4 ,-1 , 0
       0      99       0      90     .03       0     135    .013       0
  292.49    .032       0
#Block Obstruct= 1 ,-1
       0      90      80
Bank Sta=209.81,272.24
XS Rating Curve= 0 ,0
Exp/Cntr=0.5,0.3

Type RM Length L Ch R = 1 ,4955.266,246.46,269.89,287.37
XS GIS Cut Line= 2
     3113957.435    13828326.216     3113584.754    13828650.576
#Sta/Elev= 30
       0   47.76   13.74   48.79   38.93   46.33   46.72   45.11   73.39   44.88
   98.81   44.27  110.52   44.22  130.32   45.13  142.41   45.29  153.17   45.97
  172.82   49.43  192.71   48.87  212.59   50.08  227.47   50.38  244.56   50.09
  252.36   49.17  259.36   47.81  272.25   46.86   291.5   46.02  294.46   45.77
  301.89   45.11  331.02    44.2  335.95    44.1  351.79    44.3   366.6   45.05
  371.68   45.25  397.58   45.34  473.04   46.98  482.64   47.02  494.07   46.67
#Mann= 5 ,-1 , 0
       0     .03       0   98.81    .013       0  153.17     .03       0
   291.5    .013       0  331.02    .032       0
Bank Sta=294.46,366.6
XS Rating Curve= 0 ,0
Exp/Cntr=0.5,0.3

Type RM Length L Ch R = 1 ,4685.373,304.58,275.91,238.68
XS GIS Cut Line= 3
     3113957.006    13828275.101     3113636.902    13828285.879
     3113475.066    13828327.885
#Sta/Elev= 30
       0    46.2   11.23   46.19   24.95    46.4   54.96   46.14   70.68   45.15
  102.37      44     115   43.68  130.01   44.23   136.5    44.6  145.02   45.09
  160.02    45.5  170.95   45.38  185.24   44.96  199.99   44.57  222.78   44.35
  224.24   44.34  250.07   44.01  258.37   44.17  288.12   44.19   295.9   44.33
  307.11   43.95  325.27   43.74  341.11   44.08  356.27   44.76  372.39   45.15
  403.06   45.25  414.36   45.44  427.51   45.67  437.91   45.63  487.48   46.04
#Mann= 8 ,-1 , 0
       0     .03       0  102.37    .013       0   136.5     .03       0
  185.24    .013       0  224.24     .03       0  258.37    .013       0
  307.11    .032       0  414.36     .03       0
Bank Sta=222.78,295.9
XS Rating Curve= 0 ,0
Exp/Cntr=0.8,0.6

Type RM Length L Ch R = 1 ,4409.459,340.81,346.48,355.88
XS GIS Cut Line= 4
     3113952.428    13828029.117      3113743.79    13827997.404
     3113672.019    13828067.506     3113331.523    13828277.812
#Sta/Elev= 30
       0   45.96   35.76    45.3    51.1   45.56   78.27   44.81   96.45   44.47
  141.41   45.93  163.66   46.07  170.78   46.22  199.24   45.42  220.59   45.26
  241.39   44.77  249.05   44.79  310.31   44.85  328.95   45.38  378.92   44.47
  398.48   44.02  416.14    43.9  428.83   44.23   455.4   44.06  481.73   43.87
  492.44   44.24  516.99   44.43  525.13   44.63  557.83   44.67  595.41   44.51
  622.77   44.87  647.09   44.72  663.46   44.98  681.05   44.58  711.57   44.54
#Mann= 9 ,-1 , 0
       0     .03       0   78.27    .013       0  163.66    .025       0
  170.78    .013       0  199.24    .025       0  220.59    .013       0
  249.05     .03       0  398.48    .013       0   455.4    .032       0
Bank Sta=378.92,516.99
XS Rating Curve= 0 ,0
Exp/Cntr=0.8,0.6

River Reach=D109-01-99      ,D109-01-99_0002
Reach XY= 30
     3113512.169    13827818.421     3113462.083    13827741.818
     3113369.275    13827591.557       3113329.5    13827529.685
      3113202.81    13827351.435     3113112.948    13827215.906
     3113102.636    13827179.078     3113092.324    13827124.571
     3113093.319     13827087.77     3113080.539    13827053.861
     3113056.969    13827009.666     3113002.462    13826925.697
     3112970.053    13826874.137     3112927.332    13826810.792
     3112871.353    13826716.511     3112822.739    13826626.649
     3112787.384    13826557.412     3112745.863    13826454.518
     3112703.346    13826337.596     3112589.081    13825986.831
     3112551.681    13825890.078     3112503.067    13825779.593
      3112429.41    13825636.698     3112402.894    13825591.031
     3112318.924    13825456.975     3112290.935    13825415.727
     3112259.999    13825367.113     3112221.697     13825309.66
     3112196.654    13825274.305     3112181.922    13825255.154