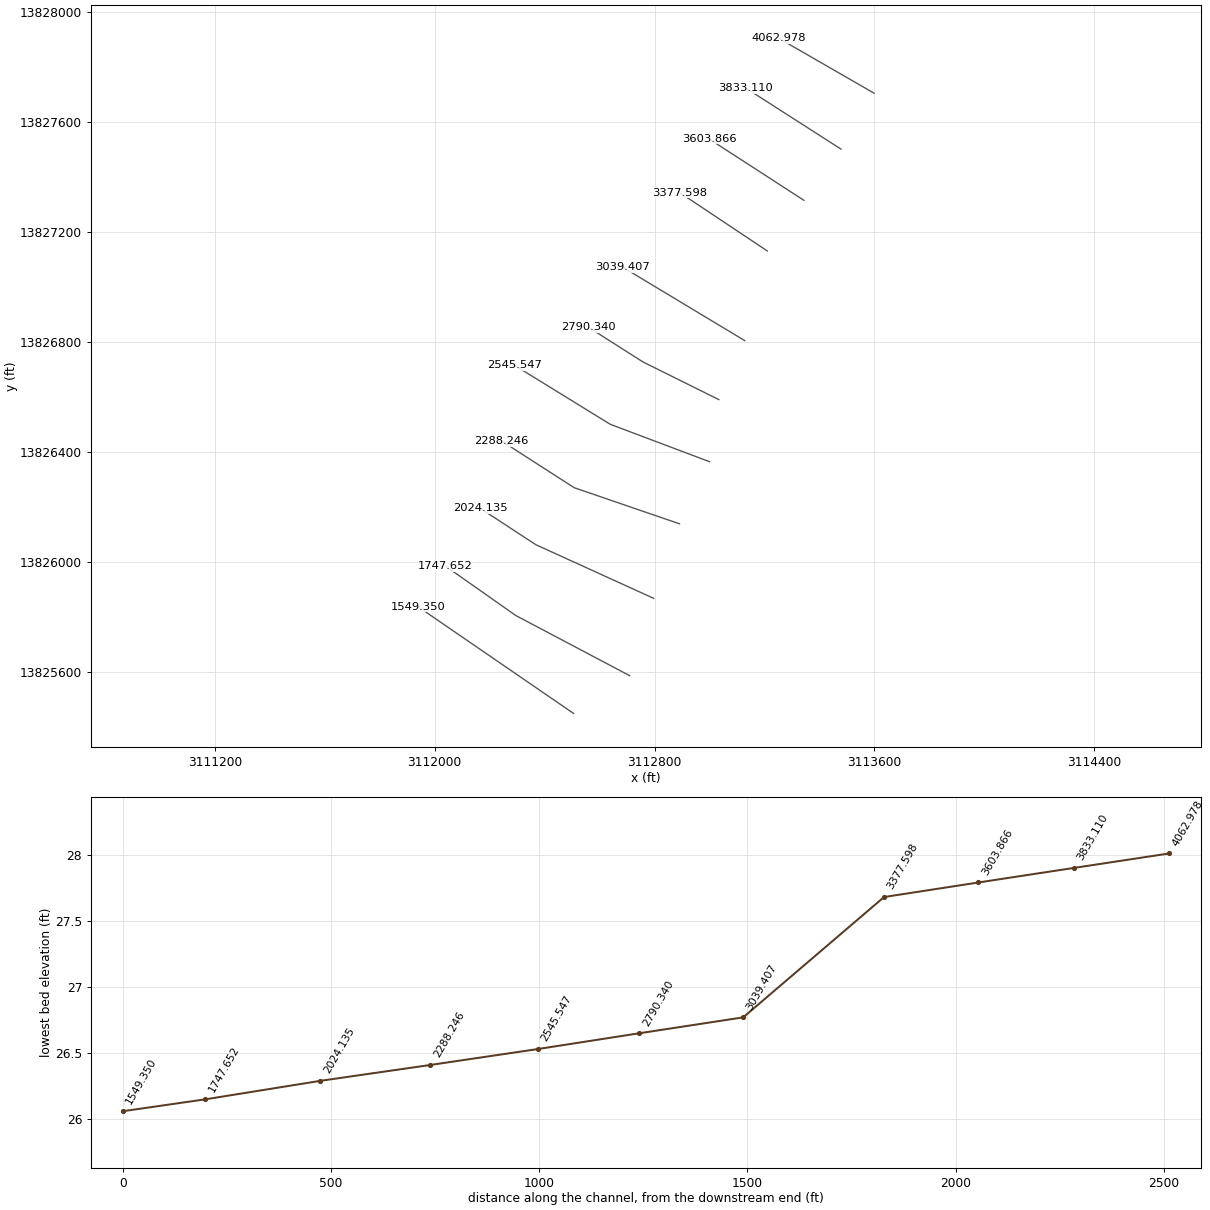
HEC-RAS study D109-00-00.prj: D109-00-00

--- D109-00-00.g01 (geometry) --- (continued)

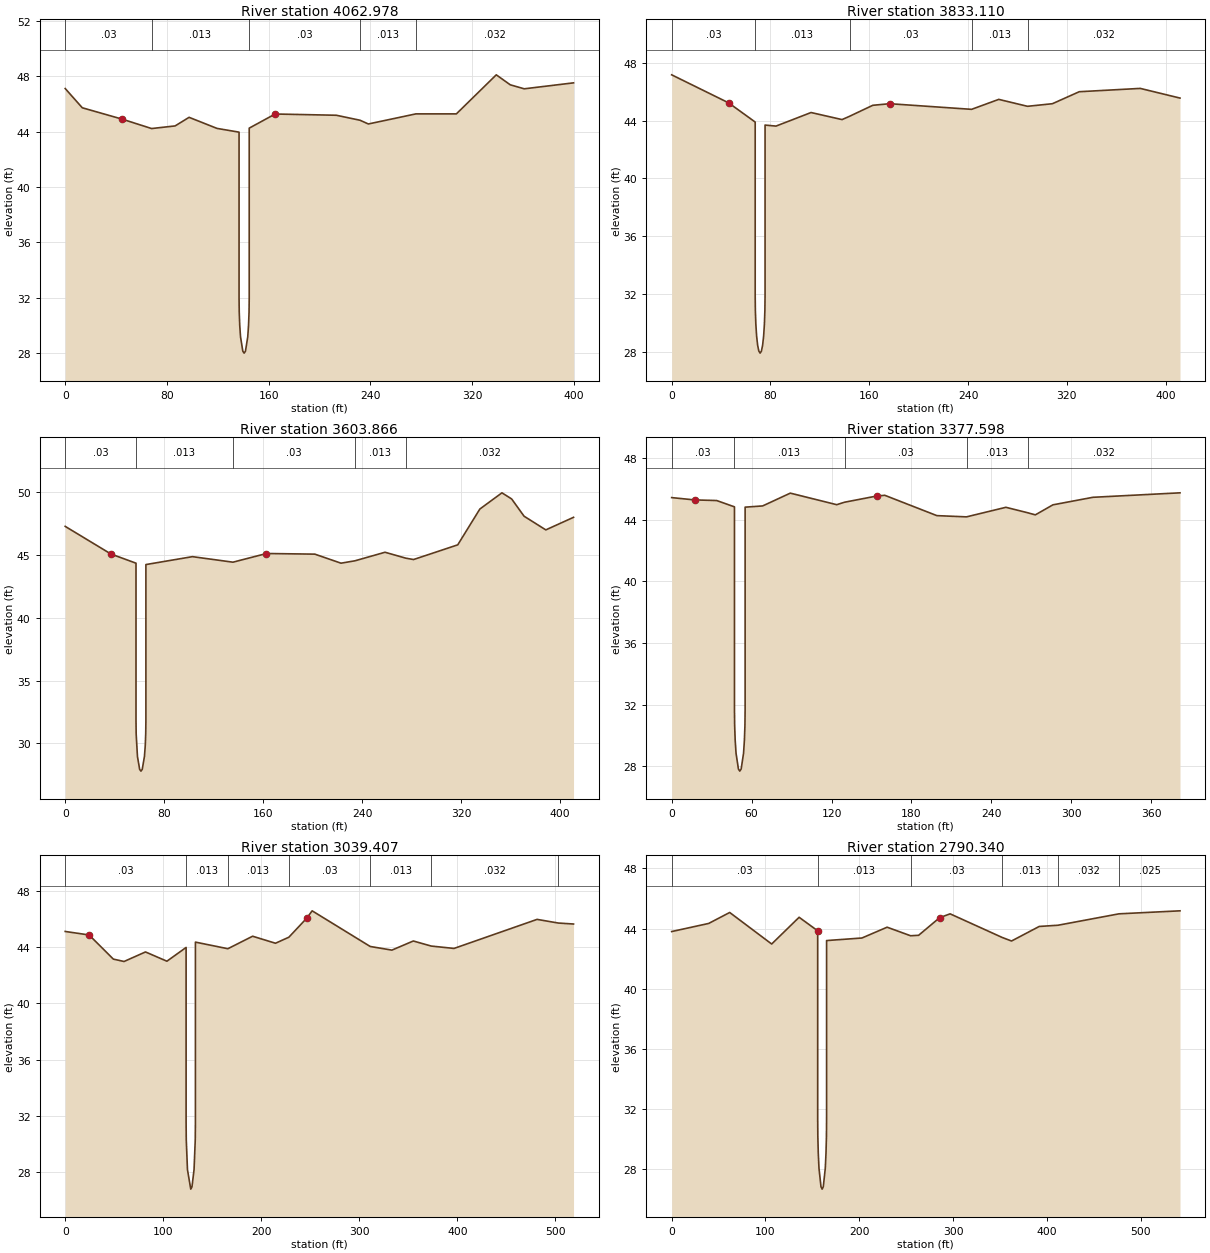
Type RM Length L Ch R = 1 ,4062.978,234.46,229.87,229.09
XS GIS Cut Line= 2
     3113598.707     13827705.32     3113252.239    13827904.916
#Sta/Elev= 30
       0   47.12   13.43   45.73   44.78   44.91   67.97   44.23   86.47   44.42
   97.45   45.04  119.42   44.24  136.75   43.97  136.75   32.01  136.89   30.97
  137.29   30.01  137.92   29.18  139.71   28.15  140.75   28.01  141.79   28.15
  143.58   29.18  144.21   30.01  144.61   30.97  144.75   32.01  144.75   44.26
  165.14   45.28  213.26   45.19   231.9   44.83  238.47   44.56   275.9   45.29
  307.71   45.29  339.09   48.11  350.07   47.39  361.06    47.1  399.85   47.53
#Mann= 5 ,-1 , 0
       0     .03       0   67.97    .013       0  144.75     .03       0
   231.9    .013       0   275.9    .032       0
#XS Lid=13
  136.75   43.97   32.01  136.89   43.97   33.05  137.29   43.99   34.01
  137.92   44.01   34.84  138.75   44.03   35.47  139.71   44.04   35.87
  140.75   44.06   36.01  141.79   44.08   35.87  142.75   44.12   35.47
  143.58   44.15   34.84  144.21   44.18   34.01  144.61   44.22   33.05
  144.75   44.26   32.01
Bank Sta=44.78,165.14
XS Rating Curve= 0 ,0
Exp/Cntr=0.8,0.6

Type RM Length L Ch R = 1 ,3833.110,229.68,229.24,228.98
XS GIS Cut Line= 2
     3113478.196    13827501.959     3113131.728     13827724.15
#Sta/Elev= 30
       0   47.17    46.1   45.23   67.62    43.9   67.62    31.9   67.76   30.86
   68.16    29.9   68.79   29.07   69.62   28.44   70.58   28.04   71.62    27.9
   72.66   28.04   73.62   28.44   74.45   29.07   75.08    29.9   75.48   30.86
   75.62    31.9   75.62   43.69   84.49   43.62  112.87   44.56  137.95   44.07
  144.06    44.3  162.84   45.06  176.57   45.17  242.84   44.78  264.86   45.47
  288.12   44.99  308.29   45.17  330.01      46   379.4   46.23  411.59   45.56
#Mann= 5 ,-1 , 0
       0     .03       0   67.62    .013       0  144.06     .03       0
  242.84    .013       0  288.12    .032       0
#XS Lid=13
   67.62    43.9    31.9   67.76   43.87   32.94   68.16   43.84    33.9
   68.79   43.81   34.73   69.62   43.78   35.36   70.58   43.76   35.76
   71.62   43.74    35.9   72.66   43.72   35.76   73.62    43.7   35.36
   74.45    43.7   34.73   75.08   43.69    33.9   75.48   43.69   32.94
   75.62   43.69    31.9
Bank Sta=46.1,176.57
XS Rating Curve= 0 ,0
Exp/Cntr=0.5,0.3

Type RM Length L Ch R = 1 ,3603.866,227.26,226.27,225.04
XS GIS Cut Line= 2
     3113343.403     13827315.56     3112998.515    13827538.954
#Sta/Elev= 30
       0   47.27   36.98   45.07   57.23   44.34   57.23   31.79   57.37   30.75
    58.4   28.96   60.19   27.93   61.23   27.79   62.27   27.93   64.06   28.96
   64.69   29.79   65.09   30.75   65.23   31.79   65.23   44.23  102.86   44.86
   135.6   44.42  162.72   45.11  201.78   45.06  222.96   44.34  234.22   44.53
  258.53   45.21  275.31   44.74  281.58   44.63  317.32    45.8  335.19   48.65
  353.06   49.94  360.92   49.45  370.93   48.08  388.51   46.99  410.92   47.99
#Mann= 5 ,-1 , 0
       0     .03       0   57.23    .013       0   135.6     .03       0
  234.22    .013       0  275.31    .032       0
#XS Lid=13
   57.23   44.34   31.79   57.37   44.34   32.83   57.77   44.34   33.79
    58.4   44.33   34.62   59.23   44.32   35.25   60.19   44.31   35.65
   61.23    44.3   35.79   62.27   44.29   35.65   63.23   44.28   35.25
   64.06   44.26   34.62   64.69   44.25   33.79   65.09   44.24   32.83
   65.23   44.23   31.79
Bank Sta=36.98,162.72
XS Rating Curve= 0 ,0
Exp/Cntr=0.5,0.3

Type RM Length L Ch R = 1 ,3377.598,328.14,338.19,330.03
XS GIS Cut Line= 2
     3113210.151    13827131.358     3112892.697    13827342.994
#Sta/Elev= 30
       0   45.43   17.17   45.28   33.75   45.24   47.13   44.83   47.13   31.68
   47.27   30.64   47.67   29.68    48.3   28.85   50.09   27.82   51.13   27.68
   52.17   27.82   53.96   28.85   54.59   29.68   54.99   30.64   55.13   31.68
   55.13   44.81   68.31   44.89   89.05   45.72  123.88   44.97  129.72   45.13
  153.76   45.53  159.94   45.58  199.05   44.26  221.29   44.18  250.84    44.8
  267.07   44.45  272.94   44.31  286.13   44.96   316.2   45.45  381.53   45.74
#Mann= 5 ,-1 , 0
       0     .03       0   47.13    .013       0  129.72     .03       0
  221.29    .013       0  267.07    .032       0
#XS Lid=13
   47.13   44.83   31.68   47.27   44.81   32.72   47.67    44.8   33.68
    48.3   44.79   34.51   49.13   44.79   35.14   50.09   44.79   35.54
   51.13   44.79   35.68   52.17    44.8   35.54   53.13    44.8   35.14
   53.96    44.8   34.51   54.59   44.81   33.68   54.99   44.81   32.72
   55.13   44.81   31.68
Bank Sta=17.17,153.76
XS Rating Curve= 0 ,0
Exp/Cntr=0.8,0.6

Type RM Length L Ch R = 1 ,3039.407,246.44,249.07,256.8
XS GIS Cut Line= 2
     3113127.962    13826805.256     3112683.578    13827072.639
#Sta/Elev= 30
       0   45.13   24.38   44.88   49.11   43.16   60.04   42.99    81.9   43.67
  103.76   43.01  123.35   43.99  123.35   31.52  123.51   30.29  124.74   28.16
   128.1   26.77  129.33   26.93  131.46   28.16  132.69   30.29  132.85   31.52
  132.85   44.37  165.96    43.9   191.2   44.79  214.55   44.29  228.19   44.72
  246.35   46.07  251.96    46.6  311.17   44.06  333.29    43.8  355.15   44.45
  373.41   44.09  396.67   43.92  481.43   45.99  503.07   45.73  518.62   45.66
#Mann= 7 ,-1 , 0
       0     .03       0  123.35    .013       0  165.96    .013       0
  228.19     .03       0  311.17    .013       0  373.41    .032       0
  503.07    .013       0
#XS Lid=13
  123.35   43.99   31.52  123.51   44.03   32.75  123.99   44.07    33.9
  124.74   44.11   34.88  125.73   44.15   35.63  126.87   44.19   36.11
   128.1   44.23   36.27  129.33   44.26   36.11  130.48   44.28   35.63
  131.46    44.3   34.88  132.21   44.32    33.9  132.69   44.34   32.75
  132.85   44.37   31.52
Bank Sta=24.38,246.35
XS Rating Curve= 0 ,0
Exp/Cntr=0.5,0.3

Type RM Length L Ch R = 1 ,2790.340,245.76,244.79,255.1
XS GIS Cut Line= 3
     3113033.813    13826590.596     3112758.064    13826727.402
     3112560.427    13826853.107
#Sta/Elev= 30
       0    43.8   39.48   44.34   61.87   45.07  106.64   42.97   135.9   44.75
   155.7   43.85   155.7    31.4  155.86   30.17  156.34   29.03  157.09   28.04
  159.22   26.81  160.45   26.65  161.68   26.81  163.81   28.04  164.56   29.03
  165.04   30.17   165.2    31.4   165.2    43.2  202.88   43.37  229.75   44.09
  254.76   43.52  263.32   43.55  285.66   44.72   296.9   44.98  352.33   43.41
  362.41   43.17  391.95   44.14  411.96   44.22     477   44.98  542.05   45.18
#Mann= 6 ,-1 , 0
       0     .03       0   155.7    .013       0  254.76     .03       0
  352.33    .013       0  411.96    .032       0     477    .025       0
#XS Lid=13
   155.7   43.85    31.4  155.86   43.77   32.63  156.34    43.7   33.78
  157.09   43.62   34.76  158.08   43.55   35.51  159.22   43.47   35.99
  160.45    43.4   36.15  161.68   43.32   35.99  162.83   43.25   35.51
  163.81   43.24   34.76  164.56   43.23   33.78  165.04   43.21   32.63
   165.2    43.2    31.4
Bank Sta=155.7,285.66
XS Rating Curve= 0 ,0
Exp/Cntr=0.5,0.3

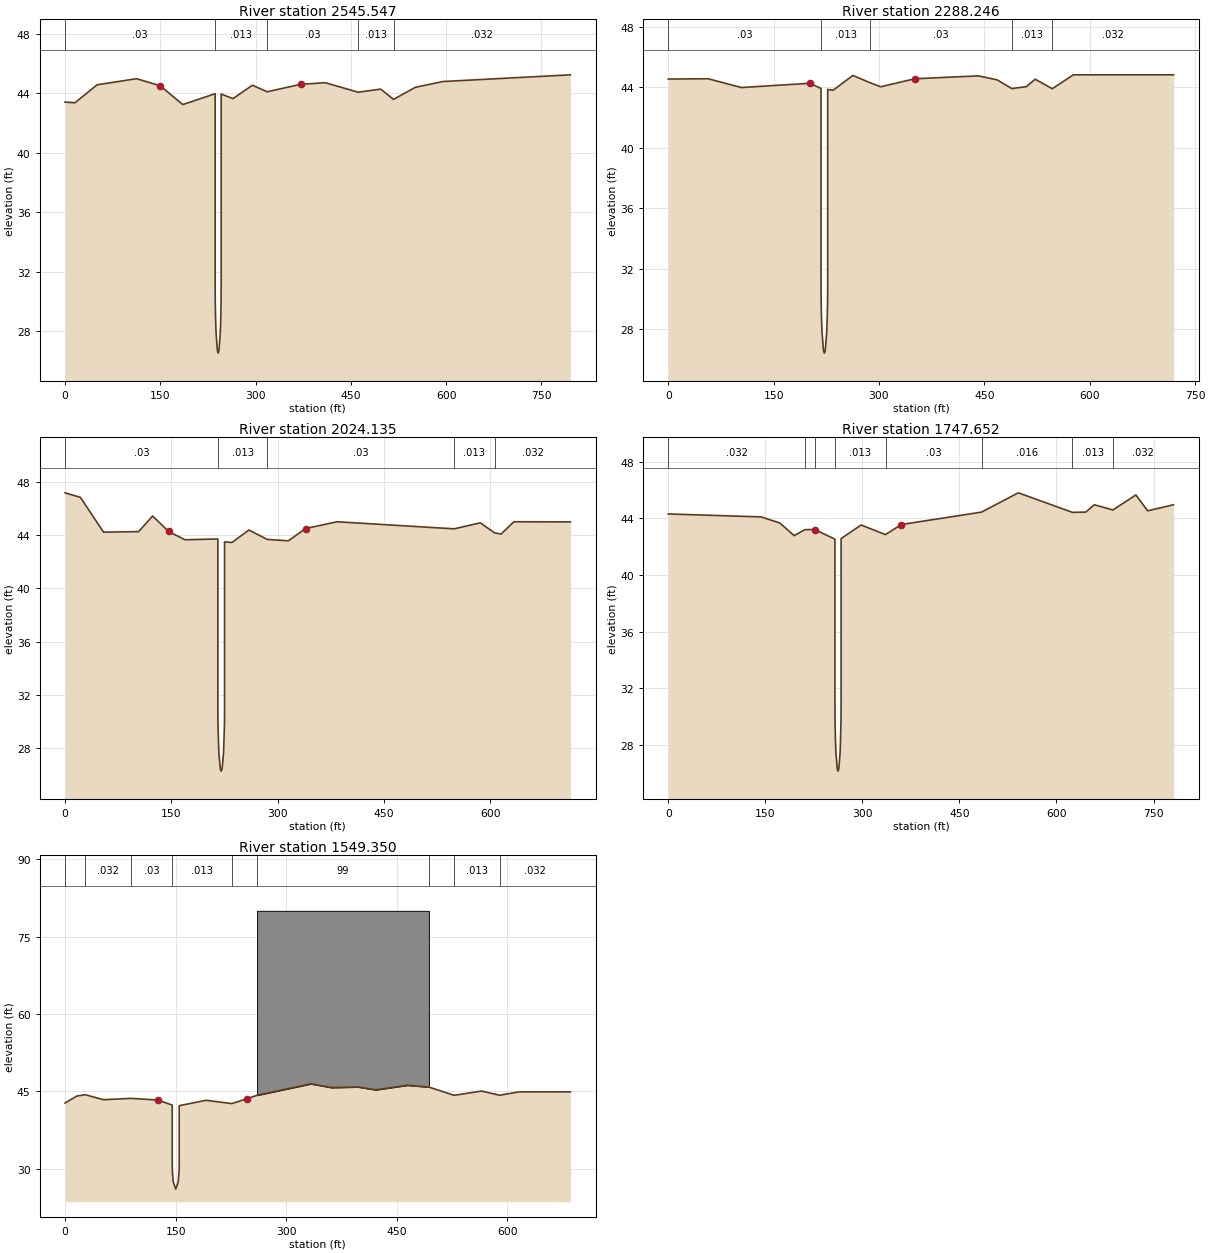
Type RM Length L Ch R = 1 ,2545.547,269.89,257.3,260.55
XS GIS Cut Line= 3
     3112999.919    13826364.638     3112638.878    13826500.647
     3112290.006    13826715.537
#Sta/Elev= 30
       0   43.41   15.51   43.36   50.44   44.57  112.66   44.98  149.56   44.51
  185.34   43.24   236.3   43.97   236.3   31.28  236.46   30.05  236.94   28.91
  237.69   27.92  239.82   26.69  241.05   26.53  242.28   26.69  244.41   27.92
  245.16   28.91  245.64   30.05   245.8   31.28   245.8   43.95   264.3   43.64
  294.94   44.54  318.22    44.1  370.73    44.6  409.74   44.71  461.42   44.07
  496.96   44.28  517.11   43.59  551.47    44.4  595.08   44.79  795.55   45.24
#Mann= 5 ,-1 , 0
       0     .03       0   236.3    .013       0  318.22     .03       0
  461.42    .013       0  517.11    .032       0
#XS Lid=13
   236.3   43.97   31.28  236.46   43.97   32.51  236.94   43.98   33.66
  237.69   43.98   34.64  238.68   43.99   35.39  239.82   43.98   35.87
  241.05   43.98   36.03  242.28   43.97   35.87  243.43   43.97   35.39
  244.41   43.96   34.64  245.16   43.96   33.66  245.64   43.95   32.51
   245.8   43.95   31.28
Bank Sta=149.56,370.73
XS Rating Curve= 0 ,0
Exp/Cntr=0.5,0.3

Type RM Length L Ch R = 1 ,2288.246,278.94,264.11,254.51
XS GIS Cut Line= 3
     3112890.706     13826138.68     3112507.666    13826269.974
     3112243.271    13826440.135
#Sta/Elev= 30
       0   44.54    56.7   44.56  104.27   43.98  201.41   44.26  217.52   43.92
  217.52   31.16  217.68   29.93  218.16   28.79  218.91    27.8  221.04   26.57
  222.27   26.41   223.5   26.57  225.63    27.8  226.38   28.79  226.86   29.93
  227.02   31.16  227.02   43.85   234.8    43.8  262.83   44.78  287.73   44.29
  302.52   44.03  351.04   44.56   441.3   44.75  468.15   44.49  489.15   43.91
  509.87   44.04  522.41   44.53   546.7    43.9  576.68   44.82  719.34   44.82
#Mann= 5 ,-1 , 0
       0     .03       0  217.52    .013       0  287.73     .03       0
  489.15    .013       0   546.7    .032       0
#XS Lid=13
  217.52   43.92   31.16  217.68   43.91   32.39  218.16    43.9   33.54
  218.91   43.89   34.52   219.9   43.88   35.27  221.04   43.88   35.75
  222.27   43.87   35.91   223.5   43.87   35.75  224.65   43.87   35.27
  225.63   43.86   34.52  226.38   43.86   33.54  226.86   43.85   32.39
  227.02   43.85   31.16
Bank Sta=201.41,351.04
XS Rating Curve= 0 ,0
Exp/Cntr=0.5,0.3

Type RM Length L Ch R = 1 ,2024.135,285.54,276.48,272.59
XS GIS Cut Line= 3
     3112796.557    13825867.531     3112368.074    13826062.627
     3112165.053    13826195.382
#Sta/Elev= 30
       0   47.16   21.69   46.82   54.37   44.21  103.82   44.25  123.61   45.42
  146.24   44.26  169.25   43.64  215.68    43.7  215.68   31.04  215.84   29.81
  217.07   27.68   219.2   26.45  220.43   26.29  221.66   26.45  223.79   27.68
  225.02   29.81  225.18   31.04  225.18   43.48  235.67   43.44  259.52   44.37
  285.35   43.67  315.13   43.56  339.57   44.48  384.01   44.99   549.3   44.46
  586.13   44.91  606.37   44.16   615.4   44.06  633.53   44.99  713.38   44.98
#Mann= 5 ,-1 , 0
       0     .03       0  215.68    .013       0  285.35     .03       0
   549.3    .013       0  606.37    .032       0
#XS Lid=13
  215.68    43.7   31.04  215.84   43.68   32.27  216.32   43.66   33.42
  217.07   43.63    34.4  218.06   43.61   35.15   219.2   43.59   35.63
  220.43   43.57   35.79  221.66   43.55   35.63  222.81   43.54   35.15
  223.79   43.52    34.4  224.54   43.51   33.42  225.02   43.49   32.27
  225.18   43.48   31.04
Bank Sta=146.24,339.57
XS Rating Curve= 0 ,0
Exp/Cntr=0.5,0.3

Type RM Length L Ch R = 1 ,1747.652,202.92,198.3,188.25
XS GIS Cut Line= 3
     3112709.235    13825586.252     3112295.058    13825804.999
      3112039.42    13825984.762
#Sta/Elev= 30
       0    44.3  143.81   44.09  172.42   43.66   194.7   42.77  210.85   43.19
  226.46    43.2  257.64   42.52  257.64    30.9   257.8   29.67  258.28   28.53
  259.03   27.54  261.16   26.31  262.39   26.15  263.62   26.31  265.75   27.54
  266.98   29.67  267.14    30.9  267.14   42.56     298   43.52  335.79   42.84
     360   43.55  484.16   44.43  541.02   45.79  624.73   44.41  645.33   44.43
  658.43   44.95   687.2   44.58  722.65   45.64  740.99   44.52  780.91   44.95
#Mann= 8 ,-1 , 0
       0    .032       0  210.85    .013       0  226.46     .03       0
  257.64    .013       0  335.79     .03       0  484.16    .016       0
  624.73    .013       0   687.2    .032       0
#XS Lid=13
  257.64   42.52    30.9   257.8   42.51   32.13  258.28   42.51   33.28
  259.03    42.5   34.26  260.02    42.5   35.01  261.16   42.49   35.49
  262.39   42.49   35.65  263.62   42.52   35.49  264.77   42.54   35.01
  265.75   42.56   34.26   266.5   42.56   33.28  266.98   42.56   32.13
  267.14   42.56    30.9
Bank Sta=226.46,360
XS Rating Curve= 0 ,0
Exp/Cntr=0.5,0.3

Type RM Length L Ch R = 1 ,1549.350,238.97,238.81,238.2
XS GIS Cut Line= 2
     3112505.007    13825448.926     3111939.653    13825836.959
#Sta/Elev= 30
       0   42.75   15.69   44.08   27.43   44.36   52.07   43.39   89.14   43.65
  126.17   43.33  145.42   42.35  145.42   30.81  145.58   29.58  146.81   27.45
  150.17   26.06  153.53   27.45  154.76   29.58  154.92   30.81  154.92   42.23
  191.31   43.28  226.28   42.64  247.54   43.61  260.57   44.25  333.53   46.46
  361.36   45.74  397.75   45.85  421.57    45.3  464.49   46.19  493.71   45.84
  527.99   44.24  565.16   45.07  589.71   44.26  616.06   44.91  685.71   44.91
#Mann= 9 ,-1 , 0
       0    .013       0   27.43    .032       0   89.14     .03       0
  145.42    .013       0  226.28     .03       0  260.57      99       0
  493.71     .03       0  527.99    .013       0  589.71    .032       0
#Block Obstruct= 1 ,-1
  260.57  493.71      80
#XS Lid=13
  145.42   42.35   30.81  145.58   42.34   32.04  146.06   42.33   33.19
  146.81   42.32   34.17   147.8   42.31   34.92  148.94    42.3    35.4
  150.17   42.29   35.56   151.4   42.28    35.4  152.55   42.27   34.92
  153.53   42.26   34.17  154.28   42.25   33.19  154.76   42.24   32.04
  154.92   42.23   30.81
Bank Sta=126.17,247.54
XS Rating Curve= 0 ,0
Exp/Cntr=0.8,0.6