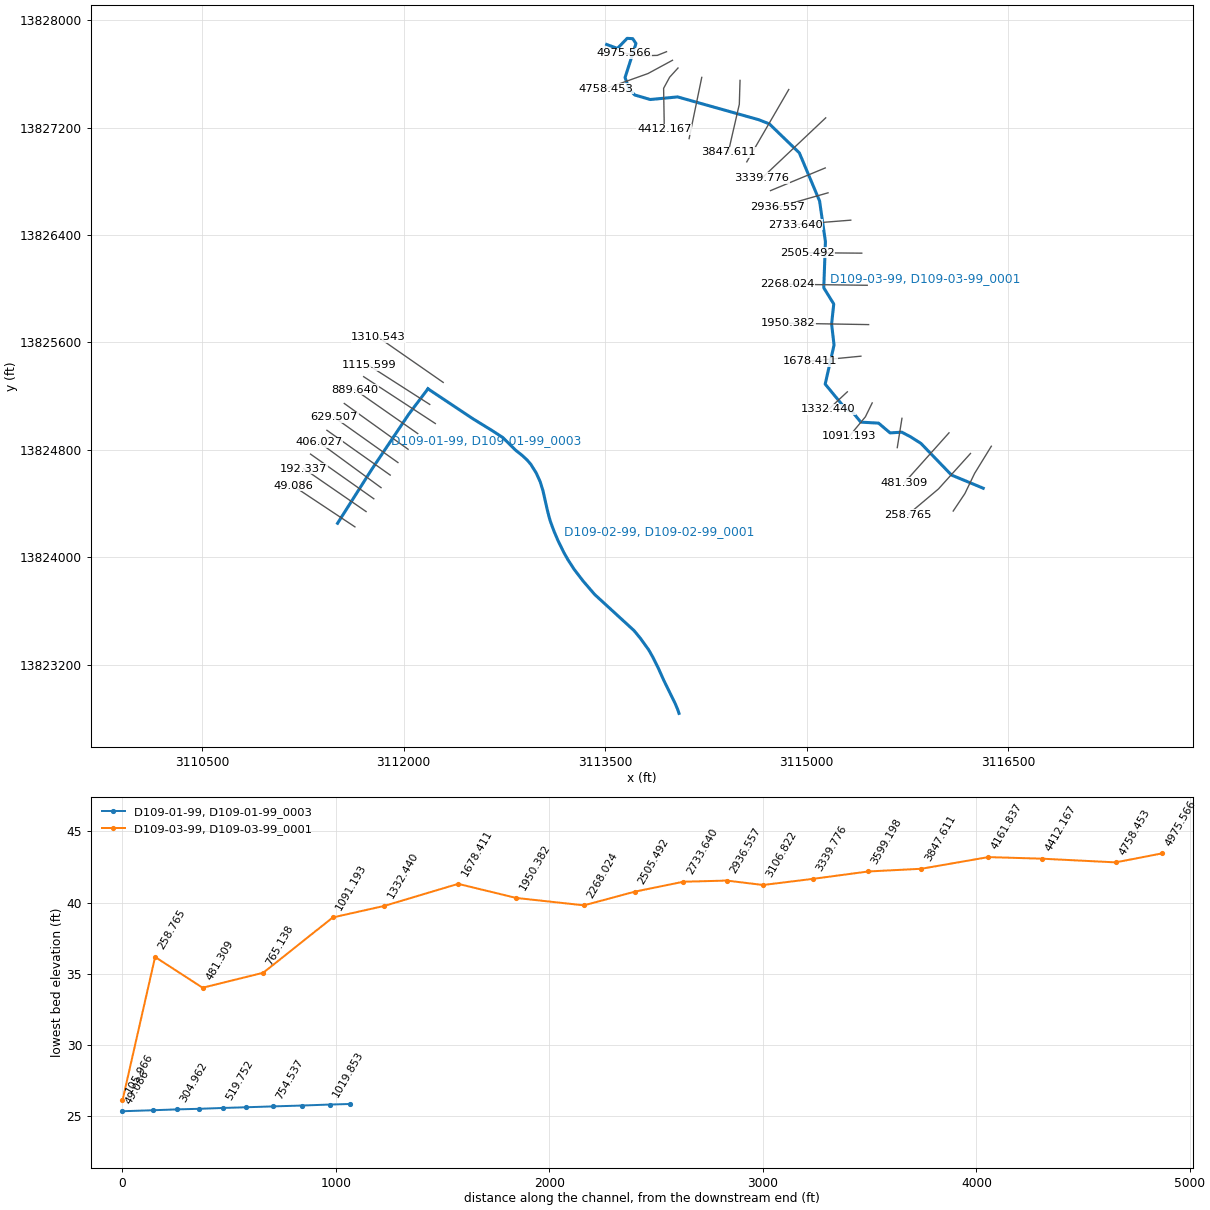
HEC-RAS study D109-00-00.prj: D109-00-00

--- D109-00-00.g01 (geometry) --- (continued)

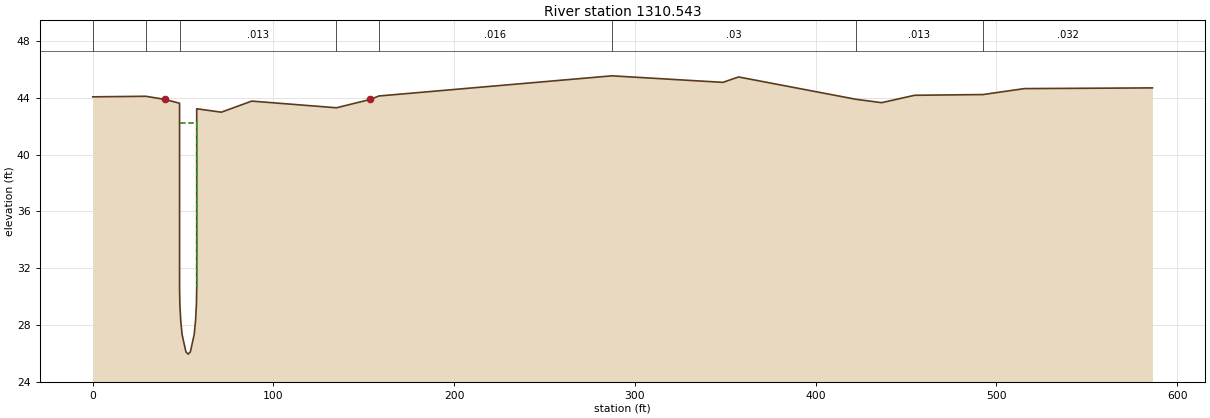
Type RM Length L Ch R = 1 ,1310.543,193.58,194.94,198.02
XS GIS Cut Line= 2
     3112295.498    13825302.798      3111814.02    13825637.424
#Sta/Elev= 30
       0   44.07   29.32   44.11   39.87   43.89   48.02   43.62   48.02    30.7
   48.18   29.47   48.66   28.33   49.41   27.34   51.54   26.11   52.77   25.95
      54   26.11   56.13   27.34   56.88   28.33   57.36   29.47   57.52    30.7
   57.52   43.23   71.15   42.99   87.94   43.77  134.86    43.3  153.62   43.89
  158.31   44.13  287.31   45.55  348.65   45.09  357.36   45.47  422.17    43.9
  436.49   43.66  454.75   44.18  492.53   44.23  515.51   44.65  586.34    44.7
#Mann= 8 ,-1 , 0
       0    .032       0   29.32     .03       0   48.02    .013       0
  134.86     .03       0  158.31    .016       0  287.31     .03       0
  422.17    .013       0  492.53    .032       0
#XS Ineff= 1 ,-1
   48.02   57.52   42.23
Permanent Ineff=
       F
#XS Lid=13
   48.02   43.62    30.7   48.18    43.6   31.93   48.66   43.58   33.08
   49.41   43.56   34.06    50.4   43.53   34.81   51.54   43.51   35.29
   52.77   43.49   35.45      54   43.42   35.29   55.15   43.36   34.81
   56.13   43.29   34.06   56.88   43.27   33.08   57.36   43.25   31.93
   57.52   43.23    30.7
Bank Sta=39.87,153.62
XS Rating Curve= 0 ,0
Exp/Cntr=0.8,0.6

River Reach=D109-01-99      ,D109-01-99_0003
Reach XY= 30
     3112181.922    13825255.154      3112130.19    13825186.773
     3112102.073    13825149.605     3112096.147    13825141.773
     3112087.073    13825129.777     3112085.778    13825128.067
     3112039.512    13825066.909      3112039.42    13825066.773
     3112012.073    13825026.012     3112009.228    13825021.773
     3111937.073    13824914.228     3111918.651    13824886.773
     3111877.073    13824824.801     3111868.331    13824811.773
     3111862.073    13824802.444     3111858.267    13824796.773
     3111832.073    13824757.731     3111819.924    13824739.625
     3111817.073    13824735.374     3111762.608    13824654.197
     3111607.073    13824408.886     3111605.732    13824406.773
     3111592.073    13824385.228     3111586.711    13824376.773
     3111563.336    13824339.904     3111548.669    13824316.773
     3111547.073    13824314.254     3111529.648    13824286.773
     3111524.769    13824279.076     3111509.049    13824254.283

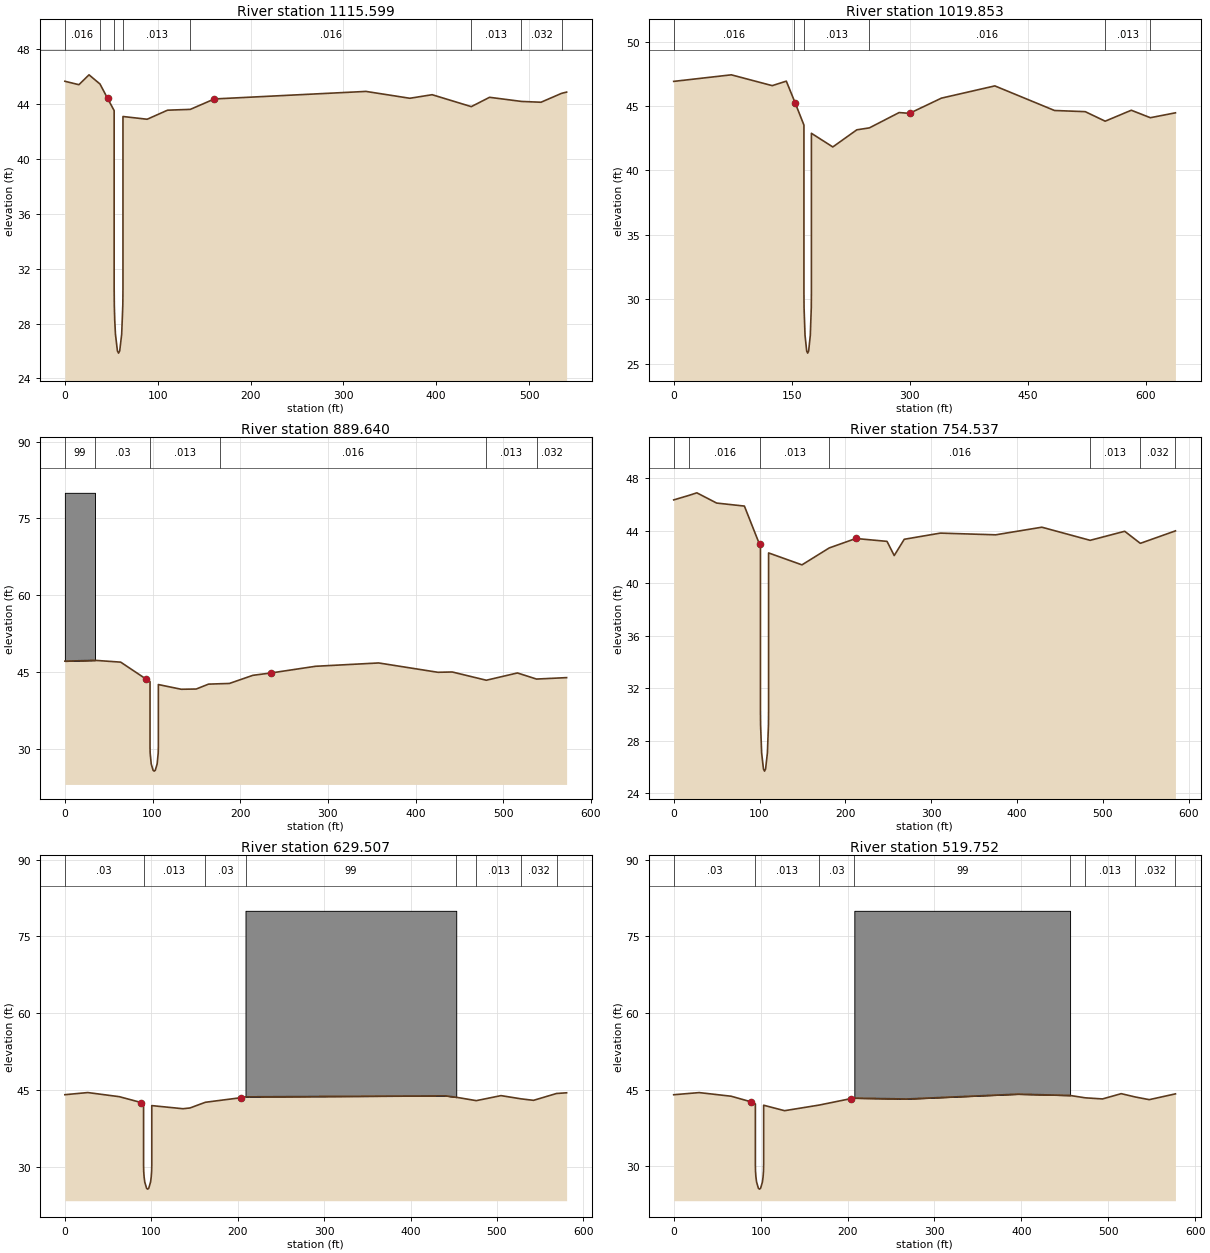
Type RM Length L Ch R = 1 ,1115.599,95.92,95.75,98.28
XS GIS Cut Line= 2
     3112195.169    13825138.961     3111740.118      13825430.5
#Sta/Elev= 30
       0   45.68   15.13   45.43   25.99   46.15   37.83   45.48   45.94   44.44
   53.08   43.54   53.08    30.6   53.24   29.37   53.72   28.23   54.47   27.24
    56.6   26.01   57.83   25.85   59.06   26.01   61.19   27.24   62.42   29.37
   62.58    30.6   62.58   43.11   88.63   42.91  110.56   43.57  135.11   43.63
  161.05   44.39  324.34   44.94  371.55   44.44  395.59    44.7  437.75   43.83
  457.45   44.51  491.79   44.21  512.84   44.15  535.03    44.8  540.43   44.89
#Mann= 8 ,-1 , 0
       0    .016       0   37.83     .03       0   53.08    .013       0
   62.58    .013       0  135.11    .016       0  437.75    .013       0
  491.79    .032       0  535.03    .016       0
#XS Lid=13
   53.08   43.54    30.6   53.24   43.47   31.83   53.72   43.41   32.98
   54.47   43.34   33.96   55.46   43.28   34.71    56.6   43.21   35.19
   57.83   43.16   35.35   59.06   43.12   35.19   60.21   43.12   34.71
   61.19   43.11   33.96   61.94   43.11   32.98   62.42   43.11   31.83
   62.58   43.11    30.6
Bank Sta=45.94,161.05
XS Rating Curve= 0 ,0
Exp/Cntr=0.8,0.6

Type RM Length L Ch R = 1 ,1019.853,131.57,130.21,127.17
XS GIS Cut Line= 2
     3112236.867    13824996.725     3111703.168    13825345.513
#Sta/Elev= 30
       0   46.91    73.2   47.42  125.19   46.58  143.11   46.93  153.02   45.44
  154.29   45.25  165.48   43.52  165.48   30.56  165.64   29.33  166.87    27.2
     169   25.97  170.23   25.81  171.46   25.97  173.59    27.2  174.82   29.33
  174.98   30.56  174.98   42.88  202.18   41.82   232.7   43.15  248.65    43.3
  286.46   44.49  299.66   44.43  340.22   45.61  408.08   46.56  483.94   44.65
  522.93   44.56   548.3   43.82  581.47   44.67  605.69   44.09  637.56   44.47
#Mann= 6 ,-1 , 0
       0    .016       0  153.02     .03       0  165.48    .013       0
  248.65    .016       0   548.3    .013       0  605.69    .032       0
#XS Lid=13
  165.48   43.52   30.56  165.64   43.43   31.79  166.12   43.34   32.94
  166.87   43.24   33.92  167.86   43.15   34.67     169   43.06   35.15
  170.23   43.03   35.31  171.46   43.01   35.15  172.61   42.98   34.67
  173.59   42.96   33.92  174.34   42.93   32.94  174.82    42.9   31.79
  174.98   42.88   30.56
Bank Sta=154.29,299.66
XS Rating Curve= 0 ,0
Exp/Cntr=0.5,0.3

Type RM Length L Ch R = 1 ,889.640 ,135.66,135.1,137.7
XS GIS Cut Line= 2
     3112105.877    13824921.983     3111636.656    13825249.441
#Sta/Elev= 30
       0   47.18   34.33   47.34   63.63   46.99   92.12   43.74    97.1    43.2
    97.1   30.49   97.26   29.26   98.49   27.13  100.62    25.9  101.85   25.74
  103.08    25.9  105.21   27.13  106.44   29.26   106.6   30.49   106.6   42.62
  132.68    41.7  149.82   41.75   163.8    42.7  177.38   42.78  187.55   42.83
  214.45   44.42  235.17   44.88  285.84   46.18  357.84   46.83  425.35   45.01
  441.78   45.07  480.64   43.46   516.1   44.88  537.85   43.69  572.19   43.97
#Mann= 6 ,-1 , 0
       0      99       0   34.33     .03       0    97.1    .013       0
  177.38    .016       0  480.64    .013       0  537.85    .032       0
#Block Obstruct= 1 ,-1
       0   34.33      80
#XS Lid=13
    97.1    43.2   30.49   97.26   43.18   31.72   97.74   43.15   32.87
   98.49   43.12   33.85   99.48   43.09    34.6  100.62   43.06   35.08
  101.85   43.03   35.24  103.08      43   35.08  104.23   42.92    34.6
  105.21   42.84   33.85  105.96   42.77   32.87  106.44   42.69   31.72
   106.6   42.62   30.49
Bank Sta=92.12,235.17
XS Rating Curve= 0 ,0
Exp/Cntr=0.5,0.3

Type RM Length L Ch R = 1 ,754.537 ,124.99,125.03,125.4
XS GIS Cut Line= 2
     3112033.988    13824805.164     3111559.059    13825145.978
#Sta/Elev= 30
       0   46.35   17.54   46.69   26.97   46.89   50.02   46.11   82.36   45.88
   99.96   42.97  101.06   42.82  101.06   30.43  101.22    29.2  102.45   27.07
  104.58   25.84  105.81   25.68  107.04   25.84  109.17   27.07   110.4    29.2
  110.56   30.43  110.56   42.31  149.43    41.4  181.21   42.69   212.2   43.41
  248.53   43.19  256.92   42.11  268.61   43.35  310.66   43.82  375.16   43.69
   428.9   44.27  485.19   43.27  525.46   43.96  543.64   43.04  584.56   43.99
#Mann= 7 ,-1 , 0
       0     .03       0   17.54    .016       0  101.06    .013       0
  181.21    .016       0  485.19    .013       0  543.64    .032       0
  584.56    .016       0
#XS Lid=13
  101.06   42.82   30.43  101.22   42.75   31.66   101.7   42.68   32.81
  102.45   42.61   33.79  103.44   42.55   34.54  104.58   42.48   35.02
  105.81   42.42   35.18  107.04   42.31   35.02  108.19   42.31   34.54
  109.17   42.31   33.79  109.92   42.31   32.81   110.4   42.31   31.66
  110.56   42.31   30.43
Bank Sta=99.96,212.2
XS Rating Curve= 0 ,0
Exp/Cntr=0.5,0.3

Type RM Length L Ch R = 1 ,629.507 ,109.82,109.75,110.05
XS GIS Cut Line= 2
     3111958.505    13824706.317     3111485.158    13825042.516
#Sta/Elev= 30
       0   44.07   26.52   44.49   63.08   43.68   88.25   42.54   91.05   42.51
   91.05   30.37   91.21   29.14   91.69      28   92.44   27.01   94.57   25.78
    95.8   25.62   97.03   25.78   99.16   27.01   99.91      28  100.39   29.14
  100.55   30.37  100.55   41.94  136.68   41.33  144.79   41.48  162.57   42.59
  204.37    43.5  209.01   43.65  440.49   43.85  452.86   43.57  476.09   42.91
  504.65   43.89  528.34   43.25  542.32   42.97  568.98   44.31  580.59   44.44
#Mann= 8 ,-1 , 0
       0     .03       0   91.05    .013       0  162.57     .03       0
  209.01      99       0  452.86     .03       0  476.09    .013       0
  528.34    .032       0  568.98    .016       0
#Block Obstruct= 1 ,-1
  209.01  452.86      80
#XS Lid=13
   91.05   42.51   30.37   91.21   42.45    31.6   91.69   42.38   32.75
   92.44   42.32   33.73   93.43   42.26   34.48   94.57   42.19   34.96
    95.8   42.13   35.12   97.03   42.06   34.96   98.18      42   34.48
   99.16   41.97   33.73   99.91   41.94   32.75  100.39   41.94    31.6
  100.55   41.94   30.37
Bank Sta=88.25,204.37
XS Rating Curve= 0 ,0
Exp/Cntr=0.5,0.3

Type RM Length L Ch R = 1 ,519.752 ,119.52,113.72,112.6
XS GIS Cut Line= 2
     3111900.994    13824612.861     3111429.731    13824946.444
#Sta/Elev= 30
       0   44.03   29.31   44.45   66.06   43.74   88.92   42.65   93.98   42.23
   93.98   30.32   94.14   29.09   94.62   27.95   95.37   26.96    97.5   25.73
   98.73   25.57   99.96   25.73  102.09   26.96  102.84   27.95  103.32   29.09
  103.48   30.32  103.48   41.98  127.57   40.91  167.44   42.01  204.39   43.29
  207.86   43.37  268.22    43.2  396.21   44.15  456.13   43.89  473.45   43.43
  493.44   43.21  514.96   44.24  531.19   43.59  547.24   43.07  577.38    44.2
#Mann= 8 ,-1 , 0
       0     .03       0   93.98    .013       0  167.44     .03       0
  207.86      99       0  456.13     .03       0  473.45    .013       0
  531.19    .032       0  577.38    .016       0
#Block Obstruct= 1 ,-1
  207.86  456.13      80
#XS Lid=13
   93.98   42.23   30.32   94.14   42.19   31.55   94.62   42.15    32.7
   95.37   42.12   33.68   96.36   42.11   34.43    97.5   42.09   34.91
   98.73   42.08   35.07   99.96   42.06   34.91  101.11   42.04   34.43
  102.09   42.02   33.68  102.84      42    32.7  103.32   41.99   31.55
  103.48   41.98   30.32
Bank Sta=88.92,204.39
XS Rating Curve= 0 ,0
Exp/Cntr=0.5,0.3

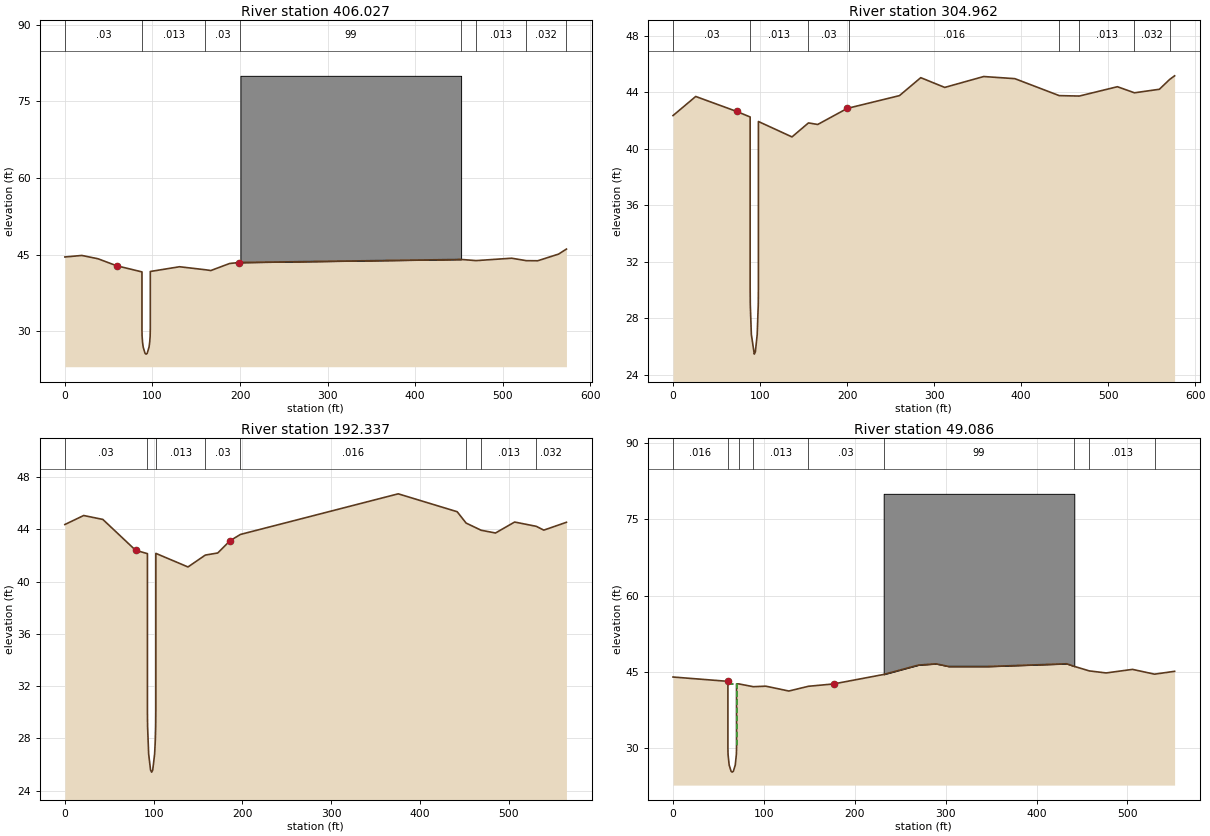
Type RM Length L Ch R = 1 ,406.027 ,100.35,101.07,102.18
XS GIS Cut Line= 2
       3111832.7    13824519.406      3111370.61    13824857.762
#Sta/Elev= 30
       0   44.53   19.37   44.83   37.86   44.18   58.99   42.82   88.03   41.61
   88.03   30.26   88.19   29.03   88.67   27.89   89.42    26.9   91.55   25.67
   92.78   25.51   94.01   25.67   96.14    26.9   96.89   27.89   97.37   29.03
   97.53   30.26   97.53   41.69  130.92   42.62  160.36   42.03  166.71   41.88
  188.17   43.26  199.31   43.45  200.45   43.45  452.45   44.05  469.63   43.82
  510.15   44.29  526.91   43.81  539.92   43.79  563.81    45.1  572.72   46.08
#Mann= 8 ,-1 , 0
       0     .03       0   88.03    .013       0  160.36     .03       0
  200.45      99       0  452.45     .03       0  469.63    .013       0
  526.91    .032       0  572.72    .016       0
#Block Obstruct= 1 ,-1
  200.45  452.45      80
#XS Lid=13
   88.03   41.61   30.26   88.19   41.61   31.49   88.67   41.61   32.64
   89.42    41.6   33.62   90.41   41.58   34.37   91.55   41.57   34.85
   92.78   41.59   35.01   94.01   41.61   34.85   95.16   41.63   34.37
   96.14   41.65   33.62   96.89   41.67   32.64   97.37   41.69   31.49
   97.53   41.69   30.26
Bank Sta=58.99,199.31
XS Rating Curve= 0 ,0
Exp/Cntr=0.5,0.3

Type RM Length L Ch R = 1 ,304.962 ,111.89,112.62,115.33
XS GIS Cut Line= 2
     3111778.783    13824436.734     3111307.794     13824769.08
#Sta/Elev= 30
       0   42.34   26.08   43.69   73.21   42.63   88.63   42.24   88.63   30.22
   88.79   28.99   90.02   26.86   93.38   25.47   94.61   25.63   96.74   26.86
   97.97   28.99   98.13   30.22   98.13   41.92  136.72   40.83  155.64   41.82
  166.29   41.71  200.03   42.84  201.75   42.87  260.24   43.75  284.69   45.02
  312.27   44.33  357.02    45.1  392.85   44.95  443.86   43.75  466.92   43.72
  510.72   44.38  530.33   43.95  558.97    44.2  570.68   44.89  576.44   45.15
#Mann= 8 ,-1 , 0
       0     .03       0   88.63    .013       0  155.64     .03       0
  201.75    .016       0  443.86     .03       0  466.92    .013       0
  530.33    .032       0  570.68    .016       0
#XS Lid=13
   88.63   42.24   30.22   88.79   42.22   31.45   89.27   42.19    32.6
   90.02   42.17   33.58   91.01   42.14   34.33   92.15   42.12   34.81
   93.38   42.09   34.97   94.61   42.07   34.81   95.76   42.04   34.33
   96.74   42.01   33.58   97.49   41.98    32.6   97.97   41.95   31.45
   98.13   41.92   30.22
Bank Sta=73.21,200.03
XS Rating Curve= 0 ,0
Exp/Cntr=0.5,0.3

Type RM Length L Ch R = 1 ,192.337 ,142.32,143.25,144.18
XS GIS Cut Line= 2
     3111721.272    13824341.481     3111256.062    13824661.922
#Sta/Elev= 30
       0   44.37    21.2   45.06   42.77   44.76   79.65    42.4   92.98   42.14
   92.98   30.16   93.14   28.93   94.37    26.8    96.5   25.57   97.73   25.41
   98.96   25.57  101.09    26.8  101.84   27.79  102.32   28.93  102.48   30.16
  102.48   42.16  138.67   41.12  158.17   42.03   172.2   42.19  185.85   43.12
  197.71   43.61  375.45   46.72  441.83   45.35  451.91   44.48  468.86   43.93
  484.97   43.72  506.54   44.56     531   44.23  539.38   43.94  564.89   44.54
#Mann= 8 ,-1 , 0
       0     .03       0   92.98    .013       0  102.48    .013       0
  158.17     .03       0  197.71    .016       0  451.91     .03       0
  468.86    .013       0     531    .032       0
#XS Lid=13
   92.98   42.14   30.16   93.14   42.14   31.39   93.62   42.14   32.54
   94.37   42.15   33.52   95.36   42.15   34.27    96.5   42.15   34.75
   97.73   42.15   34.91   98.96   42.15   34.75  100.11   42.15   34.27
  101.09   42.16   33.52  101.84   42.16   32.54  102.32   42.16   31.39
  102.48   42.16   30.16
Bank Sta=79.65,185.85
XS Rating Curve= 0 ,0
Exp/Cntr=0.8,0.6

Type RM Length L Ch R = 1 ,49.086  ,37.06,49.09,48.77
XS GIS Cut Line= 2
     3111638.261    13824227.424     3111178.466    13824532.594
#Sta/Elev= 30
       0   44.02   60.37   43.17   60.37   30.09   60.53   28.86   61.76   26.73
   63.89    25.5   65.12   25.34   66.35    25.5   68.48   26.73   69.71   28.86
   69.87   30.09   69.87   42.67   72.29   42.67    88.3   42.12  102.16   42.22
  127.45   41.27     149    42.2  176.59   42.66  231.78   44.52  270.07   46.37
  289.48   46.61  303.38   46.09  346.66   46.09  433.23   46.62  441.48   46.11
  458.04   45.22  476.52   44.82  505.52   45.52  529.78   44.58  551.85   45.14
#Mann= 9 ,-1 , 0
       0    .016       0   60.37    .013       0   72.29     .03       0
    88.3    .013       0     149     .03       0  231.78      99       0
  441.48     .03       0  458.04    .013       0  529.78    .032       0
#XS Ineff= 1 ,-1
   60.37   69.87   42.67
Permanent Ineff=
       F
#Block Obstruct= 1 ,-1
  231.78  441.48      80
#XS Lid=13
   60.37   43.17   30.09   60.53   43.15   31.32   61.01    43.1   32.47
   61.76   43.05   33.45   62.75      43    34.2   63.89      43   34.68
   65.12   42.95   34.84   66.35   42.91   34.68    67.5   42.85    34.2
   68.48    42.8   33.45   69.23   42.75   32.47   69.71    42.7   31.32
   69.87    42.7   30.09
Bank Sta=60.37,176.59
XS Rating Curve= 0 ,0
Exp/Cntr=0.8,0.6

River Reach=D109-03-99      ,D109-03-99_0001
Reach XY= 30
     3113512.169    13827818.421     3113592.304    13827789.071
     3113664.986    13827864.176     3113706.172    13827861.753
     3113730.399    13827825.412     3113649.181    13827572.131
     3113679.522    13827486.231     3113720.709    13827442.622
     3113836.999    13827408.704     3114040.508    13827428.086
     3114643.765    13827258.496     3114723.715       13827227.
     3114946.605    13827011.378     3115097.217    13826653.585
     3115140.791    13826350.386     3115128.439    13826007.056
     3115202.727     13825886.55     3115186.755    13825737.478
     3115204.857    13825580.952     3115138.975    13825290.096
     3115288.976     13825108.18     3115342.216    13825082.624
     3115403.975    13825007.023     3115536.584    13824999.605
     3115621.916    13824926.982     3115709.063    13824932.429
     3115774.423    13824897.933     3115851.585    13824848.913
     3116079.171    13824613.203     3116315.445    13824515.085

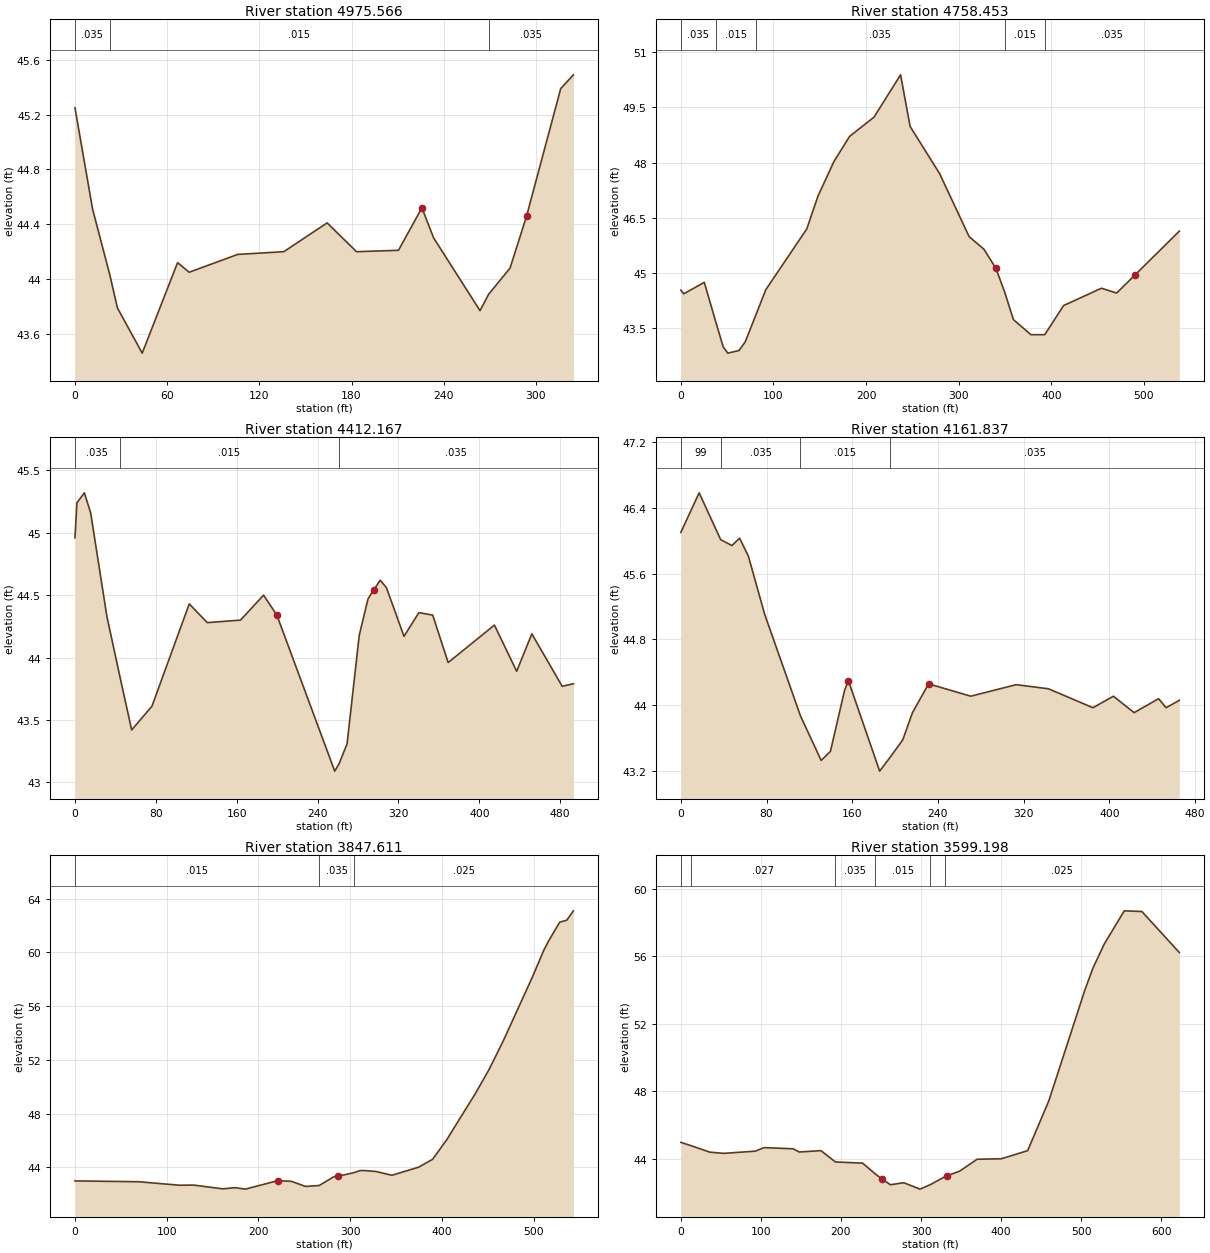
Type RM Length L Ch R = 1 ,4975.566,188.74,217.11,275.18
XS GIS Cut Line= 4
     3113957.739    13827764.657     3113888.705    13827737.193
     3113769.099    13827734.216     3113640.133    13827754.278
#Sta/Elev= 20
       0   45.25   11.48   44.51   22.71   44.03   27.62   43.79   43.77   43.46
   66.79   44.12    74.3   44.05  105.94   44.18  135.95    44.2  164.14   44.41
  183.25    44.2  210.57   44.21  225.82   44.52  233.48    44.3  263.64   43.77
   269.3   43.89  283.19   44.08  293.96   44.46  316.19   45.39  324.46   45.49
#Mann= 3 ,-1 , 0
       0    .035       0   22.71    .015       0   269.3    .035       0
Bank Sta=225.82,293.96
XS Rating Curve= 0 ,0
Exp/Cntr=0.3,0.1

Type RM Length L Ch R = 1 ,4758.453,305.87,346.29,425.66
XS GIS Cut Line= 3
     3114002.284    13827700.897     3113819.995    13827602.176
     3113508.324    13827490.661
#Sta/Elev= 30
       0   44.54     3.2   44.44   25.33   44.75   37.68   43.68   45.73      43
   50.66   42.83   62.79    42.9   69.59   43.14   80.75   43.85   91.72   44.55
  135.99    46.2  148.08   47.09  165.14   48.02   182.2   48.71   208.5   49.23
  237.28   50.38  247.58   48.98  279.44    47.7  311.31   45.99  327.24   45.65
  340.22   45.13  349.91   44.47   359.1   43.74  378.08   43.33  392.98   43.33
  413.28   44.12  454.15   44.59  470.62   44.46  490.41   44.95  538.32   46.14
#Mann= 5 ,-1 , 0
       0    .035       0   37.68    .015       0   80.75    .035       0
  349.91    .015       0  392.98    .035       0
Bank Sta=340.22,490.41
XS Rating Curve= 0 ,0
Exp/Cntr=0.3,0.1

Type RM Length L Ch R = 1 ,4412.167,259.13,250.33,238.13
XS GIS Cut Line= 4
     3114043.335     13827643.25     3113981.028    13827574.808
      3113936.17    13827492.152     3113941.409    13827185.618
#Sta/Elev= 30
       0   44.96    1.94   45.24     9.3   45.32   15.52   45.16   31.58   44.33
   44.39   43.85   56.09   43.42   76.15   43.61  113.08   44.43   130.9   44.28
  163.74    44.3   186.6    44.5  199.74   44.34  256.99   43.09  261.38   43.15
  269.24   43.31  281.28   44.18  289.93   44.47  295.41   44.54  301.99   44.62
  308.17   44.56  325.53   44.17  340.28   44.36  353.96   44.34  369.22   43.96
  415.01   44.26  437.01   43.89  452.02   44.19  482.02   43.77  493.18   43.79
#Mann= 3 ,-1 , 0
       0    .035       0   44.39    .015       0  261.38    .035       0
Bank Sta=199.74,295.41
XS Rating Curve= 0 ,0
Exp/Cntr=0.3,0.1

Type RM Length L Ch R = 1 ,4161.837,314.67,314.23,312.46
XS GIS Cut Line= 2
     3114220.091    13827573.512     3114125.942     13827117.83
#Sta/Elev= 26
       0    46.1   17.09   46.58   37.22   46.01   47.73   45.94    54.8   46.03
   63.04   45.81   78.36    45.1  111.67   43.87  130.97   43.33  139.63   43.44
   152.8   44.18  156.34    44.3  185.58    43.2  195.43   43.37  207.13   43.58
  216.21   43.91  231.26   44.26   270.6   44.11     313   44.25  343.13    44.2
   384.7   43.97  403.77   44.11  423.08   43.91  445.96   44.08  452.92   43.97
  465.31   44.06
#Mann= 4 ,-1 , 0
       0      99       0   37.22    .035       0  111.67    .015       0
  195.43    .035       0
Bank Sta=156.34,231.26
XS Rating Curve= 0 ,0
Exp/Cntr=0.3,0.1

Type RM Length L Ch R = 1 ,3847.611,263.01,248.41,238.38
XS GIS Cut Line= 3
      3114505.16    13827551.104     3114499.701    13827373.143
     3114417.817    13827017.221
#Sta/Elev= 30
       0   42.99   69.36   42.93  113.98   42.67  129.39   42.68  161.26    42.4
  174.41   42.49  185.55   42.38  221.11   43.01  235.89   42.96  251.28   42.58
   266.2   42.65  282.06    43.3  286.84   43.34  304.23   43.61  310.68   43.76
  316.31   43.76  328.24   43.69  345.38   43.41  374.41   44.01  389.81    44.6
   405.2   46.06  436.25   49.48  451.37   51.29  466.76   53.41  498.38   58.14
  510.89   60.15  516.21   60.85  528.33   62.25  535.92   62.39  543.26   63.09
#Mann= 3 ,-1 , 0
       0    .015       0   266.2    .035       0  304.23    .025       0
Bank Sta=221.11,286.84
XS Rating Curve= 0 ,0
Exp/Cntr=0.3,0.1

Type RM Length L Ch R = 1 ,3599.198,271.56,259.42,249.07
XS GIS Cut Line= 2
     3114867.836    13827483.129     3114555.261    13826944.596
#Sta/Elev= 30
       0   44.96   12.45   44.77   36.26   44.38    53.6   44.31      93   44.44
  103.97   44.65  140.32   44.58  147.87   44.39     175   44.47  193.03    43.8
  227.03   43.73  242.84   43.09  251.56   42.78  261.72   42.45  278.51   42.57
  298.66   42.19  311.34   42.45  330.02   42.93  331.88   42.97  348.44   43.26
  370.05   43.96  400.47   43.99   433.2   44.47   459.7   47.43  504.53   53.97
  514.61   55.27   528.6   56.69  553.91   58.68  575.86   58.64  622.67   56.21
#Mann= 6 ,-1 , 0
       0    .035       0   12.45    .027       0  193.03    .035       0
  242.84    .015       0  311.34    .035       0  330.02    .025       0
Bank Sta=251.56,331.88
XS Rating Curve= 0 ,0
Exp/Cntr=0.3,0.1

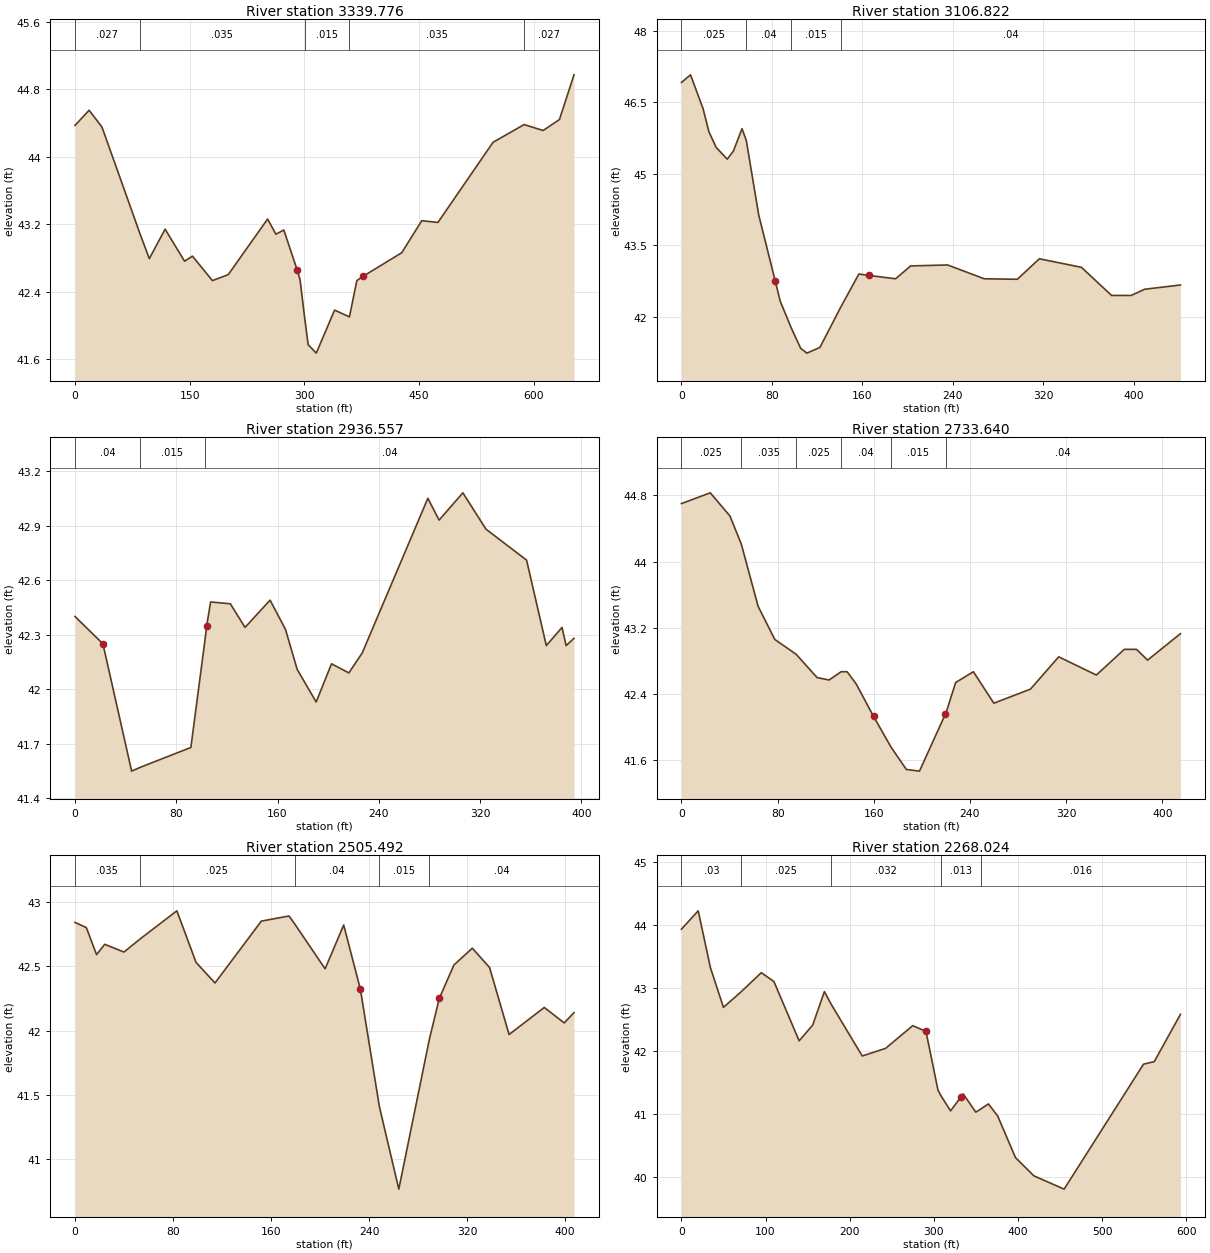
Type RM Length L Ch R = 1 ,3339.776,245.34,232.95,213.51
XS GIS Cut Line= 2
     3115142.751    13827272.235      3114668.24    13826824.085
#Sta/Elev= 30
       0   44.37   18.49   44.55   35.32   44.35   84.85   43.09   97.22   42.79
  117.85   43.14  143.33   42.76   153.6   42.82  179.75   42.53  200.38    42.6
  251.93   43.26  262.82   43.08  273.15   43.13  290.45   42.66  294.38   42.54
  300.24    42.1  304.99   41.77   315.6   41.67  339.53   42.18  358.98    42.1
  368.65   42.53   376.6   42.58  427.34   42.86  453.54   43.24  474.76   43.22
  546.82   44.17  587.42   44.38  612.36   44.31  633.66   44.44  652.69   44.97
#Mann= 5 ,-1 , 0
       0    .027       0   84.85    .035       0  300.24    .015       0
  358.98    .035       0  587.42    .027       0
Bank Sta=290.45,376.6
XS Rating Curve= 0 ,0
Exp/Cntr=0.3,0.1

Type RM Length L Ch R = 1 ,3106.822,177.38,170.26,167.58
XS GIS Cut Line= 2
     3115139.468    13826899.354     3114731.849    13826730.444
#Sta/Elev= 30
       0   46.92    8.01   47.08   19.12   46.37   24.24   45.89   30.59   45.56
   40.48   45.31   45.93   45.48   53.55   45.95   57.36    45.7   68.31   44.14
   82.95   42.75   87.34   42.33   97.07   41.77  105.43   41.34  110.95   41.24
  122.43   41.36  141.19   42.22  156.87    42.9   165.9   42.87  189.36    42.8
  202.66   43.07  235.32   43.09  267.79    42.8  296.97   42.79   316.5   43.22
   353.7   43.04  380.33   42.45  397.69   42.45  409.43   42.58  441.23   42.67
#Mann= 4 ,-1 , 0
       0    .025       0   57.36     .04       0   97.07    .015       0
  141.19     .04       0
Bank Sta=82.95,165.9
XS Rating Curve= 0 ,0
Exp/Cntr=0.3,0.1

Type RM Length L Ch R = 1 ,2936.557,212.54,202.92,199.64
XS GIS Cut Line= 2
       3115160.1    13826714.162     3114781.067    13826606.104
#Sta/Elev= 26
       0    42.4   22.07   42.25   44.74   41.55   51.24   41.57   91.53   41.68
  102.48   42.26  104.05   42.35  107.13   42.48  122.73   42.47  134.31   42.34
  154.08   42.49  166.21   42.33  175.47   42.11  190.49   41.93  202.63   42.14
  216.32   42.09   226.9    42.2  278.71   43.05  287.59   42.93  306.37   43.08
  324.66   42.88  356.69   42.71  372.29   42.24  384.69   42.34  387.89   42.24
  394.14   42.28
#Mann= 3 ,-1 , 0
       0     .04       0   51.24    .015       0  102.48     .04       0
Bank Sta=22.07,104.05
XS Rating Curve= 0 ,0
Exp/Cntr=0.3,0.1

Type RM Length L Ch R = 1 ,2733.640,232.08,228.15,226.35
XS GIS Cut Line= 2
     3115329.457    13826510.633     3114915.671     13826477.88
#Sta/Elev= 28
       0    44.7   23.97   44.83   40.35   44.55   49.81   44.21   63.75   43.46
   77.63   43.06   95.47   42.88  112.77    42.6  122.77   42.57  132.83   42.67
  137.81   42.67  145.45   42.52  159.81   42.13  174.33   41.76  187.07   41.49
     198   41.47  219.58   42.16  219.99   42.17   228.1   42.54  242.84   42.67
  259.84   42.29  290.31   42.46  313.81   42.85  345.15   42.63  368.33   42.94
  378.56   42.94  387.73   42.81  415.08   43.13
#Mann= 6 ,-1 , 0
       0    .025       0   49.81    .035       0   95.47    .025       0
  132.83     .04       0  174.33    .015       0  219.99     .04       0
Bank Sta=159.81,219.58
XS Rating Curve= 0 ,0
Exp/Cntr=0.3,0.1

Type RM Length L Ch R = 1 ,2505.492,239.67,237.47,237.47
XS GIS Cut Line= 2
     3115411.341    13826264.982     3115004.105    13826268.257
#Sta/Elev= 26
       0   42.84    9.27    42.8   17.59   42.59   24.27   42.67      40   42.61
   52.94   42.71   83.15   42.93   98.77   42.53  114.27   42.37  152.06   42.85
  174.66   42.89  179.19   42.83  204.13   42.48   219.3   42.82  232.95   42.32
  248.42   41.41  264.28   40.77  289.15   41.93  297.29   42.25  309.28   42.51
  324.28   42.64  338.35   42.49  354.28   41.97  382.99   42.18  399.28   42.06
  407.25   42.14
#Mann= 5 ,-1 , 0
       0    .035       0   52.94    .025       0  179.19     .04       0
  248.42    .015       0  289.15     .04       0
Bank Sta=232.95,297.29
XS Rating Curve= 0 ,0
Exp/Cntr=0.3,0.1

Type RM Length L Ch R = 1 ,2268.024,314.4,317.64,304.98
XS GIS Cut Line= 2
     3115451.985     13826025.85     3114858.779    13826033.622
#Sta/Elev= 30
       0   43.93   19.91   44.22   34.44   43.32   49.92   42.69   71.19   42.94
   94.92   43.24  109.92    43.1  139.92   42.16  156.05   42.41  169.93   42.94
  177.98   42.74  214.93   41.92  242.68   42.04  274.94    42.4   290.7   42.31
  304.94   41.38  308.49   41.29  319.94   41.05  332.22   41.27  334.94   41.32
  349.94   41.03  355.95   41.08  364.94   41.16  375.94   40.97  397.09   40.31
  419.08   40.02  454.95   39.81  549.32   41.79  562.08   41.83  593.26   42.58
#Mann= 5 ,-1 , 0
       0     .03       0   71.19    .025       0  177.98    .032       0
  308.49    .013       0  355.95    .016       0
Bank Sta=290.7,332.22
XS Rating Curve= 0 ,0
Exp/Cntr=0.3,0.1

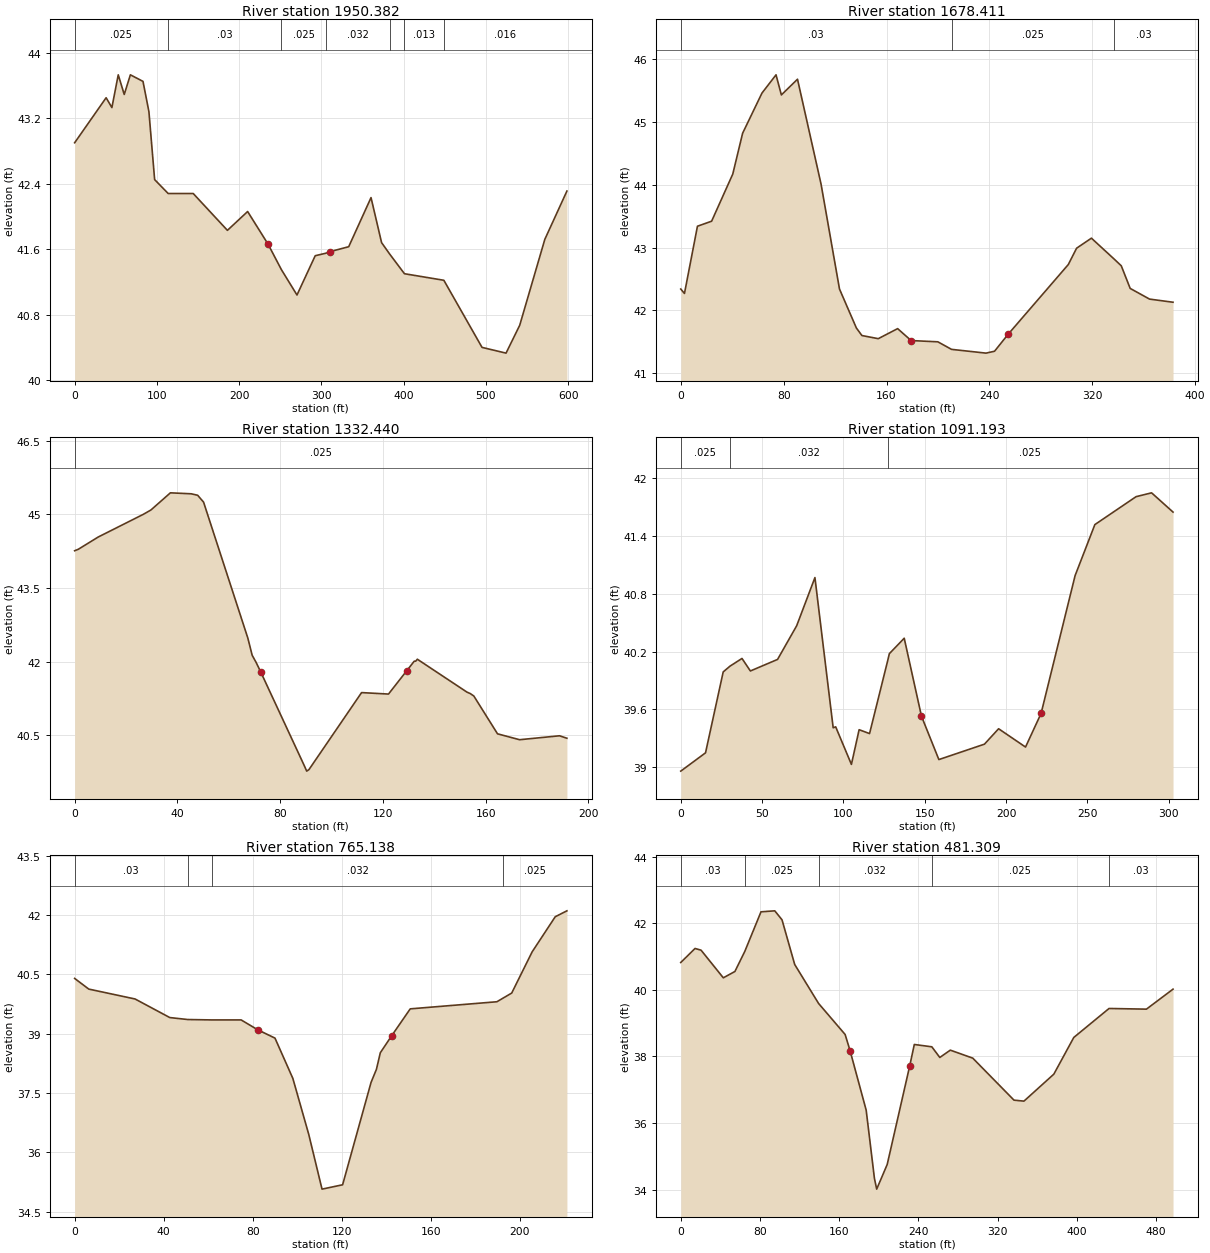
Type RM Length L Ch R = 1 ,1950.382,261.94,271.97,268.29
XS GIS Cut Line= 2
     3115462.346    13825733.133      3114863.96    13825743.495
#Sta/Elev= 30
       0    42.9   38.26   43.45   45.28   43.33      53   43.73   60.28   43.49
   67.75   43.73   83.09   43.65   90.29   43.28   97.24   42.45  113.71   42.28
  144.15   42.28  185.72   41.83   210.3   42.06   235.2   41.66  251.36   41.35
  270.31   41.04  292.47   41.52  305.22   41.55  310.61   41.57  333.19   41.63
  360.33   42.23  373.15   41.68  383.02   41.54  400.98    41.3  448.86   41.22
  495.28    40.4  524.47   40.33  541.08   40.67  571.62   41.72  598.48   42.31
#Mann= 7 ,-1 , 0
       0    .025       0  113.71     .03       0  251.36    .025       0
  305.22    .032       0  383.02     .03       0  400.98    .013       0
  448.86    .016       0
Bank Sta=235.2,310.61
XS Rating Curve= 0 ,0
Exp/Cntr=0.3,0.1

Type RM Length L Ch R = 1 ,1678.411,334.61,345.97,374.63
XS GIS Cut Line= 2
     3115404.942    13825498.076     3115023.907    13825460.984
#Sta/Elev= 30
       0   42.34    2.88   42.27   12.98   43.34      24   43.42   40.44   44.17
    48.1   44.82   63.17   45.46   74.09   45.75   78.24   45.43   90.79   45.68
  109.11   44.01  123.45   42.34  136.58   41.72  140.88    41.6  153.59   41.55
  168.66   41.71  179.17   41.52  199.95    41.5  210.56   41.38  237.38   41.32
  244.02   41.35  254.59   41.62  301.39   42.73  307.84   42.99  319.37   43.15
   336.9   42.82  342.59   42.71  349.51   42.35  364.58   42.18  382.84   42.13
#Mann= 3 ,-1 , 0
       0     .03       0  210.56    .025       0   336.9     .03       0
Bank Sta=179.17,254.59
XS Rating Curve= 0 ,0
Exp/Cntr=0.3,0.1

Type RM Length L Ch R = 1 ,1332.440,235.37,241.25,241.66
XS GIS Cut Line= 2
     3115303.794    13825232.746      3115163.59    13825102.062
#Sta/Elev= 30
       0   44.26    1.43   44.29    9.19   44.54   26.67      45   29.69   45.09
   37.28   45.44   45.43   45.42    47.9   45.39    50.2   45.25   67.43   42.48
   69.12   42.13    70.7   41.98   72.45   41.79   89.42   39.88   90.35   39.77
   91.21    39.8  111.58   41.36  111.72   41.37  122.19   41.34  129.37   41.82
  132.22   42.01   132.8   42.01  133.42   42.05  152.73   41.38  154.03   41.35
  155.42    41.3  164.64   40.53  173.23   40.41  188.78   40.49  191.66   40.44
#Mann= 1 ,-1 , 0
       0    .025       0
Bank Sta=72.45,129.37
XS Rating Curve= 0 ,0
Exp/Cntr=0.3,0.1

Type RM Length L Ch R = 1 ,1091.193,317.34,326.05,356.53
XS GIS Cut Line= 3
     3115489.022     13825150.19     3115438.346    13825046.926
     3115318.654    13824902.527
#Sta/Elev= 28
       0   38.96   15.22   39.15   26.08   39.99   30.26   40.05   37.63   40.13
   42.79      40    59.5   40.12   71.26   40.47   82.47   40.97   93.68   39.41
   95.22   39.42  104.89   39.03  109.63   39.39  116.04   39.35  127.09    40.1
  128.22   40.18  137.35   40.34  147.96   39.53  158.65   39.08  186.66   39.24
  195.37    39.4  211.92   39.21  221.49   39.56  242.38   40.99  254.53   41.52
  279.86   41.81  289.39   41.85  302.58   41.65
#Mann= 3 ,-1 , 0
       0    .025       0   30.26    .032       0  127.09    .025       0
Bank Sta=147.96,221.49
XS Rating Curve= 0 ,0
Exp/Cntr=0.3,0.1

Type RM Length L Ch R = 1 ,765.138 ,298.26,283.83,265.73
XS GIS Cut Line= 2
      3115710.49    13825035.633     3115675.553    13824817.276
#Sta/Elev= 24
       0    40.4    6.35   40.13   27.14   39.88   42.73   39.41   50.86   39.36
   61.92   39.35    74.8   39.35   82.26    39.1   89.99   38.89   98.02   37.87
  105.18   36.45  111.12   35.07  120.37   35.18  133.15   37.77  135.56    38.1
  137.31   38.52  142.41   38.95  150.75   39.63  189.69   39.81  192.39    39.9
  196.33   40.03  205.49   41.07  215.88   41.96  221.13   42.11
#Mann= 4 ,-1 , 0
       0     .03       0   50.86    .025       0   61.92    .032       0
  192.39    .025       0
Bank Sta=82.26,142.41
XS Rating Curve= 0 ,0
Exp/Cntr=0.3,0.1

Type RM Length L Ch R = 1 ,481.309 ,224.14,222.54,221.4
XS GIS Cut Line= 2
     3116060.733    13824927.513      3115729.16    13824557.084
#Sta/Elev= 30
       0   40.82   14.41   41.24   20.48   41.19   42.97   40.36   54.68   40.55
   64.63   41.15   81.02   42.34   94.94   42.37  102.26    42.1  115.07   40.76
   139.2   39.59     166   38.66  171.02   38.17  187.25   36.39   195.6   34.34
  197.87   34.02  208.49   34.76  231.17   37.71  235.86   38.36  253.55   38.29
  261.61   37.97  272.23   38.19   294.9   37.95  336.52   36.69  346.59   36.66
  376.78   37.47  396.91   38.57  432.52   39.44  470.29   39.42  497.15   40.02
#Mann= 5 ,-1 , 0
       0     .03       0   64.63    .025       0   139.2    .032       0
  253.55    .025       0  432.52     .03       0
Bank Sta=171.02,231.17
XS Rating Curve= 0 ,0
Exp/Cntr=0.3,0.1

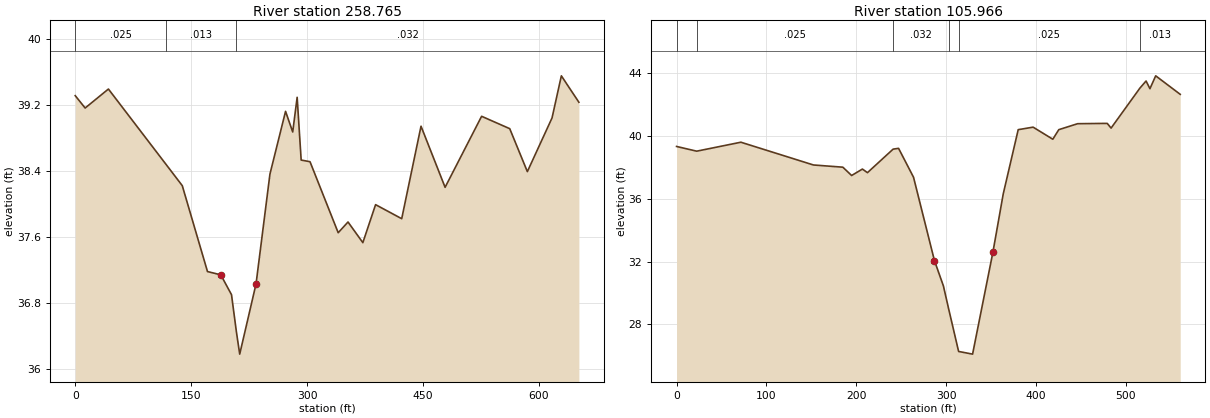
Type RM Length L Ch R = 1 ,258.765 ,145.69,152.8,158.55
XS GIS Cut Line= 3
     3116220.678    13824773.832     3115982.299    13824509.756
     3115755.722    13824319.165
#Sta/Elev= 30
       0   39.31   12.84   39.16   42.95   39.39  117.33   38.48  138.54   38.22
  171.17   37.18  188.38   37.14  202.26    36.9  208.59   36.45  212.88   36.18
  234.01   37.03     252   38.36  272.21   39.12  281.47   38.87  287.22   39.29
  292.41   38.53  303.86   38.51  340.33   37.65  353.04   37.78  372.23   37.53
  388.72   37.99  422.53   37.82  447.52   38.94  478.69    38.2  525.93   39.06
  562.34   38.91  585.15   38.39  617.08   39.04  629.15   39.55  651.83   39.23
#Mann= 3 ,-1 , 0
       0    .025       0  117.33    .013       0  208.59    .032       0
Bank Sta=188.38,234.01
XS Rating Curve= 0 ,0
Exp/Cntr=0.3,0.1

Type RM Length L Ch R = 1 ,105.966 ,90.81,105.97,80.89
XS GIS Cut Line= 4
     3116375.772    13824827.767     3116251.229    13824625.384
     3116178.884      13824475.2     3116091.887    13824345.162
#Sta/Elev= 30
       0   39.33   22.43   39.03   71.62    39.6  152.42   38.15  185.13   38.01
  194.91   37.48  206.94   37.89  212.52   37.66  241.14   39.16  247.19   39.21
  263.84   37.37  287.12   32.06  297.14   30.44  302.83   29.01  314.04   26.27
   329.6    26.1  352.18   32.58  363.74   36.31  380.39    40.4  396.99   40.56
  418.92   39.79  425.58    40.4  446.56   40.78  479.53    40.8   483.8    40.5
  515.93   43.05  522.76    43.5  527.06   43.01  533.48   43.83  560.79   42.65
#Mann= 6 ,-1 , 0
       0    .013       0   22.43    .025       0  241.14    .032       0
  302.83    .013       0  314.04    .025       0  515.93    .013       0
Bank Sta=287.12,352.18
XS Rating Curve= 0 ,0
Exp/Cntr=0.3,0.1

River Reach=D109-02-99      ,D109-02-99_0001
Reach XY= 30
     3112181.922    13825255.154     3112516.478    13825032.194
     3112661.379     13824943.14     3112739.867    13824891.821
     3112833.503    13824799.071     3112884.842       13824758.
      3112921.35    13824723.773     3112947.591    13824692.969
     3112987.521     13824629.08     3113017.184     13824564.05
      3113037.72    13824497.879     3113070.806    13824351.847
     3113084.496    13824298.225     3113093.631    13824267.148
     3113121.004    13824193.265     3113150.667    13824123.671
     3113194.021    13824035.823     3113223.683    13823983.343
     3113269.319    13823912.608      3113335.49    13823825.902
     3113423.017    13823724.023     3113715.747    13823455.558
     3113764.277    13823396.702     3113825.714       13823311.
     3113854.589    13823260.026     3113894.379    13823180.897
     3113936.733    13823086.612     3114022.299    13822912.058
     3114039.412    13822872.127     3114050.821    13822839.041