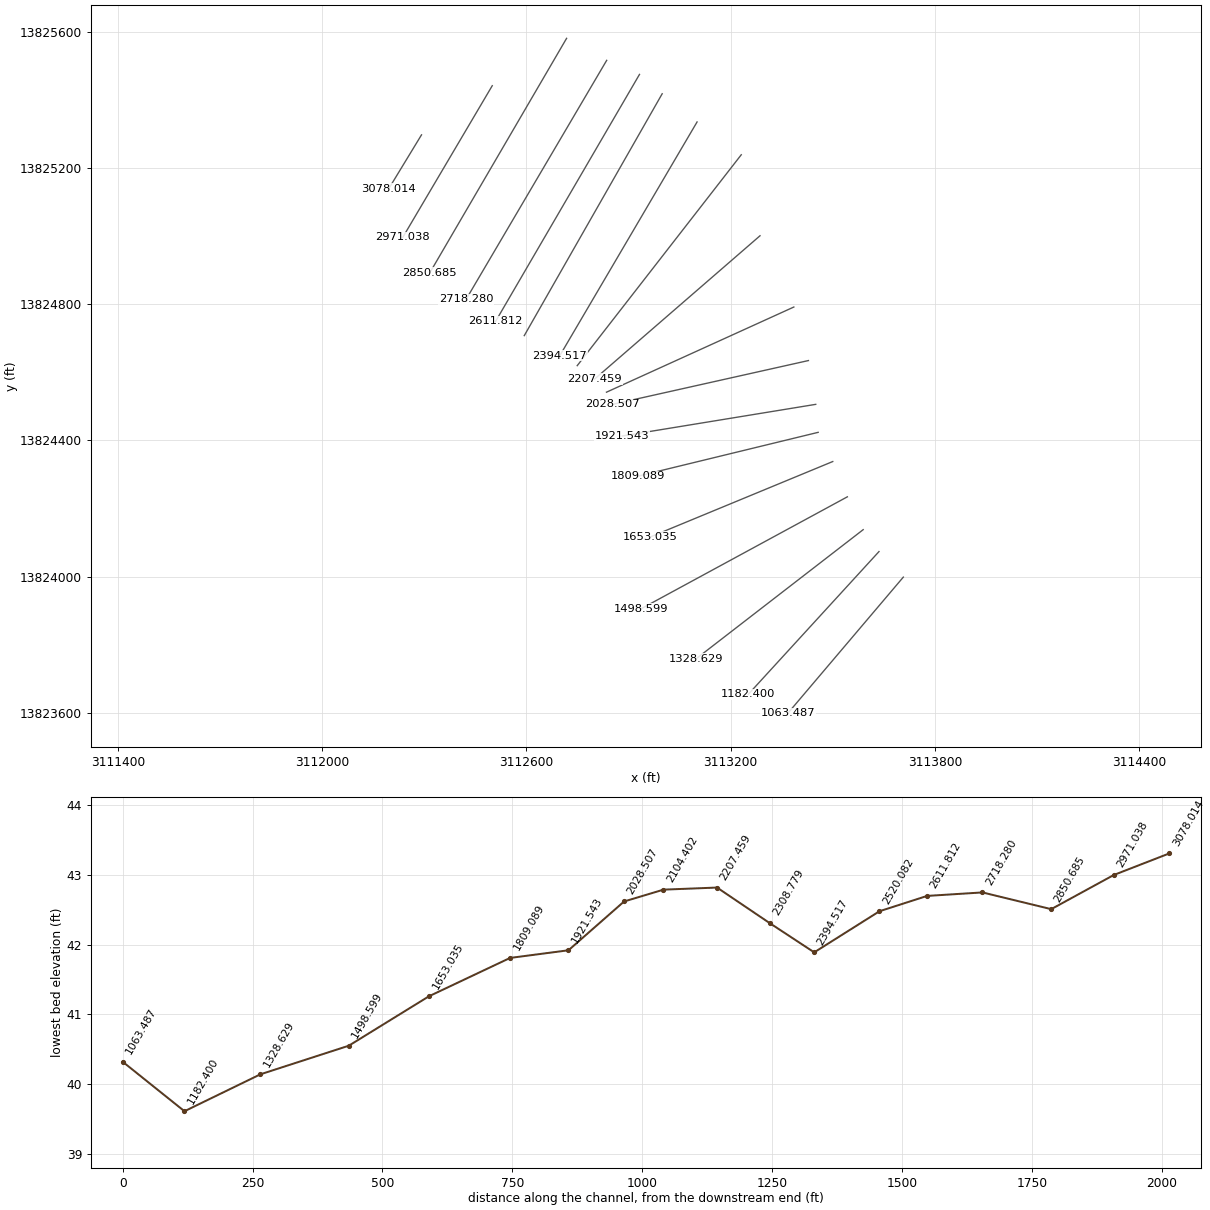
HEC-RAS study D109-00-00.prj: D109-00-00

--- D109-00-00.g01 (geometry) --- (continued)

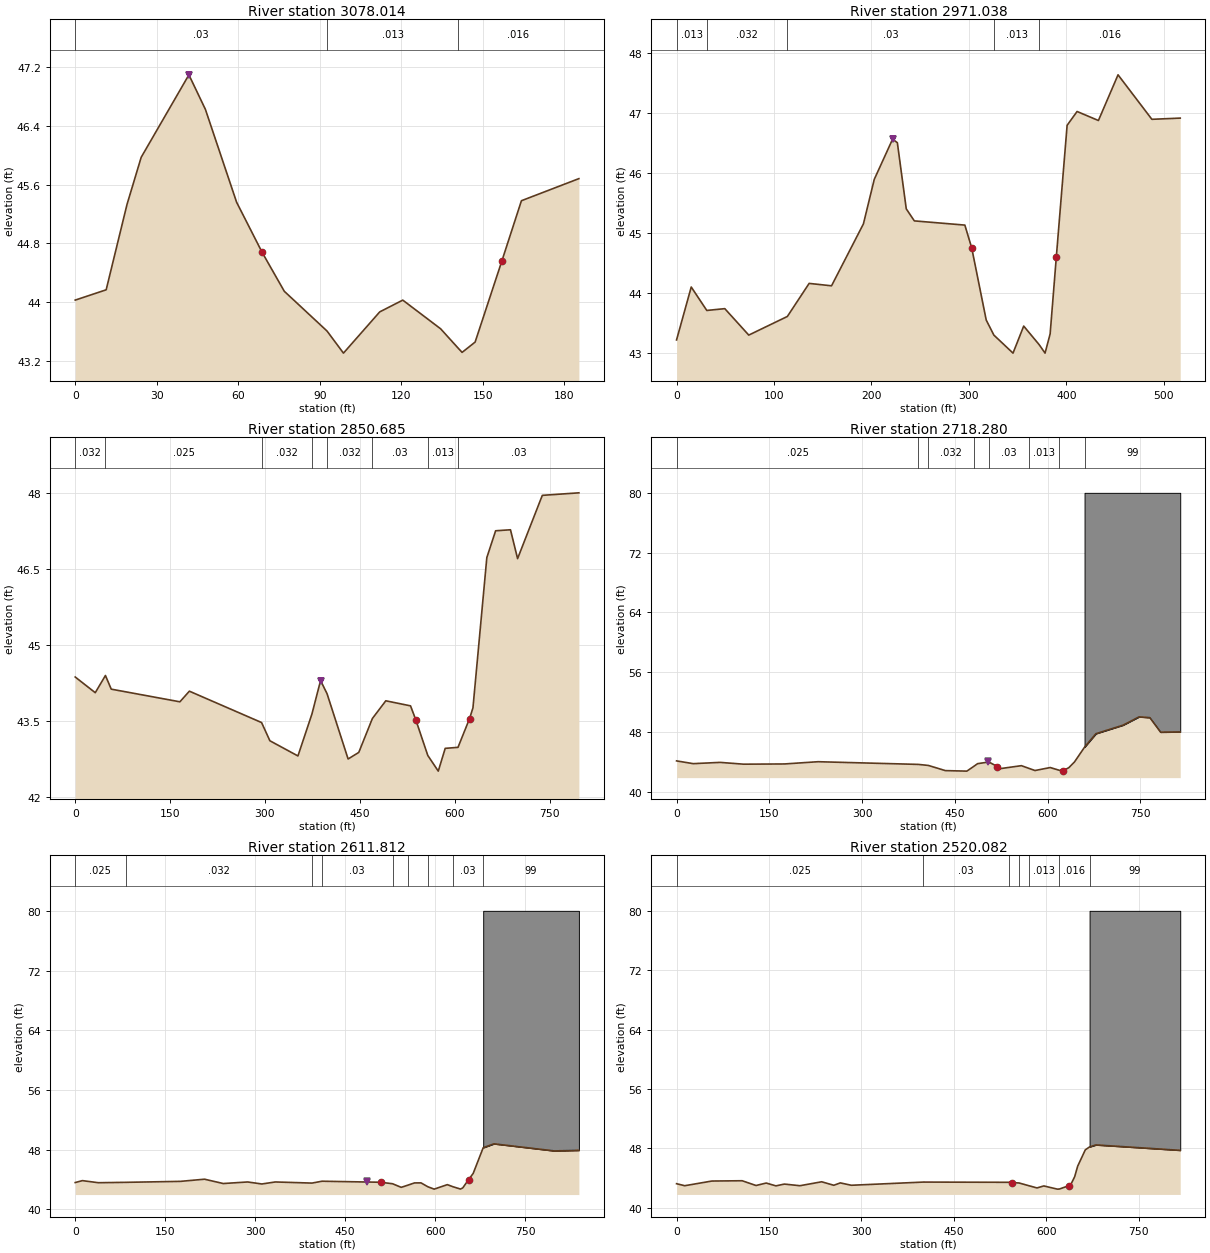
Type RM Length L Ch R = 1 ,3078.014,106.55,106.98,107.69
XS GIS Cut Line= 2
     3112291.977    13825297.516     3112195.638    13825139.149
#Sta/Elev= 20
       0   44.03   11.39   44.17   19.06   45.33   24.28   45.97   41.84   47.09
   47.92   46.62   59.39   45.36   68.77   44.68   76.95   44.15   92.68   43.61
   98.72   43.31  112.07   43.87  120.55   44.03   134.5   43.64  140.88   43.38
  142.39   43.32  147.18   43.46  157.01   44.56  164.22   45.38  185.37   45.68
#Mann= 3 ,-1 , 0
       0     .03       0   92.68    .013       0  140.88    .016       0
Levee=-1,41.84,47.09,0,,,,
Bank Sta=68.77,157.01
XS Rating Curve= 0 ,0
Exp/Cntr=0.3,0.1

Type RM Length L Ch R = 1 ,2971.038,120.11,120.35,120.5
XS GIS Cut Line= 2
     3112499.726    13825441.884     3112237.089    13824996.814
#Sta/Elev= 30
       0   43.22   15.06    44.1   31.01   43.71   49.48   43.74   74.09    43.3
  113.69   43.61  136.03   44.16  159.02   44.12  191.72   45.15  202.83   45.89
  221.66   46.56  226.55    46.5  235.69    45.4  243.97    45.2   295.8   45.13
  302.84   44.75  317.73   43.55  325.57    43.3  345.22      43  356.18   43.45
  372.08   43.14  378.08      43   383.3   43.32  389.65    44.6  400.72   46.79
  410.94   47.02  432.85   46.87  452.97   47.63  487.69   46.89  516.78   46.91
#Mann= 5 ,-1 , 0
       0    .013       0   31.01    .032       0  113.69     .03       0
  325.57    .013       0  372.08    .016       0
Levee=-1,221.66,46.56,0,,,,
Bank Sta=302.84,389.65
XS Rating Curve= 0 ,0
Exp/Cntr=0.3,0.1

Type RM Length L Ch R = 1 ,2850.685,134.4,132.4,132.38
XS GIS Cut Line= 2
     3112718.038     13825580.97     3112316.693    13824893.048
#Sta/Elev= 30
       0   44.37   31.68   44.06   47.79    44.4   56.96   44.13  165.53   43.88
  180.51   44.09  294.68   43.47  307.83   43.11  352.18   42.81  374.33   43.64
  387.97    44.3  398.22   44.04  431.51   42.75  448.41   42.88   469.9   43.55
  491.11    43.9  530.22    43.8  538.39   43.53  557.51   42.82  574.09   42.51
  585.05   42.96  605.29   42.98  623.61   43.55  628.92   43.76  650.86   46.73
  664.77   47.26  688.27   47.28  699.51   46.71   738.6   47.96  796.44   48.01
#Mann= 8 ,-1 , 0
       0    .032       0   47.79    .025       0  294.68    .032       0
  374.33    .013       0  398.22    .032       0   469.9     .03       0
  557.51    .013       0  605.29     .03       0
Levee=-1,387.97,44.3,0,,,,
Bank Sta=538.39,623.61
XS Rating Curve= 0 ,0
Exp/Cntr=0.3,0.1

Type RM Length L Ch R = 1 ,2718.280,108.54,106.47,108.28
XS GIS Cut Line= 2
     3112835.765    13825516.328     3112422.867    13824814.401
#Sta/Elev= 30
       0   44.12   27.01   43.75   70.33   43.92  108.29   43.68  174.42   43.71
  228.82   44.01  390.89   43.65  407.18   43.51  434.55   42.82  469.36   42.75
  480.47   43.38  486.76   43.75   504.9   43.97  518.75   43.36  524.67    43.1
  557.54   43.48  570.05   43.11  579.46   42.83  604.16   43.23  618.92   42.86
  624.62    42.8  634.24   43.21  643.38   43.98  659.63   45.95  678.07   47.76
   721.9    48.9   747.8   50.01   765.2   49.91  782.61   47.96  814.36      48
#Mann= 8 ,-1 , 0
       0    .025       0  390.89     .03       0  407.18    .032       0
  480.47    .013       0   504.9     .03       0  570.05    .013       0
  618.92     .03       0  659.63      99       0
Levee=-1,502.75,44.08,0,,,,
#Block Obstruct= 1 ,-1
  659.63  814.36      80
Bank Sta=518.75,624.62
XS Rating Curve= 0 ,0
Exp/Cntr=0.3,0.1

Type RM Length L Ch R = 1 ,2611.812,104,91.73,92.26
XS GIS Cut Line= 2
     3112932.108    13825475.038     3112509.379    13824749.517
#Sta/Elev= 30
       0   43.58   11.91   43.84    38.5   43.56   83.97   43.61   175.5   43.74
  215.58   44.03  246.83   43.45   287.5   43.66  311.09   43.39  333.63   43.66
  394.65   43.51  411.45   43.76  509.69   43.62  529.01   43.42  543.56   42.94
   554.2   43.22   565.5   43.53  576.47   43.54  587.78   43.02  598.41    42.7
  620.34    43.3  629.77   43.02  642.28   42.71  646.12   42.87   655.8   43.97
  663.48   44.81  680.15   48.25   698.2   48.77  798.75   47.82  839.69    47.9
#Mann= 9 ,-1 , 0
       0    .025       0   83.97    .032       0  394.65    .025       0
  411.45     .03       0  529.01    .013       0   554.2     .03       0
  587.78    .013       0  629.77     .03       0  680.15      99       0
Levee=-1,486.73,43.75,0,,,,
#Block Obstruct= 1 ,-1
  680.15  839.69      80
Bank Sta=509.69,655.8
XS Rating Curve= 0 ,0
Exp/Cntr=0.3,0.1

Type RM Length L Ch R = 1 ,2520.082,126.53,125.57,122.49
XS GIS Cut Line= 2
     3112998.757    13825418.218     3112593.761    13824707.953
#Sta/Elev= 30
       0   43.21   13.29   42.94   57.28   43.57  106.49   43.61  128.98   42.97
  145.56    43.3  161.24   42.92     175   43.16  200.24   42.94  235.57   43.47
  255.22      43  265.85   43.32  283.69      43  400.63   43.43  539.63    43.4
  543.72   43.37  555.98   43.31  572.33   42.93  585.12   42.64  596.12   42.91
  618.11   42.48  621.39   42.49  636.92   42.95  640.11   43.12   646.3   44.16
   651.1   45.57  663.57   47.78  670.45   48.17  680.84   48.44  817.62   47.71
#Mann= 7 ,-1 , 0
       0    .025       0  400.63     .03       0  539.63    .013       0
  555.98     .03       0  572.33    .013       0  621.39    .016       0
  670.45      99       0
#Block Obstruct= 1 ,-1
  670.45  817.62      80
Bank Sta=543.72,636.92
XS Rating Curve= 0 ,0
Exp/Cntr=0.3,0.1

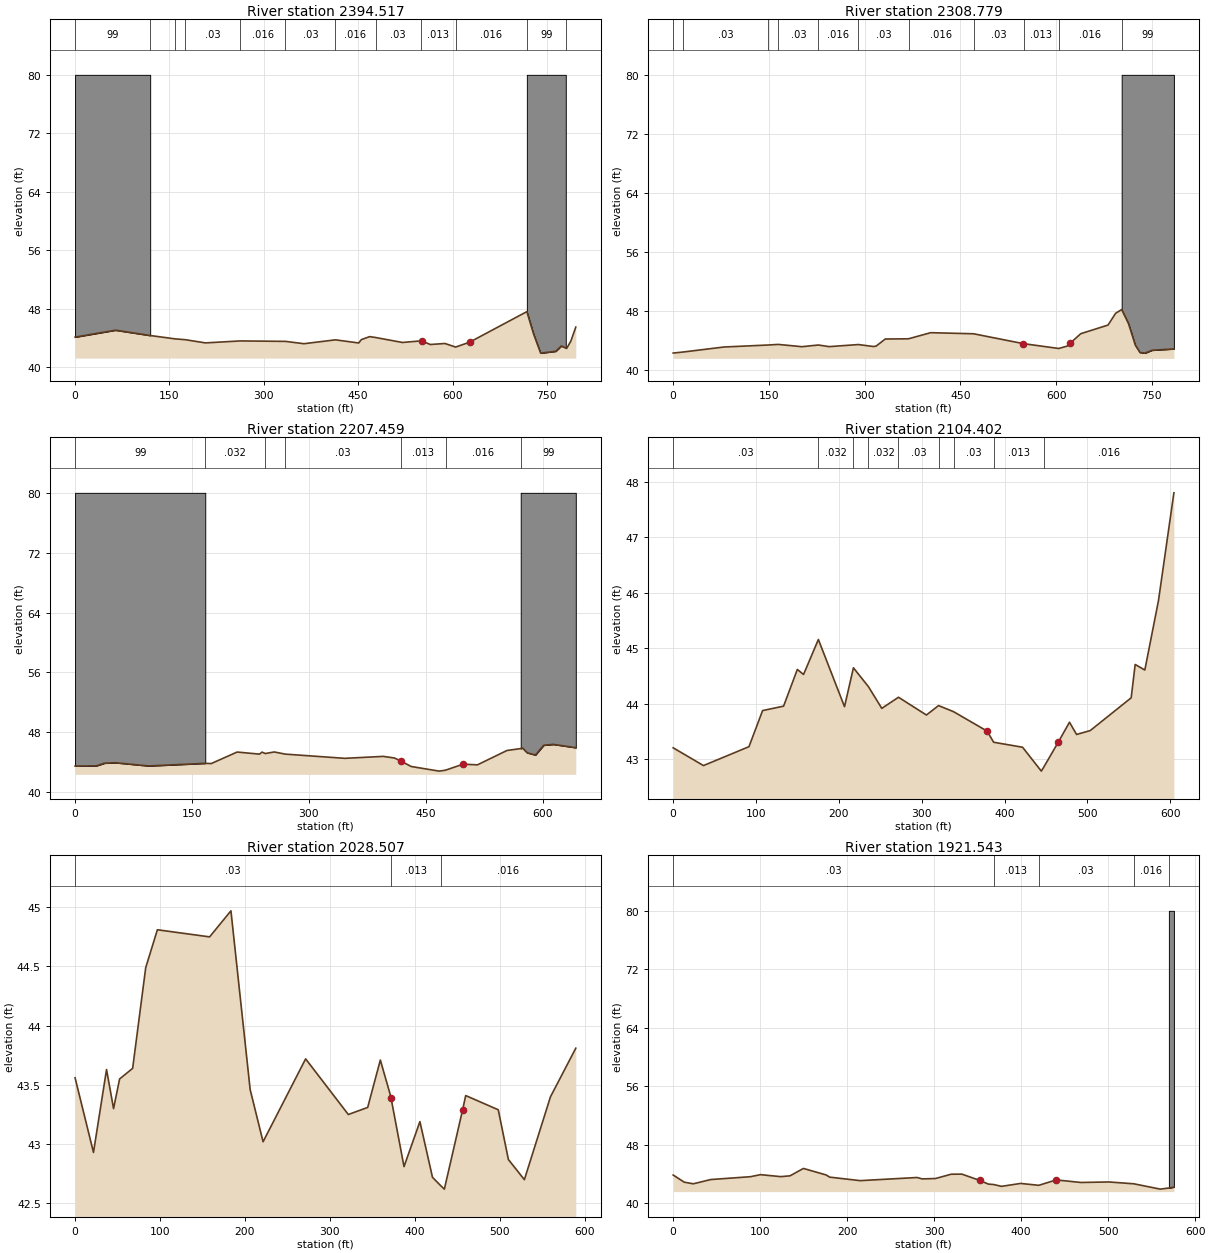
Type RM Length L Ch R = 1 ,2394.517,90.36,85.74,80.41
XS GIS Cut Line= 2
     3113101.199    13825335.439     3112698.132    13824649.241
#Sta/Elev= 30
       0   44.08   64.21   45.03  119.37    44.3  159.16   43.84  175.08   43.73
  207.21   43.29  262.62   43.56  334.24    43.5  363.78   43.18  413.83   43.71
  450.76   43.28  455.01   43.74  468.15   44.15  477.49   44.03  520.34   43.35
  549.12   43.56  550.71   43.57  564.61   43.07  587.84   43.21  604.82   42.72
  627.11   43.39  718.03   47.57  728.81   44.49  739.95   41.89  763.89   42.14
  772.83   42.87   779.9   42.59  781.29   42.53  788.04   43.55  795.82   45.45
#Mann= 12 ,-1 , 0
       0      99       0  119.37     .03       0  159.16    .013       0
  175.08     .03       0  262.62    .016       0  334.24     .03       0
  413.83    .016       0  477.49     .03       0  549.12    .013       0
  604.82    .016       0  718.03      99       0   779.9    .016       0
#Block Obstruct= 2 ,-1
       0  119.37      80  718.03   779.9      80
Bank Sta=550.71,627.11
XS Rating Curve= 0 ,0
Exp/Cntr=0.3,0.1

Type RM Length L Ch R = 1 ,2308.779,109.59,101.32,95.04
XS GIS Cut Line= 2
     3113230.967    13825239.096     3112749.253    13824619.749
#Sta/Elev= 30
       0   42.32   15.69   42.46   79.64   43.14  149.08   43.41  164.77   43.49
   201.8   43.18  227.54   43.41  244.36   43.19  290.31   43.47  313.32   43.21
  317.98   43.26  332.33   44.22  368.77   44.25  403.49   45.08  470.78   44.93
  548.45    43.6  549.24   43.59  604.16   42.94  617.37   43.26  622.21   43.66
  638.65   44.94  681.41   46.11  693.38   47.71  702.79   48.21  713.48   46.31
  724.17   43.39  731.39    42.4  739.31   42.31  750.39    42.7  784.63   42.88
#Mann= 11 ,-1 , 0
       0    .013       0   15.69     .03       0  149.08    .013       0
  164.77     .03       0  227.54    .016       0  290.31     .03       0
  368.77    .016       0  470.78     .03       0  549.24    .013       0
  604.16    .016       0  702.79      99       0
#Block Obstruct= 1 ,-1
  702.79  784.63      80
Bank Sta=548.45,622.21
XS Rating Curve= 0 ,0
Exp/Cntr=0.3,0.1

Type RM Length L Ch R = 1 ,2207.459,116.56,103.06,92.15
XS GIS Cut Line= 2
      3113286.02    13825001.188     3112800.373    13824580.425
#Sta/Elev= 30
       0    43.5    27.2   43.52   37.83   43.88   51.84   43.94   94.53   43.51
  167.07   43.86  174.73   43.83  207.97   45.37  236.77   45.09  239.87   45.36
  244.18   45.17  255.53   45.38  269.88   45.09  346.21   44.53  395.54   44.79
  410.01   44.57  417.67   44.19  431.28   43.44  467.28   42.82   475.5   42.95
  497.99   43.75  516.35   43.66  554.32   45.58  571.89   45.83  574.16   45.91
  580.15   45.27  590.78   44.97  601.42   46.28  613.86   46.39  642.57   45.95
#Mann= 7 ,-1 , 0
       0      99       0  167.07    .032       0  244.18    .013       0
  269.88     .03       0  417.67    .013       0   475.5    .016       0
  571.89      99       0
#Block Obstruct= 2 ,-1
       0  167.07      80  571.89  642.57      80
Bank Sta=417.67,497.99
XS Rating Curve= 0 ,0
Exp/Cntr=0.3,0.1

Type RM Length L Ch R = 1 ,2104.402,85.43,75.89,67.79
XS GIS Cut Line= 2
      3113385.35    13824791.923     3112835.142    13824541.829
#Sta/Elev= 30
       0   43.21   36.57   42.89   91.48   43.23  107.95   43.88  133.28   43.96
  149.85   44.62  157.38   44.53  175.27   45.16  206.81   43.95  217.58   44.65
  235.71   44.31   251.8   43.92  271.97   44.12  305.68    43.8  320.32   43.97
  338.45   43.86  378.95   43.51   386.8   43.31  421.72   43.22  444.38   42.79
  447.24   42.86  464.77   43.31  478.36   43.67  486.92   43.45   503.4   43.52
  552.83   44.11  557.65   44.71  569.31   44.61  585.78   45.86  604.38    47.8
#Mann= 9 ,-1 , 0
       0     .03       0  175.27    .032       0  217.58     .03       0
  235.71    .032       0  271.97     .03       0  320.32    .013       0
  338.45     .03       0   386.8    .013       0  447.24    .016       0
Bank Sta=378.95,464.77
XS Rating Curve= 0 ,0
Exp/Cntr=0.3,0.1

Type RM Length L Ch R = 1 ,2028.507,110.63,106.96,105.15
XS GIS Cut Line= 2
     3113428.223    13824634.721     3112853.006    13824506.101
#Sta/Elev= 30
       0   43.56   21.67   42.93   37.04   43.63    45.3    43.3   52.41   43.55
   67.78   43.64   83.15   44.49   96.89   44.81  158.36   44.75  183.48   44.97
  206.12   43.46  221.31   43.02  271.41   43.72  321.66   43.25  344.45   43.31
  359.34   43.71  371.34   43.41  371.92   43.39  387.21   42.81  405.93   43.19
  420.72   42.72  430.28   42.65  434.71   42.62  456.21   43.29  459.84   43.41
  498.16   43.29  510.08   42.87   528.9    42.7  559.64    43.4  589.42   43.81
#Mann= 3 ,-1 , 0
       0     .03       0  371.34    .013       0  430.28    .016       0
Bank Sta=371.92,456.21
XS Rating Curve= 0 ,0
Exp/Cntr=0.3,0.1

Type RM Length L Ch R = 1 ,1921.543,108.77,112.45,115.37
XS GIS Cut Line= 2
      3113449.66    13824506.101     3112881.588    13824413.208
#Sta/Elev= 30
       0   43.85   12.75   42.87   23.18   42.65   43.15   43.23   88.75   43.62
  100.46    43.9  123.59   43.63  134.35   43.74  149.72   44.75  175.84   43.86
  179.95   43.56  215.03   43.08  280.35   43.51  286.34   43.32  301.54   43.37
  319.54   43.96  331.94   43.97  352.28   43.12  362.34   42.61  368.39   42.55
  377.54    42.3  399.44    42.7   420.2   42.44  440.35   43.18  468.73   42.83
   500.9    42.9  529.57   42.65  559.93   41.92  569.86   42.07  575.62    42.2
#Mann= 5 ,-1 , 0
       0     .03       0  368.39    .013       0   420.2     .03       0
  529.57    .016       0  569.86      99       0
#Block Obstruct= 1 ,-1
  569.86  575.62      80
Bank Sta=352.28,440.35
XS Rating Curve= 0 ,0
Exp/Cntr=0.3,0.1

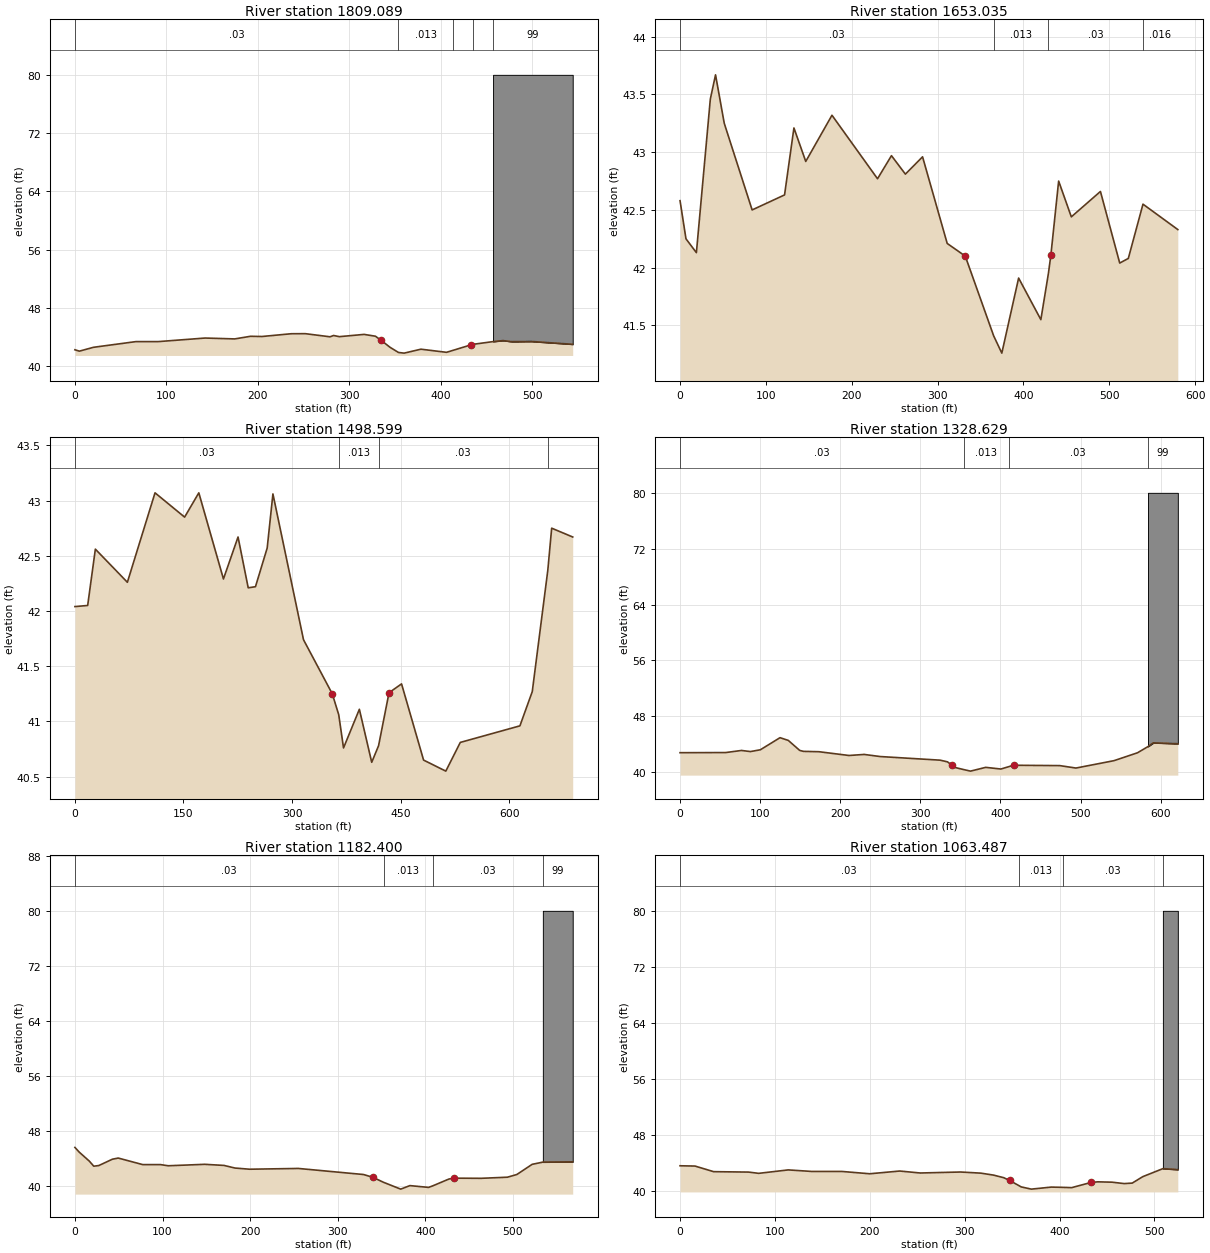
Type RM Length L Ch R = 1 ,1809.089,147.24,156.05,161.87
XS GIS Cut Line= 2
     3113456.806    13824423.927     3112928.034    13824295.307
#Sta/Elev= 30
       0   42.27    4.87   42.08   20.31   42.61   66.62   43.39   91.04   43.39
  142.29   43.88  174.68   43.76  191.96   44.12  204.37   44.09  236.43   44.47
  251.87   44.48  278.88   44.05  282.74   44.23   289.1   44.07  316.13   44.38
  328.54   44.13  334.68   43.57  344.49   42.61  353.72    41.9  359.93   41.81
  378.21   42.35  406.24   41.92  413.58    42.2  432.63   42.93  435.35   43.02
  457.12   43.39  467.99   43.53  477.55   43.38  498.87   43.41  544.19   43.02
#Mann= 5 ,-1 , 0
       0     .03       0  353.72    .013       0  413.58    .016       0
  435.35     .03       0  457.12      99       0
#Block Obstruct= 1 ,-1
  457.12  544.19      80
Bank Sta=334.68,432.63
XS Rating Curve= 0 ,0
Exp/Cntr=0.3,0.1

Type RM Length L Ch R = 1 ,1653.035,151.32,154.44,157.82
XS GIS Cut Line= 2
     3113499.679     13824338.18     3112963.762    13824116.668
#Sta/Elev= 30
       0   42.58     6.9   42.25   19.05   42.13   35.28   43.46   41.35   43.67
   51.51   43.25   83.97    42.5  121.74   42.63  132.67   43.21  146.45   42.92
  176.98   43.32  230.05   42.77  246.28   42.97  262.51   42.81  282.52   42.96
  311.21   42.21  332.28    42.1  365.33   41.41  374.85   41.26  394.43   41.91
  420.33   41.55  429.12   41.95  432.02   42.11  441.05   42.75  455.82   42.44
  489.74   42.66   512.2   42.04  522.21   42.08   539.3   42.55  579.89   42.33
#Mann= 4 ,-1 , 0
       0     .03       0  365.33    .013       0  429.12     .03       0
   539.3    .016       0
Bank Sta=332.28,432.02
XS Rating Curve= 0 ,0
Exp/Cntr=0.3,0.1

Type RM Length L Ch R = 1 ,1498.599,162.23,169.97,174.5
XS GIS Cut Line= 2
     3113542.552    13824234.569     3112937.947    13823906.473
#Sta/Elev= 30
       0   42.04   17.61   42.05   28.23   42.56   72.48   42.26  110.69   43.07
  151.58   42.85  171.21   43.07  205.24   42.29  225.41   42.67  239.47   42.21
  249.49   42.22  265.68   42.57  273.61   43.06  315.86   41.74  355.64   41.25
  364.58   41.06  371.18   40.76  393.07   41.11  410.14   40.63  419.61   40.78
  434.06   41.26  451.37   41.34  481.81   40.65  512.53   40.55  532.55   40.81
  614.93   40.96     632   41.27   653.5   42.37  658.81   42.75  687.89   42.67
#Mann= 4 ,-1 , 0
       0     .03       0  364.58    .013       0  419.61     .03       0
   653.5    .016       0
Bank Sta=355.64,434.06
XS Rating Curve= 0 ,0
Exp/Cntr=0.3,0.1

Type RM Length L Ch R = 1 ,1328.629,137.34,146.23,153.83
XS GIS Cut Line= 2
     3113588.998    13824138.104      3113097.27    13823758.096
#Sta/Elev= 30
       0   42.78   57.06    42.8   76.75    43.1   87.87   42.94   100.3    43.2
  124.83   44.93  135.13   44.54  149.36   43.11  154.09   42.97  173.42   42.92
  210.96   42.38  229.92   42.53  249.75   42.23  324.71   41.71  333.82   41.47
  339.31   41.01  343.66   40.65  354.23   40.36  362.62   40.14  381.58   40.68
  400.53   40.44  410.16   40.77  416.37   40.98   474.1   40.93  494.22   40.58
  541.85   41.64  571.15   42.77  584.16   43.65  590.91   44.19  621.45   44.06
#Mann= 4 ,-1 , 0
       0     .03       0  354.23    .013       0  410.16     .03       0
  584.16      99       0
#Block Obstruct= 1 ,-1
  584.16  621.45      80
Bank Sta=339.31,416.37
XS Rating Curve= 0 ,0
Exp/Cntr=0.3,0.1

Type RM Length L Ch R = 1 ,1182.400,117.45,118.91,120.03
XS GIS Cut Line= 2
     3113635.445    13824073.794     3113251.728    13823654.719
#Sta/Elev= 30
       0   45.66    4.99   44.97    16.3   43.69   21.51   42.94   27.21   43.03
   42.75   43.95   49.42   44.12   77.31   43.17   97.65   43.17  106.45      43
  148.11   43.21  170.15   43.05  182.69   42.67  199.34    42.5  255.08   42.61
   329.4   41.73  339.79   41.34  352.29    40.6  371.87   39.61  382.38   40.12
  403.72   39.86  409.11   40.12  427.02   41.08  432.98    41.2  463.73   41.18
  493.66   41.34  504.41   41.73  521.96   43.21  534.12   43.53  568.21   43.57
#Mann= 4 ,-1 , 0
       0     .03       0  352.29    .013       0  409.11     .03       0
  534.12      99       0
#Block Obstruct= 1 ,-1
  534.12  568.21      80
Bank Sta=339.79,432.98
XS Rating Curve= 0 ,0
Exp/Cntr=0.3,0.1

Type RM Length L Ch R = 1 ,1063.487,141.84,145.72,148.46
XS GIS Cut Line= 2
       3113706.9    13823998.766     3113367.486    13823598.615
#Sta/Elev= 30
       0   43.65   15.73   43.61    35.4   42.81   72.24   42.75   82.88   42.57
  114.07   43.06  138.87   42.84  170.65   42.84  199.95   42.51  231.62    42.9
  253.16   42.62  295.73   42.76  317.01    42.6  330.43   42.32  341.21   41.95
  347.36   41.56   356.8   40.85  359.58   40.64  370.23   40.32  391.51   40.61
  404.03   40.57  412.79   40.53  433.41   41.28  440.32   41.36  455.36   41.31
  468.12   41.11  476.65   41.18  487.79    42.1  508.97   43.24  524.71    43.1
#Mann= 4 ,-1 , 0
       0     .03       0   356.8    .013       0  404.03     .03       0
  508.97      99       0
#Block Obstruct= 1 ,-1
  508.97  524.71      80
Bank Sta=347.36,433.41
XS Rating Curve= 0 ,0
Exp/Cntr=0.3,0.1