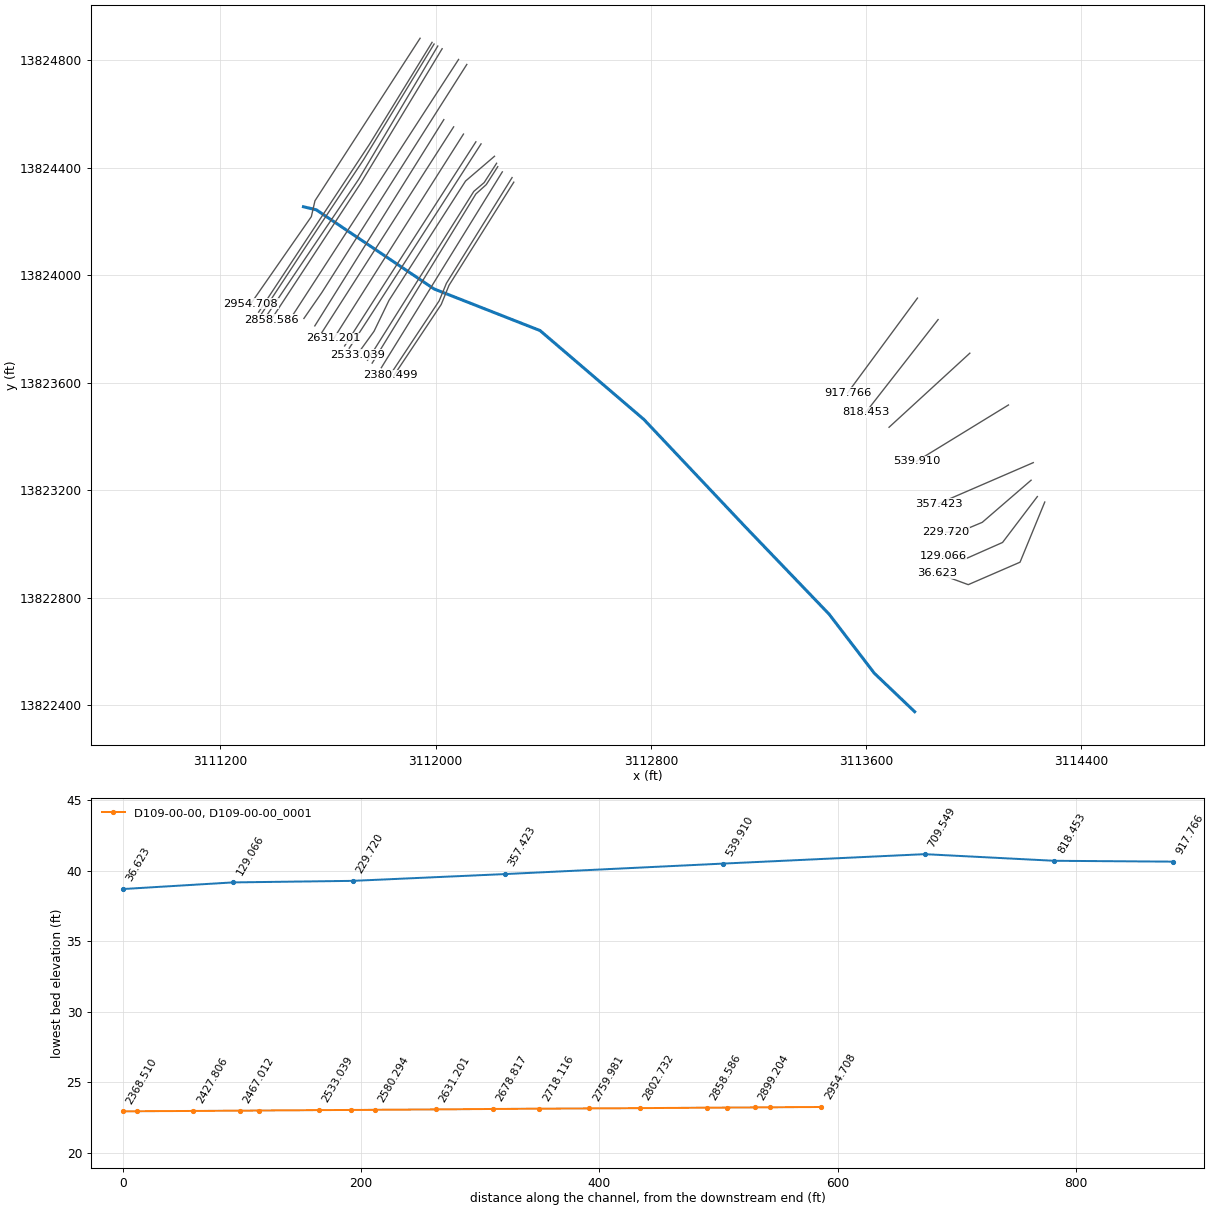
HEC-RAS study D109-00-00.prj: D109-00-00

--- D109-00-00.g01 (geometry) --- (continued)

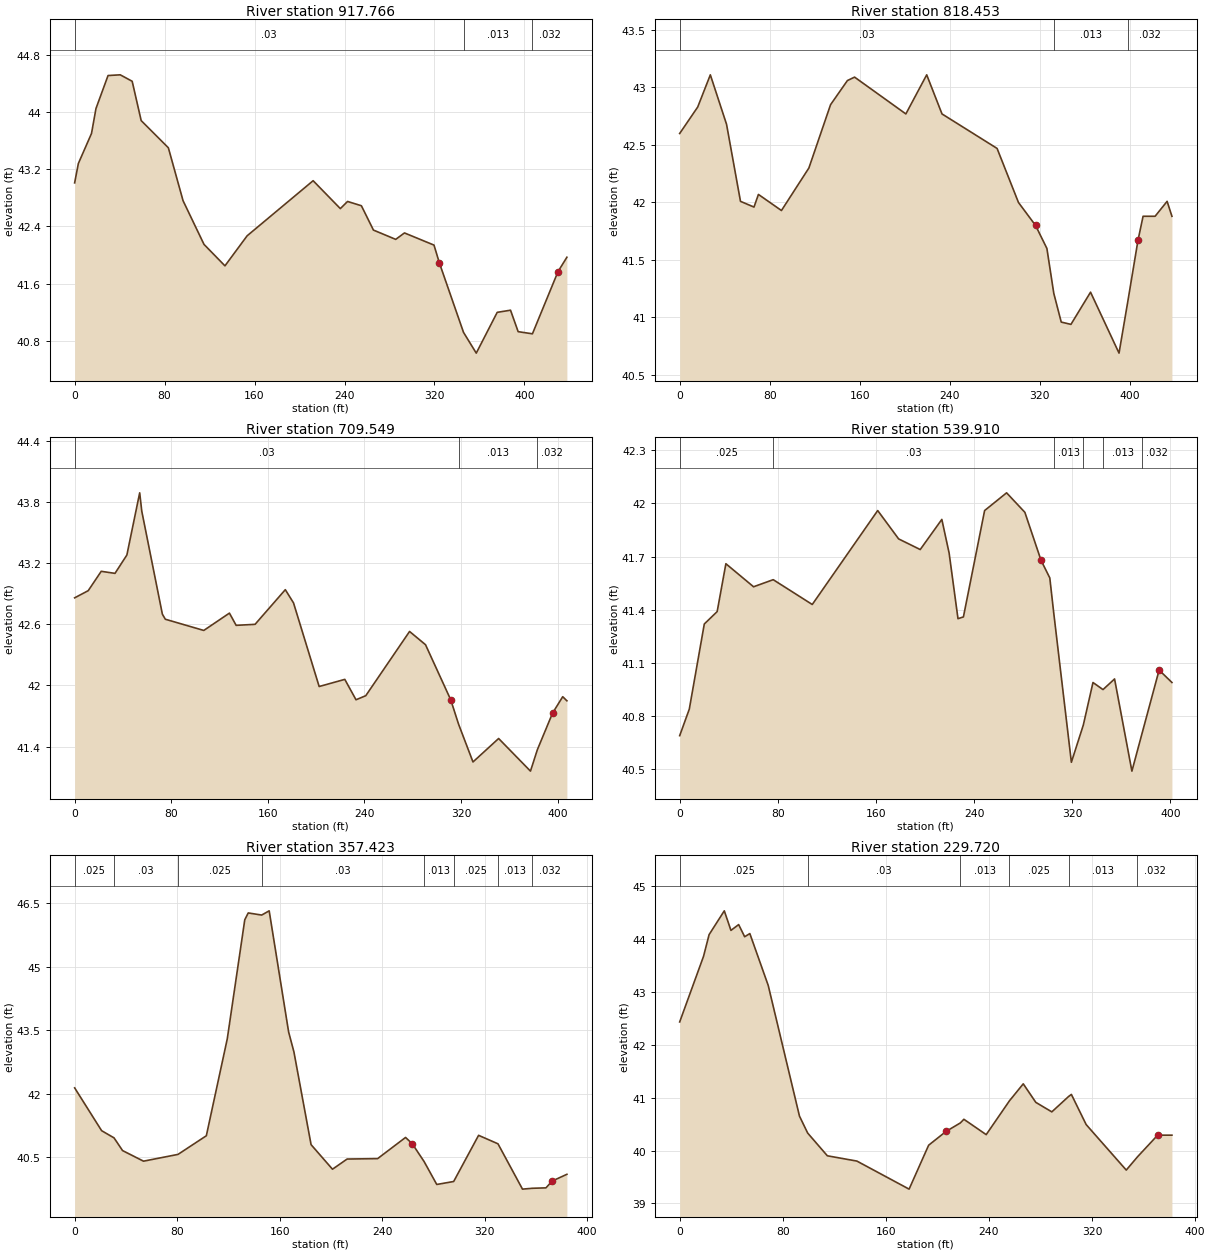
Type RM Length L Ch R = 1 ,917.766 ,101.27,99.31,98.25
XS GIS Cut Line= 2
     3113790.954    13823914.426     3113531.451    13823561.857
#Sta/Elev= 30
       0   43.01    3.29   43.28   14.98    43.7   18.98   44.05   29.71   44.51
   40.54   44.52   51.16   44.43   59.17   43.88   83.35    43.5   96.42   42.76
  115.04   42.15  133.67   41.85   153.4   42.27  212.09   43.04  236.28   42.65
  242.72   42.75  255.01   42.69  265.73   42.35  285.54   42.22  293.33   42.31
  319.58   42.14  324.39   41.89  345.84   40.92  357.17   40.63   375.8    41.2
  387.65   41.23  394.42   40.93  407.13    40.9  429.89   41.77  437.77   41.97
#Mann= 3 ,-1 , 0
       0     .03       0  345.84    .013       0  407.13    .032       0
Bank Sta=324.39,429.89
XS Rating Curve= 0 ,0
Exp/Cntr=0.3,0.1

Type RM Length L Ch R = 1 ,818.453 ,119.58,108.9,104.84
XS GIS Cut Line= 2
     3113867.675    13823834.418     3113598.718    13823489.117
#Sta/Elev= 30
       0    42.6   16.03   42.83   27.25   43.11   41.66   42.68   54.06   42.01
   66.07   41.96   70.01   42.07   90.48   41.93  114.89    42.3  134.14   42.85
  149.12   43.06  155.51   43.09  201.11   42.77  219.64   43.11  233.24   42.77
  282.22   42.47  301.23      42  316.45    41.8  326.52    41.6  332.64   41.21
  339.26   40.96   347.9   40.94  365.32   41.22  390.65   40.69   398.3   41.13
  407.49   41.67  412.03   41.88  422.72   41.88  433.41   42.01  437.69   41.88
#Mann= 3 ,-1 , 0
       0     .03       0  332.64    .013       0   398.3    .032       0
Bank Sta=316.45,407.49
XS Rating Curve= 0 ,0
Exp/Cntr=0.3,0.1

Type RM Length L Ch R = 1 ,709.549 ,183.36,169.64,165.39
XS GIS Cut Line= 2
     3113985.577    13823709.371      3113685.32    13823433.651
#Sta/Elev= 30
       0   42.86   11.23   42.93   22.01   43.12   33.41    43.1   43.25   43.28
   53.86   43.89   55.59   43.71   72.64    42.7   75.09   42.65  106.94   42.54
  128.18   42.71  133.74   42.59  149.41    42.6  174.46   42.94  181.26   42.81
  202.49   41.99  223.72   42.06  233.01   41.86  241.09    41.9  277.36   42.53
  290.58    42.4  311.44   41.86  317.96   41.62  329.88   41.25  351.12   41.48
  377.49   41.16  383.19   41.37  395.82   41.73   404.2   41.89  407.65   41.85
#Mann= 3 ,-1 , 0
       0     .03       0  317.96    .013       0  383.19    .032       0
Bank Sta=311.44,395.82
XS Rating Curve= 0 ,0
Exp/Cntr=0.3,0.1

Type RM Length L Ch R = 1 ,539.910 ,194.07,182.49,179.23
XS GIS Cut Line= 2
     3114129.169    13823516.702      3113787.23    13823306.739
#Sta/Elev= 30
       0   40.69    7.84   40.84   20.06   41.32   30.55   41.39   37.66   41.66
   60.21   41.53   76.24   41.57  108.07   41.43  161.42   41.96  178.48    41.8
  196.08   41.74  213.69   41.91  219.64   41.72  226.86   41.35  231.29   41.36
  248.57   41.96  266.49   42.06  281.38   41.95  294.52   41.68   301.7   41.58
  304.95   41.38   319.3   40.54  329.03   40.75   336.9   40.99  345.08   40.95
   354.5   41.01  368.63   40.49  377.18   40.71  390.82   41.06  401.26   40.99
#Mann= 6 ,-1 , 0
       0    .025       0   76.24     .03       0  304.95    .013       0
  329.03    .025       0  345.08    .013       0  377.18    .032       0
Bank Sta=294.52,390.82
XS Rating Curve= 0 ,0
Exp/Cntr=0.3,0.1

Type RM Length L Ch R = 1 ,357.423 ,123.2,127.7,114.46
XS GIS Cut Line= 2
      3114221.38    13823302.074     3113868.884    13823149.384
#Sta/Elev= 30
       0   42.14   21.04   41.13   30.73   40.96   37.39   40.66   53.73   40.41
   80.67   40.57  102.77   41.01  119.12    43.3  132.77   46.11  135.47   46.27
  145.98   46.22  151.81   46.32  166.99   43.46  171.12   42.99  184.51    40.8
  201.21   40.22  212.62   40.46  236.43   40.47  258.24   40.97  263.52   40.82
  272.74    40.4  282.59   39.86  295.79   39.93  315.24   41.02  330.37   40.82
  349.49   39.75  357.26   39.77  367.82   39.78  372.62   39.94  384.15    40.1
#Mann= 8 ,-1 , 0
       0    .025       0   30.73     .03       0   80.67    .025       0
  145.98     .03       0  272.74    .013       0  295.79    .025       0
  330.37    .013       0  357.26    .032       0
Bank Sta=263.52,372.62
XS Rating Curve= 0 ,0
Exp/Cntr=0.3,0.1

Type RM Length L Ch R = 1 ,229.720 ,99.85,100.65,92.79
XS GIS Cut Line= 4
     3114213.269    13823236.691     3114031.862    13823079.956
     3113949.141    13823045.126     3113896.655     13823043.13
#Sta/Elev= 30
       0   42.43   18.51   43.67   22.82   44.08   34.62   44.53   39.78   44.16
   45.76   44.27   50.42   44.04   54.44    44.1   68.71   43.12   92.96   40.65
   99.32   40.33  114.59    39.9  137.54    39.8  178.04   39.27  193.21    40.1
  206.67   40.36  217.75   40.52  220.58   40.59  237.88    40.3  255.95   40.94
  266.64   41.26  276.37   40.91   288.8   40.73  301.79   41.02  303.98   41.06
  315.46   40.49  346.57   39.63  355.28   39.88  370.94   40.29  382.02   40.29
#Mann= 6 ,-1 , 0
       0    .025       0   99.32     .03       0  217.75    .013       0
  255.95    .025       0  301.79    .013       0  355.28    .032       0
Bank Sta=206.67,370.94
XS Rating Curve= 0 ,0
Exp/Cntr=0.3,0.1

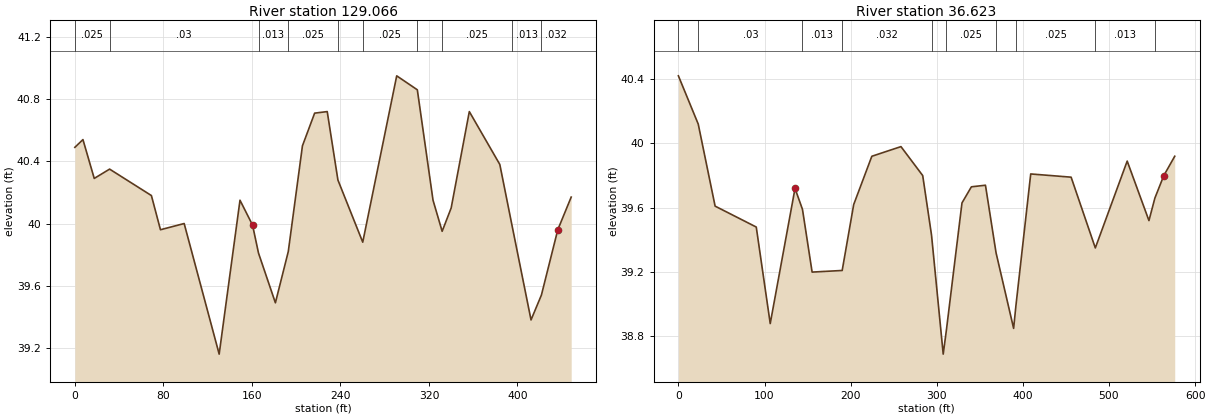
Type RM Length L Ch R = 1 ,129.066 ,75.39,92.44,69.79
XS GIS Cut Line= 4
     3114236.489    13823175.739      3114107.13    13823004.937
     3113965.105    13822942.087     3113886.995     13822953.78
#Sta/Elev= 30
       0   40.49    7.31   40.54   17.52   40.29    31.4   40.35   69.17   40.18
   77.37   39.96   98.78      40  130.42   39.16  149.24   40.15  160.58   39.99
  165.96   39.81  181.23   39.49  192.88   39.82  205.68    40.5   216.7   40.71
  228.07   40.72  237.73   40.28  260.16   39.88  290.87   40.95   309.5   40.86
  323.68   40.15  331.93   39.95  340.08    40.1  356.48   40.72  384.03   40.38
  394.72      40  412.25   39.38  421.64   39.54  436.44   39.96  448.55   40.17
#Mann= 10 ,-1 , 0
       0    .025       0    31.4     .03       0  165.96    .013       0
  192.88    .025       0  237.73    .013       0  260.16    .025       0
   309.5    .013       0  331.93    .025       0  394.72    .013       0
  421.64    .032       0
Bank Sta=160.58,436.44
XS Rating Curve= 0 ,0
Exp/Cntr=0.3,0.1

Type RM Length L Ch R = 1 ,36.623  ,56.2,36.62,44.02
XS GIS Cut Line= 4
     3114264.063    13823155.421     3114172.167    13822931.552
     3113979.696    13822847.965     3113862.847    13822890.994
#Sta/Elev= 30
       0   40.42   23.05   40.12   42.64   39.61   90.42   39.48  106.64   38.88
  135.44   39.72  144.09   39.59  155.28    39.2   190.2   39.21  203.58   39.62
  224.63   39.92  258.45   39.98  283.71    39.8  293.94   39.43  307.51   38.69
  311.23   38.84  329.31   39.63  340.22   39.73  356.57   39.74  368.87   39.32
  389.28   38.85  391.92   38.99  409.13   39.81  456.04   39.79  484.14   39.35
  521.15   39.89  546.41   39.52   553.3   39.66  563.67    39.8  576.35   39.92
#Mann= 10 ,-1 , 0
       0    .025       0   23.05     .03       0  144.09    .013       0
   190.2    .032       0  293.94    .013       0  311.23    .025       0
  368.87    .013       0  391.92    .025       0  484.14    .013       0
   553.3    .032       0
Bank Sta=135.44,563.67
XS Rating Curve= 0 ,0
Exp/Cntr=0.3,0.1

River Reach=D109-00-00      ,D109-00-00_0001
Reach XY= 30
     3111509.049    13824254.283     3111513.518    13824253.218
     3111542.536     13824246.31     3111556.821    13824242.908
      3111560.64     13824240.34     3111661.064    13824172.782
      3111695.15     13824149.85     3111742.073    13824118.285
     3111784.824    13824089.524     3111811.727    13824071.427
     3111829.661    13824059.361     3111870.672    13824031.773
     3111874.498    13824029.198     3111892.073    13824017.376
     3111994.739    13823948.309     3112388.296    13823793.616
     3112732.073    13823498.951     3112768.245    13823467.945
      3112774.46    13823462.619     3112874.463    13823356.554
     3113043.972    13823176.773     3113048.191    13823172.297
     3113092.073    13823125.757     3113147.388    13823067.088
     3113149.818    13823064.512     3113462.616    13822738.064
      3113630.39    13822518.537     3113655.176    13822494.876
     3113677.073    13822473.976     3113780.533    13822375.218

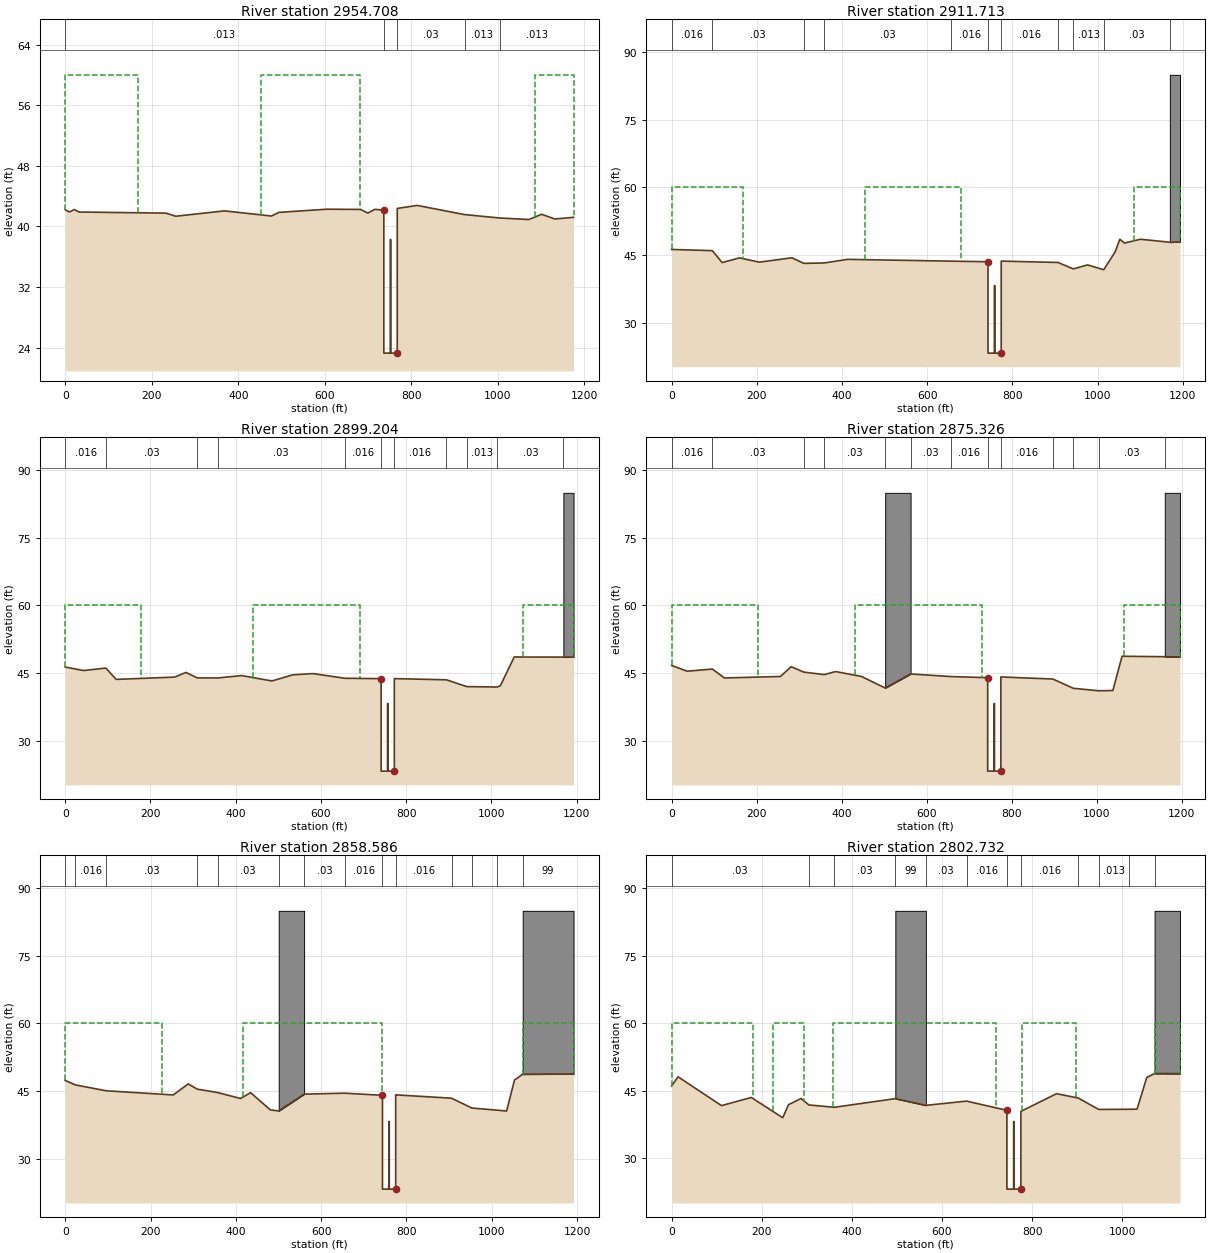
Type RM Length L Ch R = 1 ,2954.708,53.63,42.99,36.26
XS GIS Cut Line= 4
      3111942.59    13824881.392     3111551.848    13824276.544
     3111538.466    13824217.665     3111313.656    13823893.831
#Sta/Elev= 30
       0   42.19    9.97   41.89   20.82   42.22   31.67   41.89  233.07   41.74
  255.45   41.33  367.99   42.04  476.48   41.36  493.92   41.84  604.49   42.26
  682.62   42.23  699.55   41.75  715.06   42.24   736.2   42.15   736.3   42.15
   736.3   23.26   751.3   23.26   751.3   38.26   752.3   38.26   752.3   23.26
   767.3   23.26   767.3   42.36   767.4   42.36  813.39   42.76  922.95   41.55
 1003.88    41.1 1071.68    40.9 1100.88   41.59  1131.4   40.97 1174.68   41.19
#Mann= 5 ,-1 , 0
       0    .013       0   736.2    .011       0   767.4     .03       0
  922.95    .013       0 1003.88    .013       0
#XS Ineff= 3 ,-1
       0  167.07      60  453.47   680.2      60 1085.94 1174.68      60
Permanent Ineff=
       F       F       F
#XS Lid=8
   736.3   42.15   38.26  739.47    42.2   38.26  746.67   42.15   38.26
   751.8   42.19   38.26   758.1   42.24   38.26  762.05   42.34   38.26
  764.54   42.33   38.26   767.3   42.36   38.26
Bank Sta=736.3,767.3
XS Rating Curve= 0 ,0
Exp/Cntr=0.5,0.3

Type RM Length L Ch R = 1 ,2911.713,10.73,12.51,12.22
XS GIS Cut Line= 4
     3111987.086     13824866.13      3111865.78    13824668.375
     3111754.138    13824486.374     3111342.436    13823862.073
#Sta/Elev= 30
       0   46.25   95.47   45.98  118.54   43.33  158.97   44.38  205.79   43.43
  282.21    44.4  310.27   43.16     358   43.25  413.02   44.05  656.34   43.65
  742.51   43.52  742.61   43.52  742.61   23.24  757.61   23.24  757.61   38.24
  758.61   38.24  758.61   23.24  773.61   23.24  773.61   43.66  773.71   43.66
  906.94   43.36  942.74   41.93  976.29   42.82 1014.34   41.75 1041.26   45.73
 1052.09   48.52 1062.92   47.67 1100.44   48.51 1169.47   47.85 1193.34   47.94
#Mann= 11 ,-1 , 0
       0    .016       0   95.47     .03       0  310.27    .013       0
     358     .03       0  656.34    .016       0  742.51    .011       0
  773.71    .016       0  906.94     .03       0  942.74    .013       0
 1014.34     .03       0 1169.47      99       0
#XS Ineff= 3 ,-1
       0  167.07      60  453.47   680.2      60 1085.94 1193.34      60
Permanent Ineff=
       F       F       F
#Block Obstruct= 1 ,-1
 1169.47 1193.34      85
#XS Lid=6
  742.61   43.52   38.24  745.88   43.49   38.24  753.51   43.55   38.24
  759.74   43.61   38.24  763.85   43.59   38.24  773.61   43.66   38.24
Bank Sta=742.61,773.61
XS Rating Curve= 0 ,0
Exp/Cntr=0.5,0.3

Type RM Length L Ch R = 1 ,2899.204,19.61,23.88,22.07
XS GIS Cut Line= 4
     3111994.567    13824859.895     3111731.916    13824428.611
     3111520.653    13824110.295     3111352.598    13823854.812
#Sta/Elev= 30
       0   46.33   43.13   45.56   95.42    46.1  119.54   43.59  256.74    44.1
  283.26   45.13  310.13   43.92  357.84   43.91  414.25   44.44  485.05   43.24
  534.06    44.6  581.54   44.88  656.05   43.84  741.24   43.75  741.34   43.75
  741.34   23.23  756.34   23.23  756.34   38.23  757.34   38.23  757.34   23.23
  772.34   23.23  772.34   43.76  772.44   43.76  894.61    43.5  942.32   41.99
 1013.89    41.9 1021.13   42.18 1053.62   48.56 1168.95   48.54 1192.81   48.55
#Mann= 11 ,-1 , 0
       0    .016       0   95.42     .03       0  310.13    .013       0
  357.84     .03       0  656.05    .016       0  741.24    .011       0
  772.44    .016       0  894.61     .03       0  942.32    .013       0
 1013.89     .03       0 1168.95      99       0
#XS Ineff= 3 ,-1
       0  178.92      60  441.34  691.83      60 1073.53 1192.81      60
Permanent Ineff=
       F       F       F
#Block Obstruct= 1 ,-1
 1168.95 1192.81      85
#XS Lid=7
  741.34   43.75   38.23  741.93   43.76   38.23  746.24   43.79   38.23
  761.31   43.79   38.23  771.42   43.76   38.23  771.75   43.76   38.23
  772.34   43.76   38.23
Bank Sta=741.34,772.34
XS Rating Curve= 0 ,0
Exp/Cntr=0.5,0.3

Type RM Length L Ch R = 1 ,2875.326,16.19,16.74,19.45
XS GIS Cut Line= 3
     3112008.283    13824852.414     3111713.794    13824355.736
      3111368.01    13823842.892
#Sta/Elev= 30
       0   46.67   36.68    45.4   95.68   45.88  124.15    43.9  255.81   44.23
   281.1    46.4  310.95    45.2  358.78   44.65  385.73   45.32  446.06   44.25
   502.3   41.67  562.09   44.79  657.77   44.21  743.37   43.96  743.47   43.96
  743.47   23.22  758.47   23.22  758.47   38.22  759.47   38.22  759.47   23.22
  774.47   23.22  774.47   44.13  774.57   44.13  896.96   43.66   944.8   41.61
 1004.59   41.06 1037.98   41.11 1059.59   48.72 1160.07   48.62 1195.95   48.57
#Mann= 13 ,-1 , 0
       0    .016       0   95.68     .03       0  310.95    .013       0
  358.78     .03       0   502.3      99       0  562.09     .03       0
  657.77    .016       0  743.37    .011       0  774.57    .016       0
  896.96     .03       0   944.8    .013       0 1004.59     .03       0
 1160.07      99       0
#XS Ineff= 3 ,-1
       0  203.31      60  430.54  729.53      60 1064.39 1195.95      60
Permanent Ineff=
       F       F       F
#Block Obstruct= 2 ,-1
   502.3  562.09      85 1160.07 1195.95      85
#XS Lid=4
  743.47   43.96   38.22  744.12   43.97   38.22  764.34   43.97   38.22
  774.47   44.13   38.22
Bank Sta=743.47,774.47
XS Rating Curve= 0 ,0
Exp/Cntr=0.5,0.3

Type RM Length L Ch R = 1 ,2858.586,62.52,55.85,56.99
XS GIS Cut Line= 3
     3112024.492    13824842.439       3111723.4    13824344.209
     3111389.322    13823834.367
#Sta/Elev= 30
       0   47.34   23.83   46.35   95.34   45.05  253.33   44.12  288.39   46.57
  309.84    45.4  357.51   44.65  411.07   43.33   434.6   44.63  481.18   40.79
  500.51   40.57  560.09    44.3  655.43   44.51  743.63   44.04  743.73   44.04
  743.73   23.21  758.73   23.21  758.73   38.21  759.73   38.21  759.73   23.21
  774.73   23.21  774.73   44.14  774.83   44.14  905.68    43.4  953.35   41.21
 1012.94   40.74 1034.77   40.55 1053.37   47.44 1072.52   48.72 1191.69   48.78
#Mann= 14 ,-1 , 0
       0     .03       0   23.83    .016       0   95.34     .03       0
  309.84    .013       0  357.51     .03       0  500.51      99       0
  560.09     .03       0  655.43    .016       0  743.63    .011       0
  774.83    .016       0  905.68     .03       0  953.35    .013       0
 1012.94     .03       0 1072.52      99       0
#XS Ineff= 3 ,-1
       0  226.42      60  417.09  743.63      60 1072.52 1191.69      60
Permanent Ineff=
       F       F       F
#Block Obstruct= 2 ,-1
  500.51  560.09      85 1072.52 1191.69      85
#XS Lid=6
  743.73   44.04   38.21  753.34   44.03   38.21  757.53   44.06   38.21
   762.7   44.06   38.21  765.77   44.11   38.21  774.73   44.14   38.21
Bank Sta=743.73,774.73
XS Rating Curve= 0 ,0
Exp/Cntr=0.5,0.3

Type RM Length L Ch R = 1 ,2802.732,38.87,42.75,44.66
XS GIS Cut Line= 2
      3112085.59    13824802.538     3111472.438    13823855.679
#Sta/Elev= 30
       0   46.11    14.2   48.13  110.59   41.73  176.65   43.54  246.51   39.04
  259.44   41.94  287.03   43.31  304.57   41.88  360.98   41.36  496.34   43.28
  564.03   41.79  654.27   42.73  743.83   40.69  743.93   40.69  743.93   23.18
  758.93   23.18  758.93   38.18  759.93   38.18  759.93   23.18  774.93   23.18
  774.93   40.45  775.03   40.45  854.11   44.38  902.44   43.41  947.56   40.88
 1015.24   40.92 1032.81   40.94 1054.24   47.99 1071.65   48.86 1128.05   48.83
#Mann= 12 ,-1 , 0
       0     .03       0  304.57    .013       0  360.98     .03       0
  496.34      99       0  564.03     .03       0  654.27    .016       0
  743.83    .011       0  775.03    .016       0  902.44     .03       0
  947.56    .013       0 1015.24     .03       0 1071.65      99       0
#XS Ineff= 5 ,-1
       0  179.61      60  224.51  294.07      60  358.52     720      60
  776.85  898.06      60 1071.65 1128.05      60
Permanent Ineff=
       F       F       F       F       F
#Block Obstruct= 2 ,-1
  496.34  564.03      85 1071.65 1128.05      85
#XS Lid=6
  743.93   40.69   38.18  747.01   40.55   38.18  750.49   40.65   38.18
  755.88   40.27   38.18  764.87   40.24   38.18  774.93   40.45   38.18
Bank Sta=743.93,774.93
XS Rating Curve= 0 ,0
Exp/Cntr=0.9,0.9

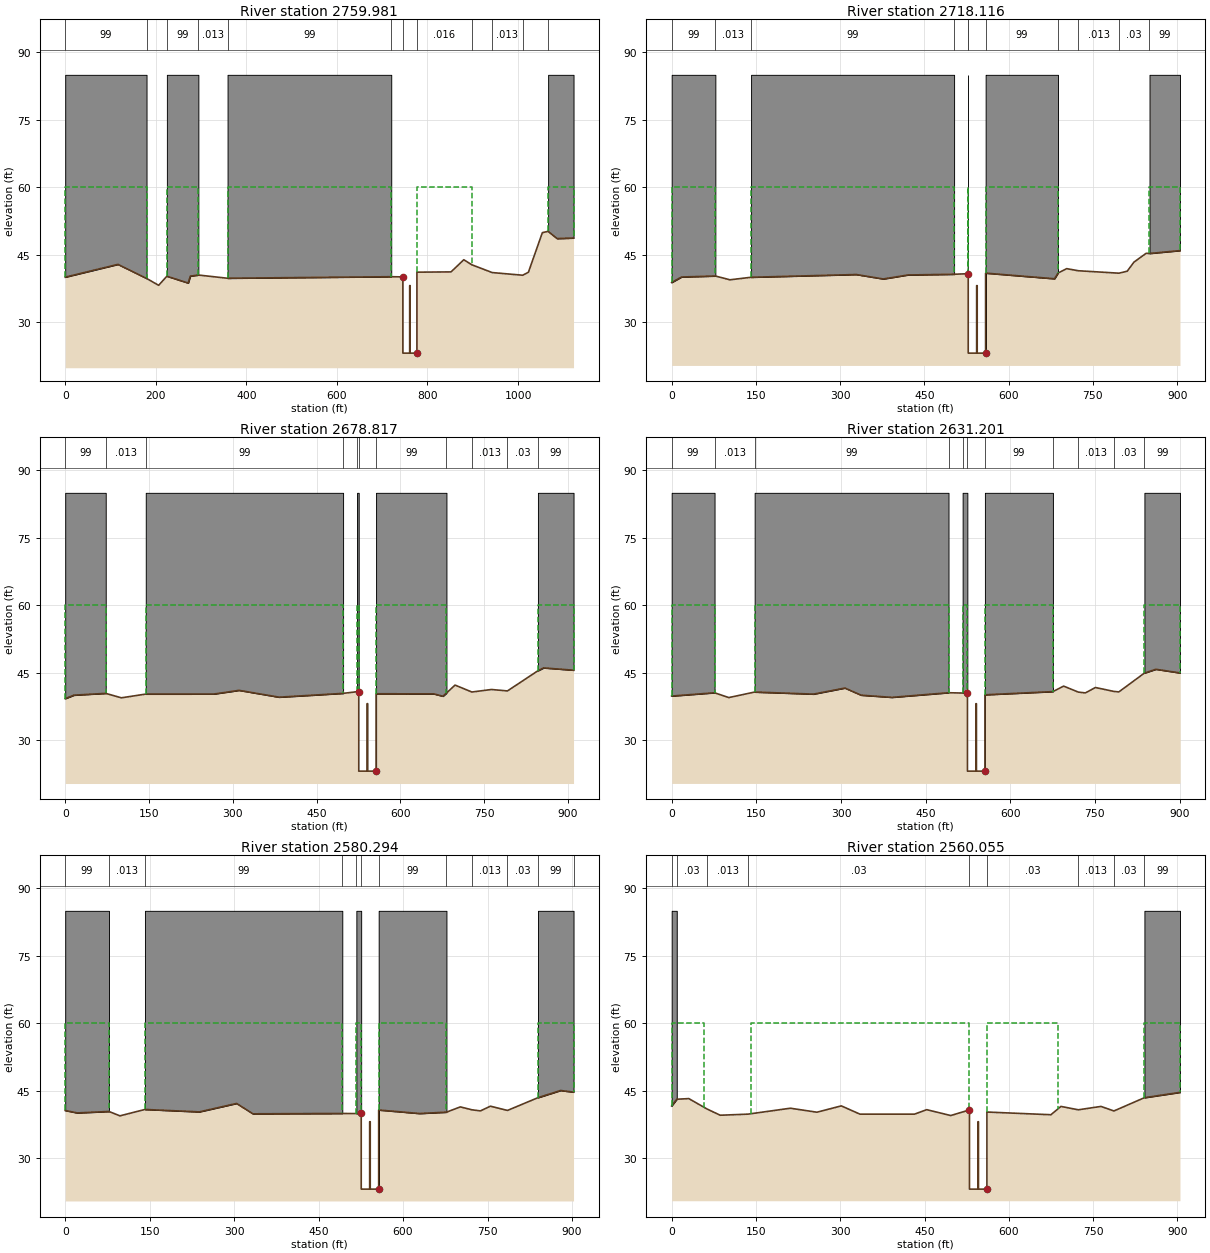
Type RM Length L Ch R = 1 ,2759.981,38.79,41.87,43.34
XS GIS Cut Line= 3
     3112116.144    13824783.906     3111577.393    13823935.005
     3111510.799     13823838.63
#Sta/Elev= 30
       0   40.04  116.41   42.88  179.61   39.76  206.39   38.23  224.51   40.25
   271.6   38.73   276.3   40.27  294.07   40.51  358.52    39.8     720   40.14
  745.65    40.1  745.75    40.1  745.75   23.16  760.75   23.16  760.75   38.16
  761.75   38.16  761.75   23.16  776.75   23.16  776.75   41.15  776.85   41.15
  852.06   41.21  880.23   43.91  898.06   42.79  942.96   41.06 1010.32   40.47
 1022.91   41.13 1053.74   49.93 1066.44   50.22 1086.08   48.62 1122.57   48.73
#Mann= 12 ,-1 , 0
       0      99       0  179.61     .03       0  224.51      99       0
  294.07    .013       0  358.52      99       0     720    .016       0
  745.65    .011       0  776.85    .016       0  898.06     .03       0
  942.96    .013       0 1010.32     .03       0 1066.44      99       0
#XS Ineff= 5 ,-1
       0  179.61      60  224.51  294.07      60  358.52     720      60
  776.85  898.06      60 1066.44 1122.57      60
Permanent Ineff=
       F       F       F       F       F
#Block Obstruct= 4 ,-1
       0  179.61      85  224.51  294.07      85  358.52     720      85
 1066.44 1122.57      85
#XS Lid=6
  745.75    40.1   38.16  749.78   40.19   38.16  756.05   40.35   38.16
  767.91   40.96   38.16  773.81   41.13   38.16  776.75   41.15   38.16
Bank Sta=745.75,776.75
XS Rating Curve= 0 ,0
Exp/Cntr=0.5,0.3

Type RM Length L Ch R = 1 ,2718.116,44.02,39.3,37.03
XS GIS Cut Line= 2
     3112030.784    13824578.589     3111551.291    13823810.925
#Sta/Elev= 30
       0   38.84   17.55   40.06   77.79   40.28  103.72   39.44   141.4      40
  328.58   40.61  376.79   39.62  420.33   40.51  502.88   40.67  527.88    40.8
  527.92    40.8  528.02    40.8  528.02   23.14  543.02   23.14  543.02   38.14
  544.02   38.14  544.02   23.14  559.02   23.14  559.02   40.92  559.12   40.92
   681.6   39.67  687.88   40.93  703.37   41.92  724.09   41.45   796.5   40.91
  811.14   41.35  823.12   43.37  844.89   45.33   850.8   45.29  905.11   45.93
#Mann= 11 ,-1 , 0
       0      99       0   77.79    .013       0   141.4      99       0
  502.88     .03       0  527.88      99       0  527.92    .011       0
  559.12      99       0  687.88     .03       0  724.09    .013       0
   796.5     .03       0   850.8      99       0
#XS Ineff= 5 ,-1
       0   77.79      60   141.4  502.88      60  527.88  527.92      60
  559.12  687.88      60   850.8  905.11      60
Permanent Ineff=
       F       F       F       F       F
#Block Obstruct= 5 ,-1
       0   77.79      85   141.4  502.88      85  527.88  528.02      85
  559.02  687.88      85   850.8  905.11      85
#XS Lid=2
  528.02      85   38.14  559.02      85   38.14
Bank Sta=528.02,559.02
XS Rating Curve= 0 ,0
Exp/Cntr=0.3,0.1

Type RM Length L Ch R = 1 ,2678.817,45.73,47.62,48.5
XS GIS Cut Line= 2
     3112067.285    13824551.693     3111576.865     13823785.35
#Sta/Elev= 30
       0   39.24   15.67   40.01   72.51   40.41  100.47   39.42  144.17   40.25
  266.13   40.26  311.14   41.08  382.81   39.56  497.37   40.41  522.37   40.78
   525.3   40.71   525.4   40.71   525.4   23.12   540.4   23.12   540.4   38.12
   541.4   38.12   541.4   23.12   556.4   23.12   556.4   40.32   556.5   40.32
  659.52    40.3  676.01   39.77  682.37   40.47  697.73   42.25  727.87   40.71
  762.89   41.27  791.55   40.95  846.14   45.44  856.08   46.07  909.83   45.56
#Mann= 11 ,-1 , 0
       0      99       0   72.51    .013       0  144.17      99       0
  497.37     .03       0  522.37      99       0   525.3    .011       0
   556.5      99       0  682.37     .03       0  727.87    .013       0
  791.55     .03       0  846.14      99       0
#XS Ineff= 5 ,-1
       0   72.51      60  144.17  497.37      60  522.37   525.3      60
   556.5  682.37      60  846.14  909.83      60
Permanent Ineff=
       F       F       F       F       F
#Block Obstruct= 5 ,-1
       0   72.51      85  144.17  497.37      85  522.37   525.3      85
   556.4  682.37      85  846.11  909.83      85
#XS Lid=2
   525.4      85   38.12   556.4      85   38.12
Bank Sta=525.4,556.4
XS Rating Curve= 0 ,0
Exp/Cntr=0.3,0.1

Type RM Length L Ch R = 1 ,2631.201,53.74,50.91,49.77
XS GIS Cut Line= 2
     3112103.787    13824524.797      3111621.62    13823764.039
#Sta/Elev= 30
       0   39.79   75.98   40.52  101.27   39.45  147.02   40.68  251.44   40.22
  306.85   41.57   335.8   39.98  390.15    39.5  490.52   40.53  515.52   40.46
  523.91   40.42  524.01   40.42  524.01   23.09  539.01   23.09  539.01   38.09
  540.01   38.09  540.01   23.09  555.01   23.09  555.01   40.07  555.11   40.07
  675.52   40.78   694.5      42  720.55   40.67  733.06   40.49  750.82   41.69
   783.6   40.82  792.33   40.71  837.64    44.9  857.81   45.75  900.69   44.93
#Mann= 11 ,-1 , 0
       0      99       0   75.98    .013       0  147.02      99       0
  490.52     .03       0  515.52      99       0  523.91    .011       0
  555.11      99       0  675.52     .03       0  720.55    .013       0
   783.6     .03       0  837.64      99       0
#XS Ineff= 5 ,-1
       0   75.98      60  147.02  490.52      60  515.52  523.91      60
  555.11  675.52      60  837.64  900.69      60
Permanent Ineff=
       F       F       F       F       F
#Block Obstruct= 5 ,-1
       0   75.98      85  147.02  490.52      85  515.52  523.91      85
  555.01  675.52      85  837.64  900.69      85
#XS Lid=2
  524.01      85   38.09  555.01      85   38.09
Bank Sta=524.01,555.01
XS Rating Curve= 0 ,0
Exp/Cntr=0.3,0.1

Type RM Length L Ch R = 1 ,2580.294,20.32,20.24,20.02
XS GIS Cut Line= 3
     3112149.895     13824495.98     3111804.088    13823958.058
     3111662.112    13823736.334
#Sta/Elev= 30
       0   40.56   21.33   40.02    77.7   40.34   97.18   39.37   141.6   40.79
  238.19   40.25  304.41   42.13  333.33   39.82  492.08    39.9  517.08   39.87
  525.62    39.9  525.72    39.9  525.72   23.06  540.72   23.06  540.72   38.06
  541.72   38.06  541.72   23.06  556.72   23.06  556.72   40.67  556.82   40.67
  629.34   39.89  677.08   40.19  701.75   41.36  722.22   40.72  737.38   40.47
  755.19   41.52  785.41   40.57  839.58   43.41  879.79   45.01  902.77   44.65
#Mann= 12 ,-1 , 0
       0      99       0    77.7    .013       0   141.6      99       0
  492.08     .03       0  517.08      99       0  525.62    .011       0
  556.82      99       0  677.08     .03       0  722.22    .013       0
  785.41     .03       0  839.58      99       0  902.77     .03       0
#XS Ineff= 5 ,-1
       0    77.7      60   141.6  492.08      60  517.08  525.62      60
  556.82  677.08      60  839.58  902.77      60
Permanent Ineff=
       F       F       F       F       F
#Block Obstruct= 5 ,-1
       0    77.7      85   141.6  492.08      85  517.08  525.62      85
  556.72  677.08      85  839.58  902.77      85
#XS Lid=2
  525.72      85   38.06  556.72      85   38.06
Bank Sta=525.72,556.72
XS Rating Curve= 0 ,0
Exp/Cntr=0.3,0.1

Type RM Length L Ch R = 1 ,2560.055,37.38,27.02,36.03
XS GIS Cut Line= 3
     3112169.106    13824488.295     3111750.296    13823837.026
     3111679.162    13823727.809
#Sta/Elev= 30
       0   41.56    9.05   43.06   30.54    43.2   63.33   40.86    86.4    39.5
   135.7   39.74  211.24   41.06  258.47   40.17  301.89   41.58  335.07   39.74
  432.14   39.74  453.85   40.74  496.58   39.43   529.9   40.68     530   40.68
     530   23.05     545   23.05     545   38.05     546   38.05     546   23.05
     561   23.05     561   40.21   561.1   40.21  674.92   39.61  692.75   41.46
  723.72   40.71  764.09   41.46  787.04   40.45  841.32    43.4  904.65   44.59
#Mann= 9 ,-1 , 0
       0      99       0    9.05     .03       0   63.33    .013       0
   135.7     .03       0   529.9    .011       0   561.1     .03       0
  723.72    .013       0  787.04     .03       0  841.32      99       0
#XS Ineff= 4 ,-1
       0   58.33      60   140.7   529.9      60   561.1  687.53      60
  841.32  904.65      60
Permanent Ineff=
       F       F       F       F
#Block Obstruct= 2 ,-1
       0    9.05      85  841.32  904.65      85
#XS Lid=6
     530   40.68   38.05  532.25   40.58   38.05  543.41   40.16   38.05
  550.08   39.87   38.05  553.79   39.85   38.05     561   40.21   38.05
Bank Sta=530,561
XS Rating Curve= 0 ,0
Exp/Cntr=0.3,0.1

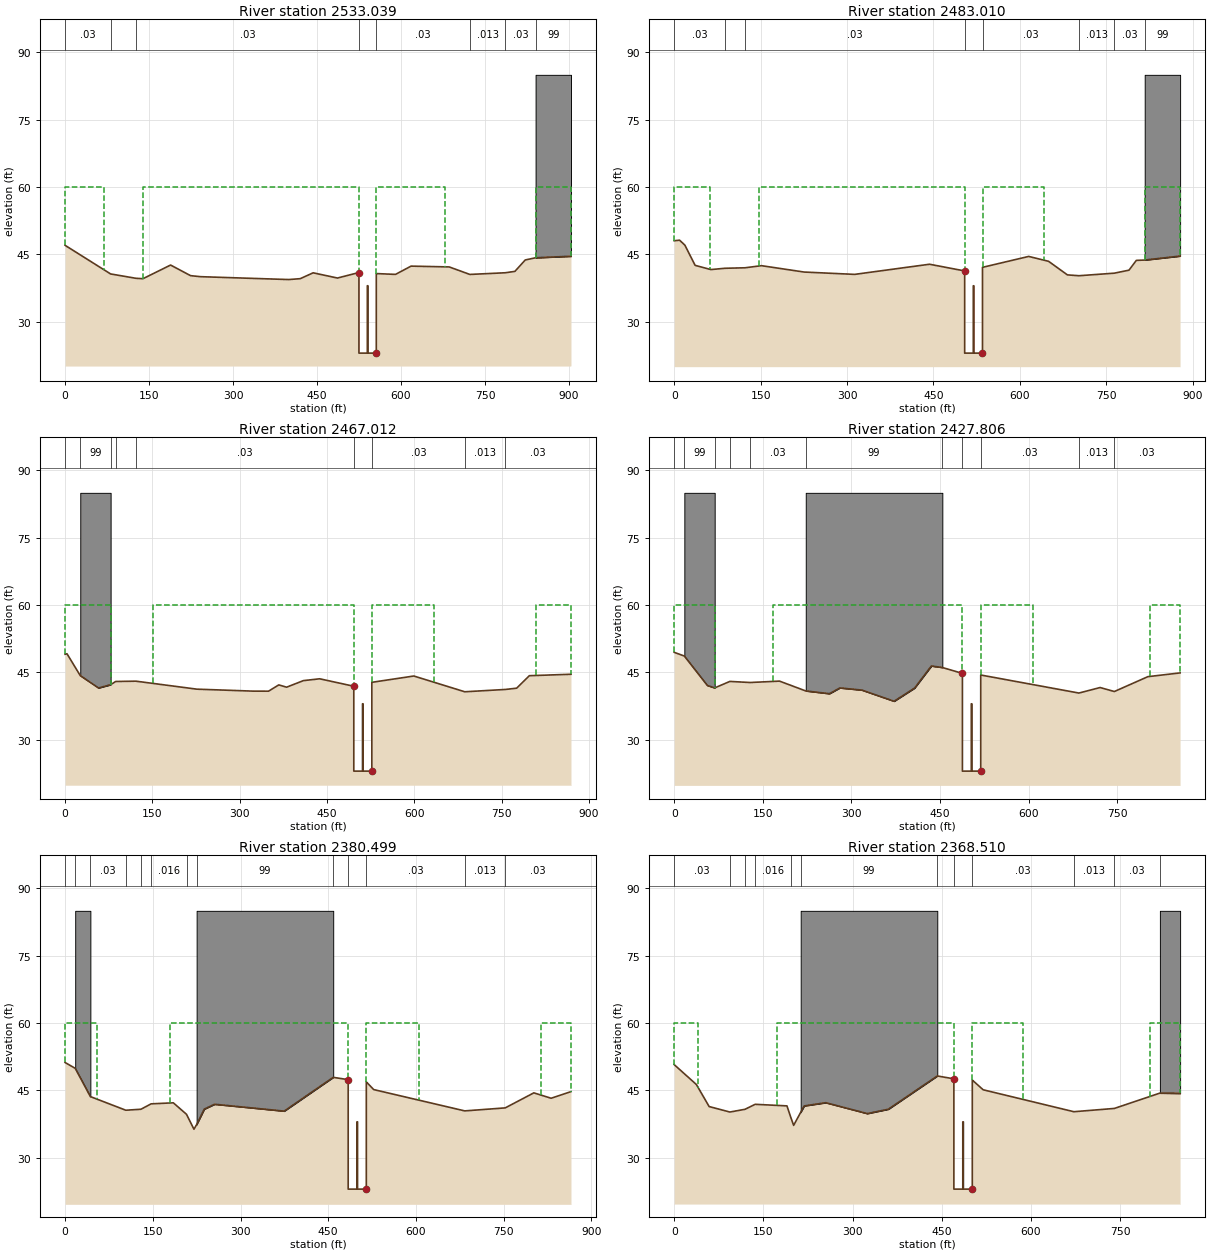
Type RM Length L Ch R = 1 ,2533.039,49.33,50.03,43.23
XS GIS Cut Line= 5
     3112219.056    13824442.188     3112111.472    13824349.973
     3111827.142    13823906.187     3111771.429    13823790.919
     3111708.998    13823704.366
#Sta/Elev= 30
       0   47.04   81.31   40.67  126.49    39.7  139.04   39.61  188.43   42.65
  224.06   40.29  241.88   40.06  399.57   39.42  420.02   39.62  443.01   40.92
  486.44   39.76  524.69   40.98  524.79   40.98  524.79   23.04  539.79   23.04
  539.79   38.04  540.79   38.04  540.79   23.04  555.79   23.04  555.79   40.75
  555.89   40.75   590.1   40.57  617.91   42.41  686.04   42.23   722.8   40.56
  786.04   40.93  803.31   41.24  821.81   43.78  840.25   44.27   903.5   44.61
#Mann= 8 ,-1 , 0
       0     .03       0   81.31    .013       0  126.49     .03       0
  524.69    .011       0  555.89     .03       0   722.8    .013       0
  786.04     .03       0  840.25      99       0
#XS Ineff= 4 ,-1
       0   69.31      60  138.49  524.69      60  555.89  677.62      60
  840.25   903.5      60
Permanent Ineff=
       F       F       F       F
#Block Obstruct= 1 ,-1
  840.25   903.5      85
#XS Lid=6
  524.79   40.98   38.04  526.91   41.06   38.04  529.87   41.18   38.04
  534.49   41.15   38.04  551.59   40.75   38.04  555.79   40.75   38.04
Bank Sta=524.79,555.79
XS Rating Curve= 0 ,0
Exp/Cntr=0.3,0.1

Type RM Length L Ch R = 1 ,2483.010,11.33,16,18.25
XS GIS Cut Line= 4
     3112226.873    13824416.177     3112180.633    13824344.209
      3112142.21     13824311.55     3111747.359    13823683.054
#Sta/Elev= 30
       0   48.04     9.3   48.17   18.49   47.07   36.32   42.56   63.58   41.62
   87.82   41.91  122.95   42.02  151.47   42.49  225.52   41.07  313.23   40.55
  443.18   42.81  504.05   41.32  504.15   41.32  504.15   23.01  519.15   23.01
  519.15   38.01  520.15   38.01  520.15   23.01  535.15   23.01  535.15   42.12
  535.25   42.12  615.36   44.55  649.89   43.46  682.53   40.44  702.56   40.25
  764.04   40.82  789.45   41.49  802.21   43.67  816.73   43.74  878.21   44.63
#Mann= 8 ,-1 , 0
       0     .03       0   87.82    .013       0  122.95     .03       0
  504.05    .011       0  535.25     .03       0  702.56    .013       0
  764.04     .03       0  816.73      99       0
#XS Ineff= 4 ,-1
       0   62.82      60  147.95  504.05      60  535.25  641.09      60
  816.73  878.21      60
Permanent Ineff=
       F       F       F       F
#Block Obstruct= 1 ,-1
  816.73  878.21      85
#XS Lid=7
  504.15   41.32   38.01  507.49   41.27   38.01  509.07   41.29   38.01
  511.76   41.35   38.01  526.79   41.79   38.01  530.22   42.01   38.01
  535.15   42.12   38.01
Bank Sta=504.15,535.15
XS Rating Curve= 0 ,0
Exp/Cntr=0.3,0.1

Type RM Length L Ch R = 1 ,2467.012,32.18,39.21,38.53
XS GIS Cut Line= 4
     3112231.135     13824403.39     3112188.318    13824336.525
     3112149.895    13824301.944     3111764.408    13823672.398
#Sta/Elev= 30
       0   49.04    3.29   49.15   26.08   44.28   57.43   41.53   78.24   42.25
   86.93   42.97   121.7   43.04  226.45   41.26   323.2   40.82  349.57   40.81
  367.16   42.21  380.65    41.7  409.38   43.16  437.51   43.57  495.98   41.91
  496.08   41.91  496.08      23  511.08      23  511.08      38  512.08      38
  512.08      23  527.08      23  527.08   42.79  527.42   42.79  599.24   44.19
  686.74   40.68  756.28   41.19  775.91   41.48  797.73   44.26  869.28   44.58
#Mann= 9 ,-1 , 0
       0     .03       0   26.08      99       0   78.24     .03       0
   86.93    .013       0   121.7     .03       0  495.98    .011       0
  527.42     .03       0  686.74    .013       0  756.28     .03       0
#XS Ineff= 4 ,-1
       0   78.24      60   150.7  495.98      60  527.18  634.58      60
  808.43  869.28      60
Permanent Ineff=
       F       F       F       F
#Block Obstruct= 1 ,-1
   26.08   78.24      85
#XS Lid=7
  496.08   41.91      38  507.87   42.07      38   514.1   42.27      38
  524.28   42.74      38  525.01   42.78      38  525.46   42.79      38
  527.08   42.79      38
Bank Sta=496.08,527.08
XS Rating Curve= 0 ,0
Exp/Cntr=0.3,0.1

Type RM Length L Ch R = 1 ,2427.806,41.82,47.31,47.05
XS GIS Cut Line= 2
     3112248.184     13824384.21     3111798.507    13823655.349
#Sta/Elev= 30
       0   49.45   17.13   48.63    56.1   42.07   68.51   41.53   94.21   42.97
  128.46   42.73  178.28   43.04  222.67   40.85  262.72   40.24  280.34   41.52
   317.7   41.04   372.2   38.55  406.83   41.48  435.39   46.41   453.9   46.07
   487.8   44.77   487.9   44.77   487.9   22.98   502.9   22.98   502.9   37.98
   503.9   37.98   503.9   22.98   518.9   22.98   518.9    44.4     519    44.4
  685.13   40.38  720.97   41.61  745.08   40.72  801.81   44.03  856.42   44.87
#Mann= 11 ,-1 , 0
       0     .03       0   17.13      99       0   68.51     .03       0
   94.21    .013       0  128.46     .03       0  222.67      99       0
   453.9     .03       0   487.8    .011       0     519     .03       0
  685.13    .013       0  745.08     .03       0
#XS Ineff= 4 ,-1
       0   68.51      60  167.46   487.8      60     519  608.06      60
  805.03  856.42      60
Permanent Ineff=
       F       F       F       F
#Block Obstruct= 2 ,-1
   17.13   68.51      85  222.67   453.9      85
#XS Lid=6
   487.9   44.77   37.98  491.84   44.72   37.98  492.53    44.7   37.98
  503.01   44.53   37.98  509.47   44.71   37.98   518.9    44.4   37.98
Bank Sta=487.9,518.9
XS Rating Curve= 0 ,0
Exp/Cntr=0.3,0.1

Type RM Length L Ch R = 1 ,2380.499,14,11.99,13.43
XS GIS Cut Line= 4
     3112284.414    13824362.898     3112040.389    13823969.585
     3112013.493    13823904.266     3111830.475    13823627.644
#Sta/Elev= 30
       0   51.19    17.3   49.89   43.26   43.59  103.82   40.55  129.78   40.77
  147.08   41.97  185.09    42.2  207.65   39.64  220.39   36.31  224.95   37.34
  238.05    40.8   255.7   41.88  374.73   40.35  458.55   47.88  484.05   47.37
  484.15   47.37  484.15   22.96  499.15   22.96  499.15   37.96  500.15   37.96
  500.15   22.96  515.15   22.96  515.15   46.85  515.25   46.85  527.81   45.15
   683.5    40.4  752.71   41.07  801.67   44.42  831.22   43.22  865.19    44.7
#Mann= 13 ,-1 , 0
       0     .03       0    17.3      99       0   43.26     .03       0
  103.82    .013       0  129.78     .03       0  147.08    .016       0
  207.65     .03       0  224.95      99       0  458.55     .03       0
  484.05    .011       0  515.25     .03       0   683.5    .013       0
  752.71     .03       0
#XS Ineff= 4 ,-1
       0   53.82      60  179.78  484.05      60  515.25  605.63      60
  813.28  865.19      60
Permanent Ineff=
       F       F       F       F
#Block Obstruct= 2 ,-1
    17.3   43.26      85  224.95  458.55      85
#XS Lid=5
  484.15   47.37   37.96  493.34    47.3   37.96  499.59   47.24   37.96
  514.61   46.85   37.96  515.15   46.85   37.96
Bank Sta=484.15,515.15
XS Rating Curve= 0 ,0
Exp/Cntr=0.3,0.1

Type RM Length L Ch R = 1 ,2368.510,39.43,45.31,42.62
XS GIS Cut Line= 4
     3112290.808    13824345.849     3112049.995    13823961.901
     3112021.178    13823890.818     3111843.262    13823623.381
#Sta/Elev= 30
       0   50.71   37.33   46.27   58.78   41.36   93.62   40.14  119.16   40.75
  136.18   41.86  189.67   41.51  195.76   39.09  200.94   37.17  212.78   40.07
  218.65    41.5  254.96   42.22  324.88   39.79   360.3   40.77  442.59   48.18
   470.4   47.55   470.5   47.55   470.5   22.95   485.5   22.95   485.5   37.95
   486.5   37.95   486.5   22.95   501.5   22.95   501.5   47.25   501.6   47.25
  519.79    45.1  672.39   40.21  740.48   40.94  817.09   44.36  851.13    44.3
#Mann= 12 ,-1 , 0
       0     .03       0   93.62    .013       0  119.16     .03       0
  136.18    .016       0  195.76     .03       0  212.78      99       0
  442.59     .03       0   470.4    .011       0   501.6     .03       0
  672.39    .013       0  740.48     .03       0  817.09      99       0
#XS Ineff= 4 ,-1
       0   40.62      60  172.16   470.4      60   501.6  587.28      60
  800.06  851.13      60
Permanent Ineff=
       F       F       F       F
#Block Obstruct= 2 ,-1
  212.78  442.59      85  817.09  851.13      85
#XS Lid=7
   470.5   47.55   37.95  473.72   47.52   37.95  481.58    47.5   37.95
  494.27    47.7   37.95  497.76   47.69   37.95  500.14    47.4   37.95
   501.5   47.25   37.95
Bank Sta=470.5,501.5
XS Rating Curve= 0 ,0
Exp/Cntr=0.3,0.1