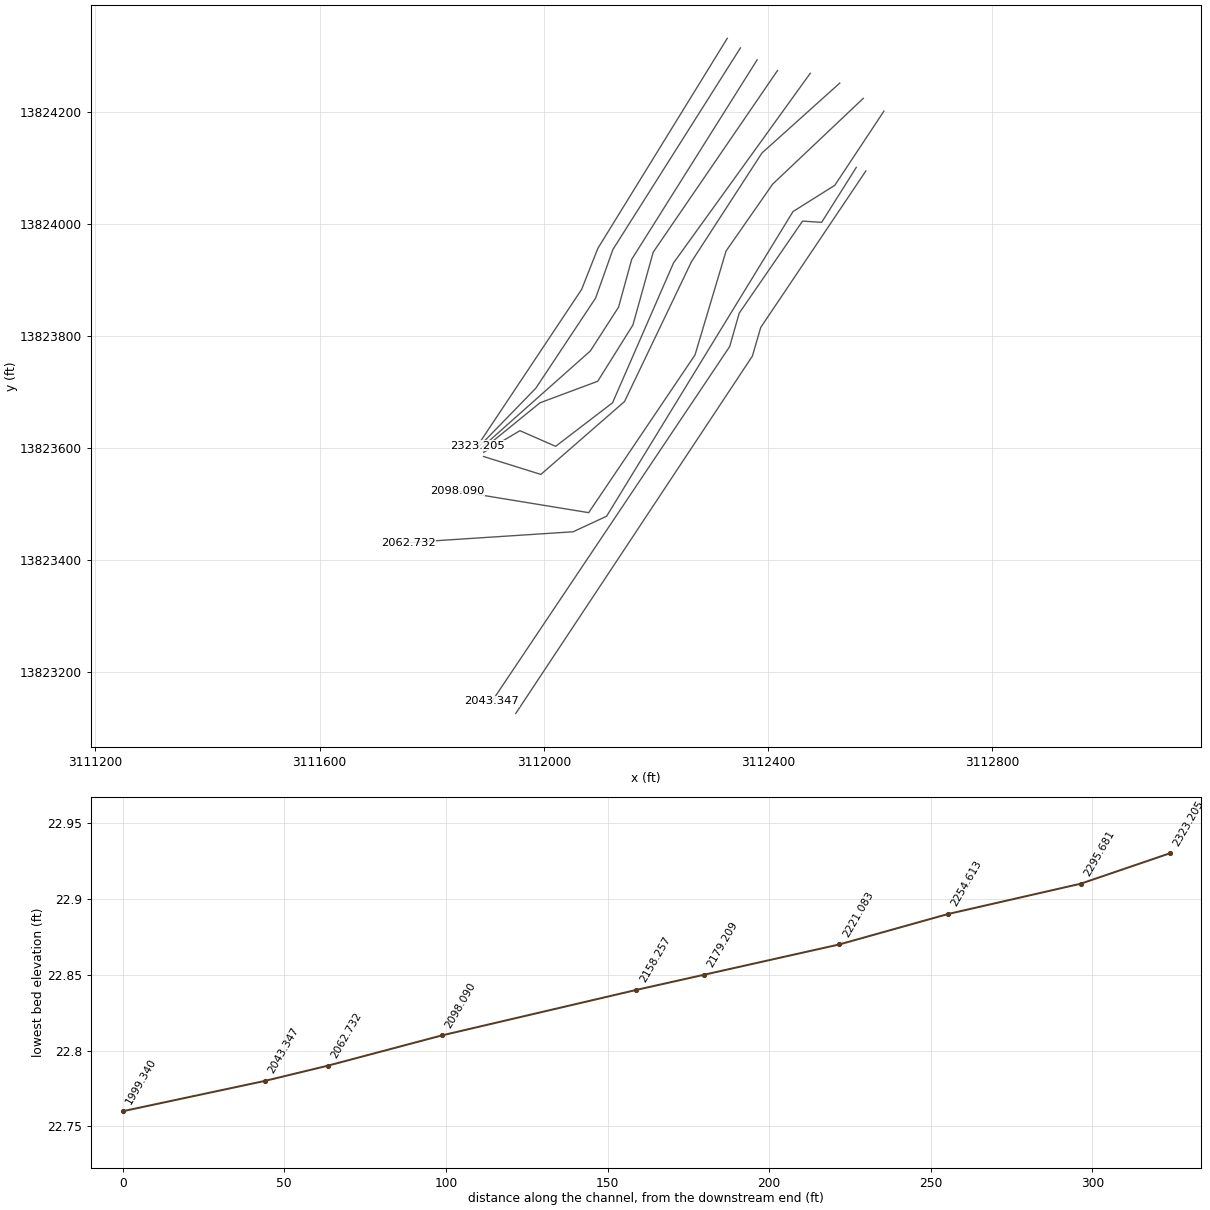
HEC-RAS study D109-00-00.prj: D109-00-00

--- D109-00-00.g01 (geometry) --- (continued)

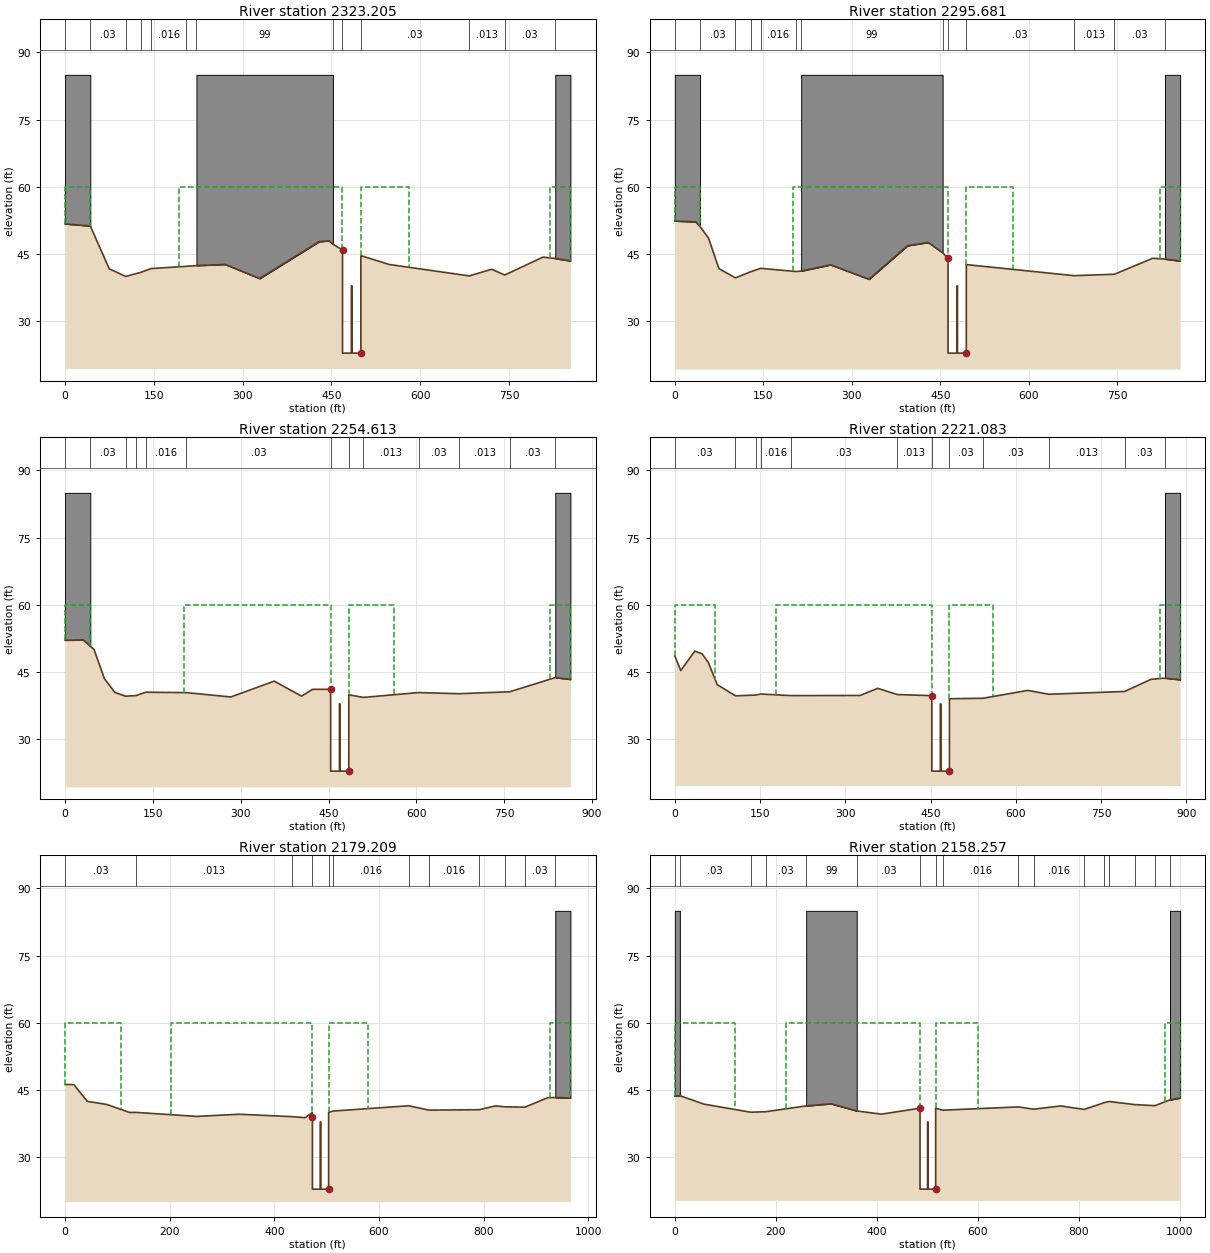
Type RM Length L Ch R = 1 ,2323.205,27.8,27.52,29.61
XS GIS Cut Line= 4
     3112327.038     13824330.93     3112096.103    13823956.137
     3112067.285    13823883.134     3111881.623    13823604.201
#Sta/Elev= 30
       0   51.75   42.69   51.28   74.69   41.73  102.45   40.04  128.07   40.95
  145.14   41.79  204.91   42.29  221.98   42.45  270.52   42.71  328.77   39.56
  429.09   47.78  445.87   47.98  452.51   47.24  468.67   45.93  468.77   45.93
  468.77   22.93  483.77   22.93  483.77   37.93  484.77   37.93  484.77   22.93
  499.77   22.93  499.77   44.67  499.87   44.67  547.72    42.7  683.03   40.15
  720.82   41.64  742.79   40.35  807.36   44.34  828.17   44.04  853.79   43.49
#Mann= 13 ,-1 , 0
       0      99       0   42.69     .03       0  102.45    .013       0
  128.07     .03       0  145.14    .016       0  204.91     .03       0
  221.98      99       0  452.51     .03       0  468.67    .011       0
  499.87     .03       0  683.03    .013       0  742.79     .03       0
  828.17      99       0
#XS Ineff= 4 ,-1
       0   42.69      60  193.07  468.67      60  499.87  580.57      60
  819.63  853.79      60
Permanent Ineff=
       F       F       F       F
#Block Obstruct= 3 ,-1
       0   42.69      85  221.98  452.51      85  828.17  853.79      85
#XS Lid=6
  468.77   45.93   37.93  473.95   45.85   37.93  478.41   45.69   37.93
  485.25   45.49   37.93  494.54   45.09   37.93  499.77   44.67   37.93
Bank Sta=468.77,499.77
XS Rating Curve= 0 ,0
Exp/Cntr=0.3,0.1

Type RM Length L Ch R = 1 ,2295.681,36.89,41.07,20.18
XS GIS Cut Line= 5
     3112350.481    13824313.881     3112122.999    13823954.216
      3112092.26    13823867.764     3111985.476    13823706.747
     3111883.859     13823602.27
#Sta/Elev= 30
       0   52.39   35.64   52.18   42.81   51.14    57.1   48.58   74.85   41.75
  102.75    39.7  128.44   41.06  145.57   41.83  205.51   41.11  214.07   41.21
  263.95   42.61  329.18   39.39  394.32   46.87  429.38   47.59  453.82   45.31
  462.88   44.04  462.98   44.04  462.98   22.91  477.98   22.91  477.98   37.91
  478.98   37.91  478.98   22.91  493.98   22.91  493.98   42.66  494.08   42.66
  676.46   40.19  744.96   40.51  809.75   44.07  830.59   43.89  856.27   43.45
#Mann= 13 ,-1 , 0
       0      99       0   42.81     .03       0  102.75    .013       0
  128.44     .03       0  145.57    .016       0  205.51     .03       0
  214.07      99       0  453.82     .03       0  462.88    .011       0
  494.08     .03       0  676.46    .013       0  744.96     .03       0
  830.59      99       0
#XS Ineff= 4 ,-1
       0   42.81      60  200.44  462.88      60  494.08   573.7      60
  822.02  856.27      60
Permanent Ineff=
       F       F       F       F
#Block Obstruct= 3 ,-1
       0   42.81      85  214.07  453.82      85  830.59  856.27      85
#XS Lid=5
  462.98   44.04   37.91  477.14   43.58   37.91  482.16   43.46   37.91
  493.06   42.67   37.91  493.98   42.66   37.91
Bank Sta=462.98,493.98
XS Rating Curve= 0 ,0
Exp/Cntr=0.3,0.1

Type RM Length L Ch R = 1 ,2254.613,29.7,33.53,19.46
XS GIS Cut Line= 5
     3112380.317    13824292.569     3112156.544    13823936.664
     3112133.101    13823851.417     3112082.844    13823773.327
      3111887.35    13823599.652
#Sta/Elev= 30
       0   52.11   30.96   52.17   43.16   50.76   49.55   50.05   67.27    43.5
   84.99   40.46  103.58   39.61  120.85   39.75  138.11    40.5  207.16   40.41
  283.21   39.44  357.32   42.97  403.92   39.62  422.86   41.15  453.54   41.15
  453.64   41.16  453.64   22.89  468.64   22.89  468.64   37.89  469.64   37.89
  469.64   22.89  484.64   22.89  484.64   39.93  484.74   39.93  509.28   39.34
  604.23   40.42  673.28   40.17   759.6    40.6  837.29   43.76  863.18   43.36
#Mann= 13 ,-1 , 0
       0      99       0   43.16     .03       0  103.58    .013       0
  120.85     .03       0  138.11    .016       0  207.16     .03       0
  453.54    .011       0  484.74     .03       0  509.28    .013       0
  604.23     .03       0  673.28    .013       0   759.6     .03       0
  837.29      99       0
#XS Ineff= 4 ,-1
       0   43.16      60  202.85  453.54      60  484.74  561.07      60
  828.65  863.18      60
Permanent Ineff=
       F       F       F       F
#Block Obstruct= 2 ,-1
       0   43.16      85  837.29  863.18      85
#XS Lid=5
  453.64   41.16   37.89     462   40.86   37.89  468.16   40.51   37.89
  471.67   40.39   37.89  484.64   39.93   37.89
Bank Sta=453.64,484.64
XS Rating Curve= 0 ,0
Exp/Cntr=0.3,0.1

Type RM Length L Ch R = 1 ,2221.083,47.09,41.87,77.7
XS GIS Cut Line= 6
     3112416.547    13824273.389     3112194.905    13823949.451
     3112158.675    13823819.449     3112095.935    13823719.217
     3111992.956    13823680.804     3111889.968    13823597.033
#Sta/Elev= 30
       0   48.61   10.49   45.33   35.26   49.67   48.29   49.03   59.33   47.04
   74.54   42.19   106.7   39.68  142.27   39.85  151.17   40.08  204.52   39.73
  326.14   39.76  356.95   41.36  391.25   39.97  452.13   39.72  452.23   39.72
  452.23   22.87  467.23   22.87  467.23   37.87  468.23   37.87  468.23   22.87
  483.23   22.87  483.23   39.03  483.33   39.03  542.42   39.14  621.29   40.89
  658.01   40.03  791.39   40.65  838.15   43.37  862.53   43.63  889.21   43.28
#Mann= 12 ,-1 , 0
       0     .03       0   106.7    .013       0  142.27     .03       0
  151.17    .016       0  204.52     .03       0  391.25    .013       0
  452.13    .011       0  483.33     .03       0  542.42     .03       0
  658.01    .013       0  791.39     .03       0  862.53      99       0
#XS Ineff= 4 ,-1
       0   71.14      60  177.84  452.13      60  483.33   560.2      60
  853.64  889.21      60
Permanent Ineff=
       F       F       F       F
#Block Obstruct= 1 ,-1
  862.53  889.21      85
#XS Lid=6
  452.23   39.72   37.87  454.41   39.58   37.87  463.13   39.37   37.87
  469.98   39.14   37.87  473.84   39.16   37.87  483.23   39.03   37.87
Bank Sta=452.23,483.23
XS Rating Curve= 0 ,0
Exp/Cntr=0.3,0.1

Type RM Length L Ch R = 1 ,2179.209,26.74,20.95,60.65
XS GIS Cut Line= 6
     3112475.066    13824268.611     3112231.135     13823930.27
     3112122.445    13823680.923     3112020.879    13823603.143
     3111957.169     13823631.07     3111892.587     13823592.67
#Sta/Elev= 30
       0   46.21   16.69    46.2   42.63   42.45   79.72   41.76  123.28   39.97
  135.21   39.99  251.09   39.09  332.98   39.57  434.61   39.03  458.86    38.8
  472.63   39.96  472.73   38.96  472.73   22.85  487.73   22.85  487.73   37.85
  488.73   37.85  488.73   22.85  503.73   22.85  503.73   39.98  503.83   39.98
  511.87   40.28  656.74   41.47  695.37   40.49  791.95   40.59  822.53   41.44
  840.24   41.23  878.88   41.16  922.77   43.28  936.82   43.31   965.8   43.19
#Mann= 12 ,-1 , 0
       0     .03       0  135.21    .013       0  434.61     .03       0
  472.63    .011       0  503.83     .03       0  511.87    .016       0
  656.74     .03       0  695.37    .016       0  791.95     .03       0
  840.24    .013       0  878.88     .03       0  936.82      99       0
#XS Ineff= 4 ,-1
       0  106.24      60  202.82  472.63      60  503.83  579.48      60
  927.17   965.8      60
Permanent Ineff=
       F       F       F       F
#Block Obstruct= 1 ,-1
  936.82   965.8      85
#XS Lid=6
  472.73   38.96   37.85  474.34   38.95   37.85  476.53   39.12   37.85
  485.16   39.36   37.85  501.21   39.95   37.85  503.73   39.98   37.85
Bank Sta=472.73,503.73
XS Rating Curve= 0 ,0
Exp/Cntr=0.3,0.1

Type RM Length L Ch R = 1 ,2158.257,59.04,60.17,59.38
XS GIS Cut Line= 6
     3112527.647    13824251.085     3112388.842    13824126.338
     3112263.103    13823932.401     3112143.757    13823683.054
     3111994.575    13823553.053     3111892.279     13823585.02
#Sta/Elev= 30
       0   43.63      10   43.71   57.91   41.82  150.06   40.02  180.07   40.13
  260.11   41.43  309.53    41.9  360.15    40.3  408.97   39.59  485.35   40.91
  485.45   40.91  485.45   22.84  500.45   22.84  500.45   37.84  501.45   37.84
  501.45   22.84  516.45   22.84  516.45   40.91  516.55   40.91  530.21   40.47
  680.27    41.2  710.29   40.69  763.83   41.42  810.33   40.64  850.34   42.16
  860.35   42.41  910.37   41.72  950.38   41.48   980.4   42.78  1000.4   43.18
#Mann= 17 ,-1 , 0
       0      99       0      10     .03       0  150.06    .013       0
  180.07     .03       0  260.11      99       0  360.15     .03       0
  485.35    .011       0  516.55     .03       0  530.21    .016       0
  680.27     .03       0  710.29    .016       0  810.33     .03       0
  850.34    .016       0  860.35     .03       0  910.37    .013       0
  950.38     .03       0   980.4      99       0
#XS Ineff= 4 ,-1
       0  120.05      60  220.09  485.35      60  516.55  600.24      60
  970.39  1000.4      60
Permanent Ineff=
       F       F       F       F
#Block Obstruct= 3 ,-1
       0      10      85  260.11  360.15      85   980.4  1000.4      85
#XS Lid=7
  485.45   40.91   37.84   494.6    41.1   37.84  499.31   41.02   37.84
  510.66   41.11   37.84  510.93    41.1   37.84  511.63   41.07   37.84
  516.45   40.91   37.84
Bank Sta=485.45,516.45
XS Rating Curve= 0 ,0
Exp/Cntr=0.3,0.1

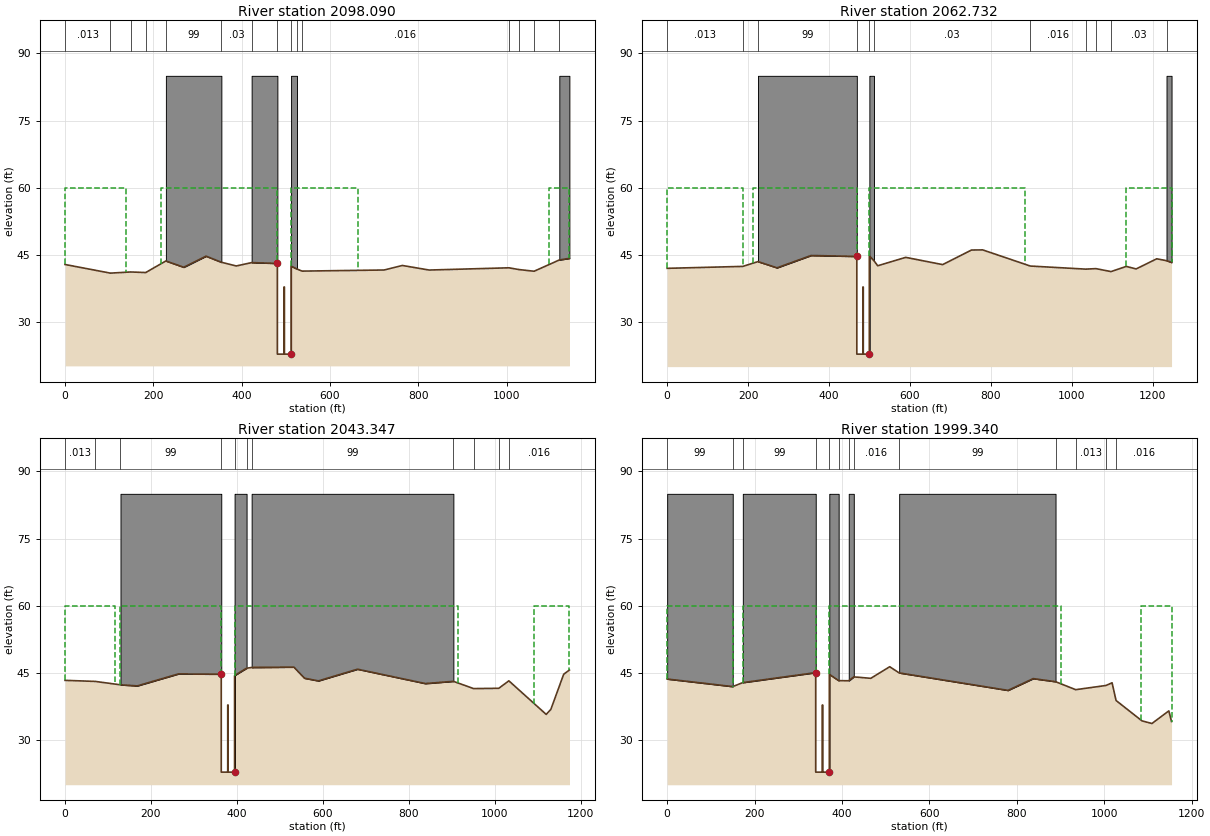
Type RM Length L Ch R = 1 ,2098.090,62.92,35.36,65.19
XS GIS Cut Line= 6
     3112569.711    13824223.918     3112408.022    13824070.927
     3112324.907    13823951.582     3112269.496     13823766.17
     3112079.822    13823484.855     3111845.393    13823523.216
#Sta/Elev= 30
       0   42.84  102.81   40.91  148.51   41.17  182.78   41.04  228.47   43.63
  268.78   42.22  319.53    44.7  354.13   43.34  387.83   42.51  422.67   43.26
  480.92   43.08  481.02   43.08  481.02   22.81  496.02   22.81  496.02   37.81
  497.02   37.81  497.02   22.81  512.02   22.81  512.02   42.46  512.12   42.46
  525.48   41.83  536.91   41.36  722.98   41.61  763.97   42.62  824.76    41.6
 1005.28    42.1 1028.12   41.71 1062.39   41.33 1119.51   43.85 1142.36   44.21
#Mann= 15 ,-1 , 0
       0    .013       0  102.81     .03       0  148.51    .013       0
  182.78     .03       0  228.47      99       0  354.13     .03       0
  422.67      99       0  480.92    .011       0  512.12      99       0
  525.48     .03       0  536.91    .016       0 1005.28     .03       0
 1028.12    .013       0 1062.39     .03       0 1119.51      99       0
#XS Ineff= 4 ,-1
       0  137.08      60  217.05  480.92      60  512.12  662.57      60
 1096.66 1142.36      60
Permanent Ineff=
       F       F       F       F
#Block Obstruct= 4 ,-1
  228.47  354.13      85  422.67  481.02      85  512.02  525.48      85
 1119.51 1142.36      85
#XS Lid=2
  481.02      85   37.81  512.02      85   37.81
Bank Sta=481.02,512.02
XS Rating Curve= 0 ,0
Exp/Cntr=0.3,0.1

Type RM Length L Ch R = 1 ,2062.732,45.84,19.39,167.25
XS GIS Cut Line= 6
     3112606.518    13824201.133     3112518.843    13824068.796
     3112444.252    13824021.911     3112111.789    13823478.462
     3112052.117    13823450.757     3111758.015    13823431.576
#Sta/Elev= 30
       0   41.97  186.96    42.4  224.35   43.47  271.32   42.08  355.71   44.84
  468.57   44.63  468.67   44.63  468.67   22.79  483.67   22.79  483.67   37.79
  484.67   37.79  484.67   22.79  499.67   22.79  499.67   44.73  499.77   44.73
  511.03   43.66  520.31   42.54  589.49   44.42  680.73    42.8  752.08   46.06
  779.66   46.09  897.42   42.48 1034.52   41.79 1059.46    41.9 1096.84   41.24
 1134.61    42.4 1158.84   41.83 1209.77    44.1 1233.95   43.68 1246.41   43.29
#Mann= 11 ,-1 , 0
       0    .013       0  186.96     .03       0  224.35      99       0
  468.57    .011       0  499.77      99       0  511.03     .03       0
  897.42    .016       0 1034.52     .03       0 1059.46    .013       0
 1096.84     .03       0 1233.95      99       0
#XS Ineff= 4 ,-1
       0  186.96      60  211.89  468.57      60  499.77  884.95      60
 1134.23 1246.41      60
Permanent Ineff=
       F       F       F       F
#Block Obstruct= 3 ,-1
  224.35  468.67      85  499.67  511.03      85 1233.95 1246.41      85
#XS Lid=2
  468.67      85   37.79  499.67      85   37.79
Bank Sta=468.67,499.67
XS Rating Curve= 0 ,0
Exp/Cntr=0.3,0.1

Type RM Length L Ch R = 1 ,2043.347,45.14,44.01,46.2
XS GIS Cut Line= 6
     3112557.204    13824100.764       3112495.4     13824002.73
     3112461.302    13824004.861     3112348.349    13823840.761
       3112331.3    13823781.088     3111907.197     13823148.13
#Sta/Elev= 30
       0    43.3   70.39   43.06  129.06    42.3  168.21   42.06  263.64   44.73
  363.36   44.68  363.46   44.68  363.46   22.78  378.46   22.78  378.46   37.78
  379.46   37.78  379.46   22.78  394.46   22.78  394.46   44.38  394.56   44.38
  422.36   46.01   434.1   46.18  532.27   46.26  557.07   43.77   589.5   43.18
  680.34   45.79  838.17   42.58  903.39   43.08  950.32   41.46 1008.98   41.52
 1032.45   43.19 1119.27   35.69 1130.09   36.81 1159.98   44.66 1173.24   45.61
#Mann= 11 ,-1 , 0
       0    .013       0   70.39     .03       0  129.06      99       0
  363.36    .011       0  394.56      99       0  422.36     .03       0
   434.1      99       0  903.39     .03       0  950.32    .013       0
 1008.98     .03       0 1032.45    .016       0
#XS Ineff= 4 ,-1
       0  117.32      60  129.06  363.36      60  394.56  915.12      60
 1091.11 1173.24      60
Permanent Ineff=
       F       F       F       F
#Block Obstruct= 3 ,-1
  129.06  363.46      85  394.46  422.36      85   434.1  903.39      85
#XS Lid=2
  363.46      85   37.78  394.46      85   37.78
Bank Sta=363.46,394.46
XS Rating Curve= 0 ,0
Exp/Cntr=0.3,0.1

Type RM Length L Ch R = 1 ,1999.340,42.04,39.38,26.72
XS GIS Cut Line= 4
     3112574.254     13824094.37      3112386.71    13823815.187
     3112371.792    13823764.039      3111949.82    13823126.818
#Sta/Elev= 30
       0   43.58     150   41.89  173.08   42.78  339.79   45.01  339.89   45.01
  339.89   22.76  354.89   22.76  354.89   37.76  355.89   37.76  355.89   22.76
  370.89   22.76  370.89   44.63  370.99   44.63  392.32   43.22   415.4   43.19
  426.93   44.06  465.83   43.74  509.12   46.33  530.78   44.95  779.71   41.04
  837.37   43.67  888.49   42.99  934.64    41.2 1003.87   42.14 1017.82   42.74
 1026.95   38.78 1086.24   34.22 1109.05   33.64  1147.7   36.46 1153.88   34.07
#Mann= 13 ,-1 , 0
       0      99       0     150     .03       0  173.08      99       0
  339.79    .011       0  370.99      99       0  392.32    .016       0
   415.4      99       0  426.93    .016       0  530.78      99       0
  888.49     .03       0  934.64    .013       0 1003.87     .03       0
 1026.95    .016       0
#XS Ineff= 4 ,-1
       0     150      60  173.08  339.79      60  370.99  900.02      60
 1084.65 1153.88      60
Permanent Ineff=
       F       F       F       F
#Block Obstruct= 5 ,-1
       0     150      85  173.08  339.89      85  370.89  392.32      85
   415.4  426.93      85  530.78  888.49      85
#XS Lid=2
  339.89      85   37.76  370.89      85   37.76
Bank Sta=339.89,370.89
XS Rating Curve= 0 ,0
Exp/Cntr=0.3,0.1