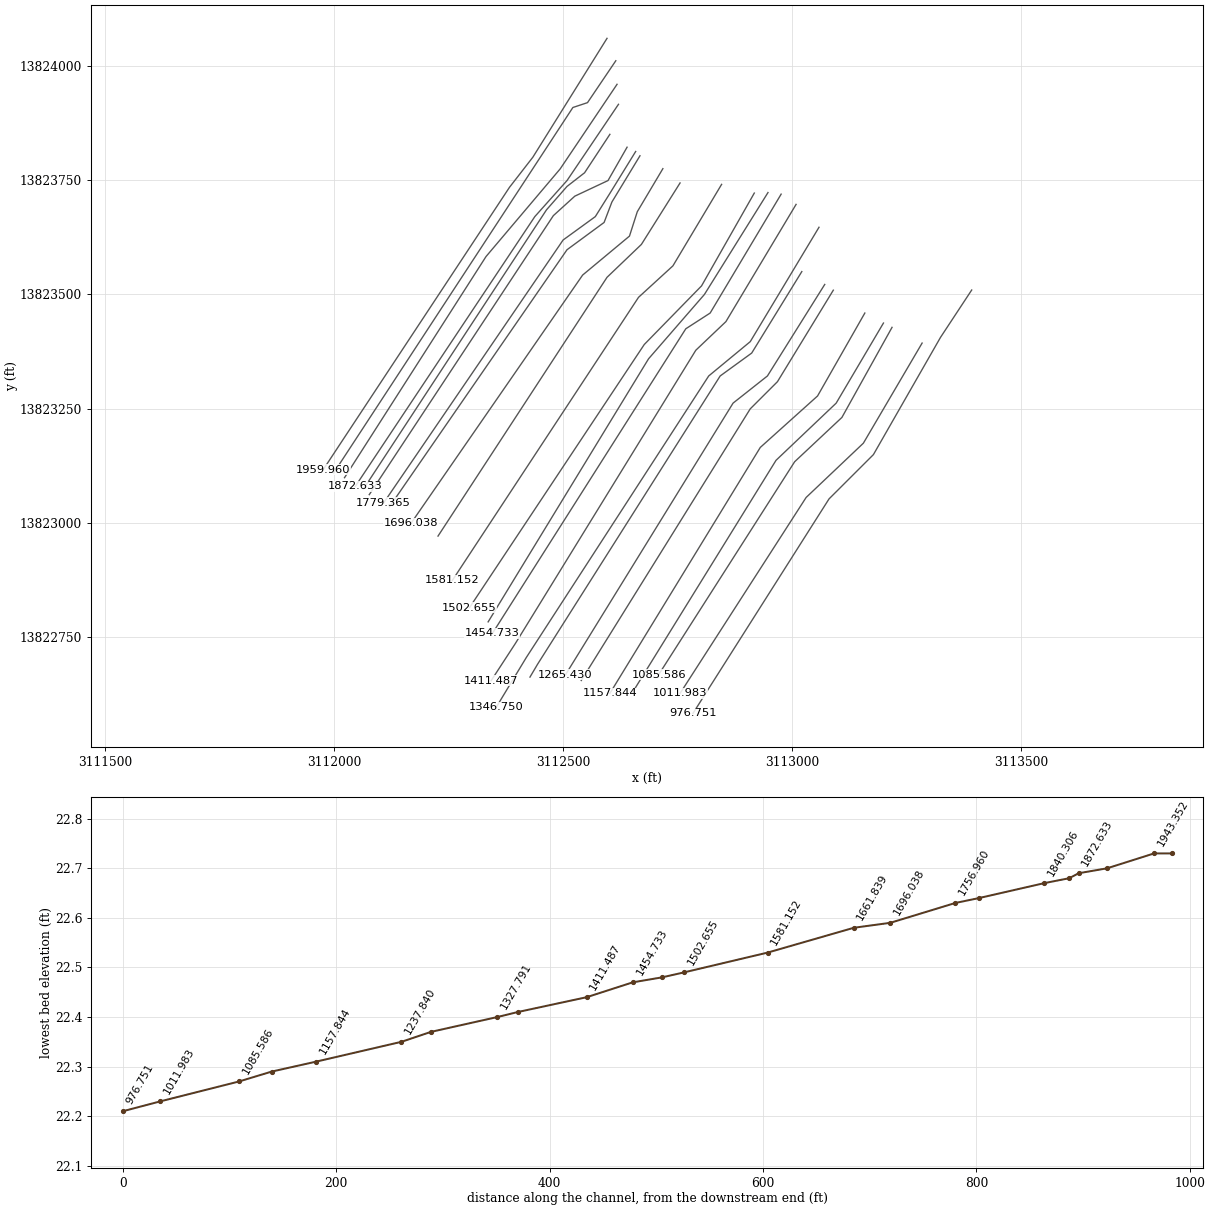
HEC-RAS study D109-00-00.prj: D109-00-00

--- D109-00-00.g01 (geometry) --- (continued)

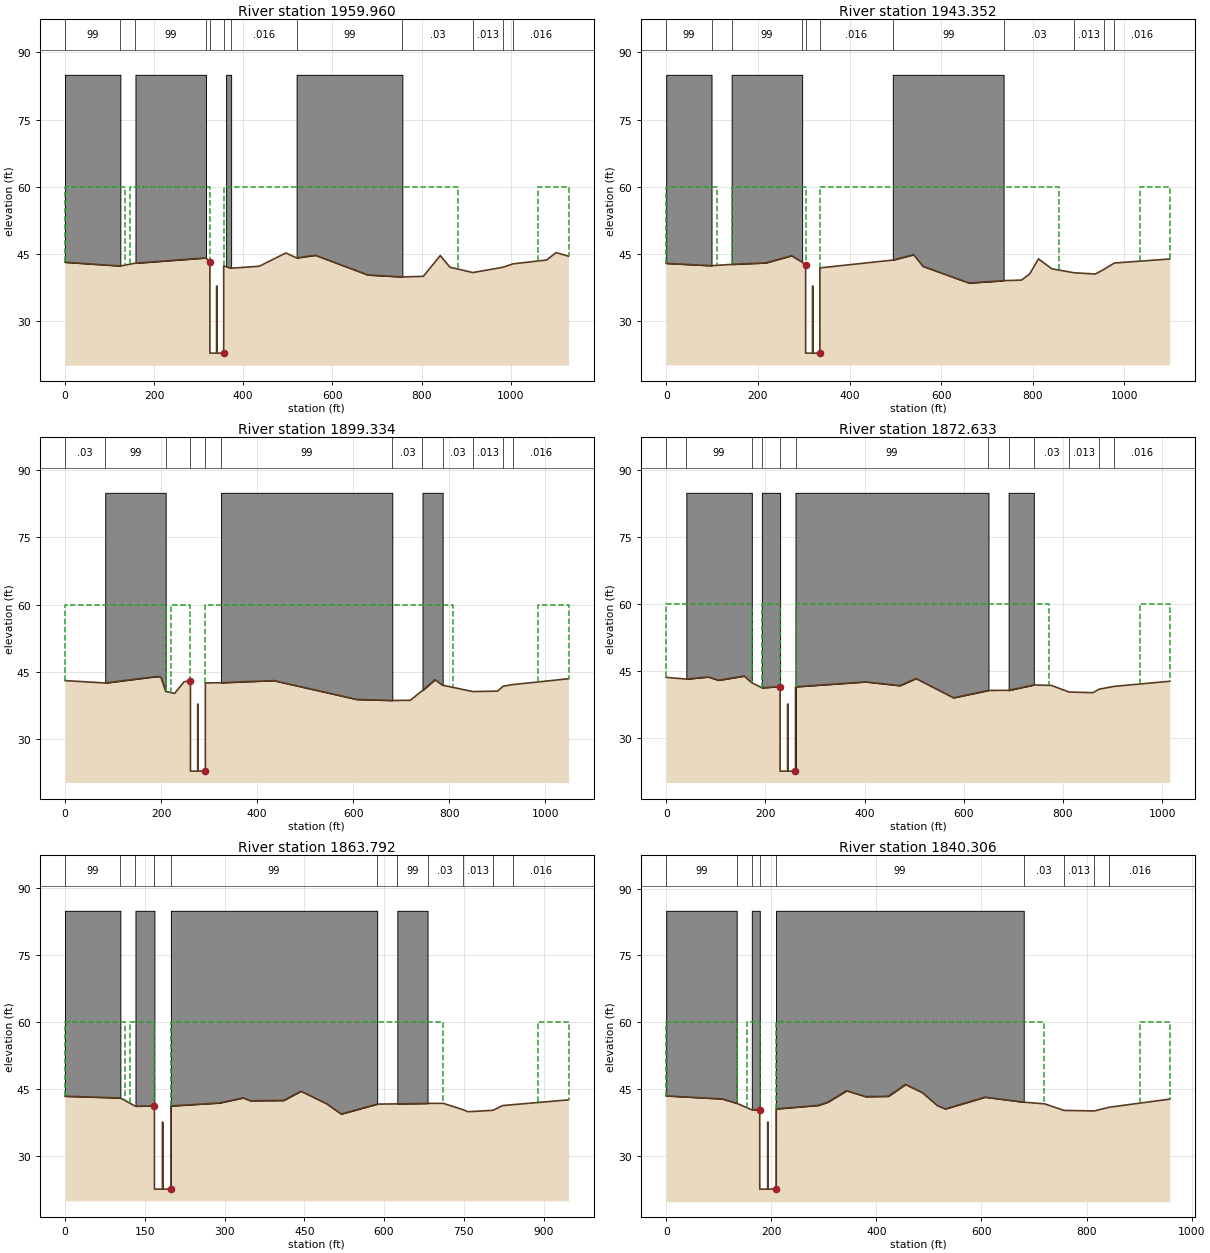
Type RM Length L Ch R = 1 ,1959.960,29.66,16.61,22.4
XS GIS Cut Line= 4
     3112595.565    13824060.272     3112433.596    13823800.269
     3112382.448    13823734.202     3111975.394    13823116.163
#Sta/Elev= 30
       0   43.07  124.29   42.23  158.19   42.86  316.38   44.04  325.08   43.09
  325.18   43.09  325.18   22.73  340.18   22.73  340.18   37.73  341.18   37.73
  341.18   22.73  356.18   22.73  356.18   42.26  356.28   42.26  372.87   41.73
  436.04   42.17  495.61   45.14  519.76   44.04   561.8   44.63   679.7   40.22
  757.05   39.78  804.17   39.91  842.13   44.56  863.79   41.95  915.24   40.76
  983.03   41.95 1005.63   42.71 1080.37   43.56 1102.03   45.21 1129.92   44.42
#Mann= 12 ,-1 , 0
       0      99       0  124.29    .016       0  158.19      99       0
  316.38    .016       0  325.08    .011       0  356.28      99       0
  372.87    .016       0  519.76      99       0  757.05     .03       0
  915.24    .013       0  983.03     .03       0 1005.63    .016       0
#XS Ineff= 4 ,-1
       0  135.59      60  146.89  325.08      60  356.28  881.34      60
 1062.13 1129.92      60
Permanent Ineff=
       F       F       F       F
#Block Obstruct= 4 ,-1
       0  124.29      85  158.19  316.38      85  361.58  372.87      85
  519.76  757.05      85
#XS Lid=5
  325.18   43.09   37.73  337.83   42.67   37.73  343.82   42.51   37.73
  345.57   42.49   37.73  356.18   42.26   37.73
Bank Sta=325.18,356.18
XS Rating Curve= 0 ,0
Exp/Cntr=0.3,0.1

Type RM Length L Ch R = 1 ,1943.352,160.21,44.02,23.56
XS GIS Cut Line= 4
     3112614.746    13824011.255     3112552.942    13823919.614
     3112520.974    13823908.958     3111998.837    13823109.769
#Sta/Elev= 30
       0   42.82    98.9   42.29  142.85   42.59  217.13   42.92  273.64   44.53
  296.69   43.09  304.17   42.34  304.27   42.34  304.27   22.73  319.27   22.73
  319.27   37.73  320.27   37.73  320.27   22.73  335.27   22.73  335.27    41.8
  335.37    41.8  494.49   43.55  539.88   44.76  560.32   42.15  660.62   38.42
  736.24   38.94  775.33   39.07  793.25   40.46  812.34   43.82  841.56    41.6
  890.08   40.71  936.59   40.43  956.01   41.52  977.99   42.89 1098.87   43.79
#Mann= 11 ,-1 , 0
       0      99       0    98.9    .016       0  142.85      99       0
  296.69    .016       0  304.17    .011       0  335.37    .016       0
  494.49      99       0  736.24     .03       0  890.08    .013       0
  956.01     .03       0  977.99    .016       0
#XS Ineff= 4 ,-1
       0  109.89      60  142.85  304.17      60  335.37  857.12      60
 1032.94 1098.87      60
Permanent Ineff=
       F       F       F       F
#Block Obstruct= 3 ,-1
       0    98.9      85  142.85  296.69      85  494.49  736.24      85
#XS Lid=6
  304.27   42.34   37.73  309.48   42.02   37.73  313.83   41.91   37.73
  320.48   41.98   37.73  327.39   41.98   37.73  335.27    41.8   37.73
Bank Sta=304.27,335.27
XS Rating Curve= 0 ,0
Exp/Cntr=0.3,0.1

Type RM Length L Ch R = 1 ,1899.334,26.67,26.7,33.44
XS GIS Cut Line= 4
     3112617.452    13823959.741     3112493.269    13823774.695
       3112331.3    13823582.889      3112022.28    13823099.113
#Sta/Elev= 30
       0   42.97   83.84   42.43  191.63   43.89  199.63   43.72  209.59   40.54
  228.19   40.09  247.82   42.71  261.06   42.94  261.16   42.94  261.16    22.7
  276.16    22.7  276.16    37.7  277.16    37.7  277.16    22.7  292.16    22.7
  292.16   42.44  292.26   42.44  324.86   42.49  434.16   42.97   607.1   38.75
  681.17   38.52   718.6   38.55  744.04   40.76  770.04   43.16  785.96   41.93
  848.84   40.51  900.38   40.61  911.71    41.7  932.67   42.08 1047.95   43.38
#Mann= 12 ,-1 , 0
       0     .03       0   83.84      99       0  209.59    .016       0
  261.06    .011       0  292.26    .016       0  324.86      99       0
  681.17     .03       0  744.04      99       0  785.96     .03       0
  848.84    .013       0  911.71     .03       0  932.67    .016       0
#XS Ineff= 4 ,-1
       0  209.59      60  220.07  261.06      60  292.26  806.92      60
  985.07 1047.95      60
Permanent Ineff=
       F       F       F       F
#Block Obstruct= 3 ,-1
   83.84  209.59      85  324.86  681.17      85  744.04  785.96      85
#XS Lid=6
  261.16   42.94    37.7  267.45   42.86    37.7  274.49   42.53    37.7
  282.83    42.6    37.7  287.08    42.5    37.7  292.16   42.44    37.7
Bank Sta=261.16,292.16
XS Rating Curve= 0 ,0
Exp/Cntr=0.3,0.1

Type RM Length L Ch R = 1 ,1872.633,16.62,8.84,16.8
XS GIS Cut Line= 4
      3112620.58    13823915.952     3112508.187    13823749.121
     3112437.859    13823670.267     3112045.723    13823079.933
#Sta/Elev= 30
       0   43.68   40.62    43.3    84.8   43.77  105.42   43.03  157.15   43.98
  172.64   42.48  192.95   41.35  229.65   41.62  229.75   41.62  229.75   22.69
  244.75   22.69  244.75   37.69  245.75   37.69  245.75   22.69  260.75   22.69
  260.75   41.57  260.85   41.57  402.43   42.67  471.24   41.83   503.7   43.42
  579.44   39.11  649.94   40.76  690.56   40.77  741.33   41.98  776.61   41.88
  812.42    40.4  860.77   40.26  873.35   41.04  903.82   41.67 1015.52   42.81
#Mann= 12 ,-1 , 0
       0     .03       0   40.62      99       0  172.64    .016       0
  192.95      99       0  229.65    .013       0  260.85      99       0
  649.94     .03       0  690.56      99       0  741.33     .03       0
  812.42    .013       0  873.35     .03       0  903.82    .016       0
#XS Ineff= 4 ,-1
       0  172.64      60  192.95  229.65      60  260.85   771.8      60
  954.59 1015.52      60
Permanent Ineff=
       F       F       F       F
#Block Obstruct= 4 ,-1
   40.62  172.64      85  192.95  229.75      85  260.75  649.94      85
  690.56  741.33      85
#XS Lid=2
  229.75      85   37.69  260.75      85   37.69
Bank Sta=229.75,260.75
XS Rating Curve= 0 ,0
Exp/Cntr=0.3,0.1

Type RM Length L Ch R = 1 ,1863.792,32.71,23.49,17.87
XS GIS Cut Line= 5
     3112601.814    13823850.269     3112546.548     13823766.17
     3112508.187    13823736.334     3112463.433    13823685.185
     3112063.838    13823074.583
#Sta/Elev= 30
       0   43.49  104.16   43.09  132.57   41.25   168.1   41.32   168.2   41.32
   168.2   22.68   183.2   22.68   183.2   37.68   184.2   37.68   184.2   22.68
   199.2   22.68   199.2   41.31   199.3   41.31  290.84   41.98  335.25   43.12
  348.14   42.48   411.1   42.54   443.6   44.61  491.55   41.84  519.45    39.5
   587.1   41.72  624.97   41.77  681.79   41.88  711.54   41.88  748.07   40.49
  757.83   40.01  804.89   40.33  822.85   41.39  842.77    41.6  946.93   42.67
#Mann= 11 ,-1 , 0
       0      99       0  104.16    .016       0  132.57      99       0
   168.1    .011       0   199.3      99       0   587.1     .03       0
  624.97      99       0  681.79     .03       0  748.07    .013       0
  804.89     .03       0  842.77    .016       0
#XS Ineff= 4 ,-1
       0  113.63      60   123.1   168.1      60   199.3   710.2      60
  890.11  946.93      60
Permanent Ineff=
       F       F       F       F
#Block Obstruct= 4 ,-1
       0  104.16      85  132.57   168.2      85   199.2   587.1      85
  624.97  681.79      85
#XS Lid=2
   168.2      85   37.68   199.2      85   37.68
Bank Sta=168.2,199.2
XS Rating Curve= 0 ,0
Exp/Cntr=0.3,0.1

Type RM Length L Ch R = 1 ,1840.306,50.05,60.94,39.04
XS GIS Cut Line= 5
     3112639.347    13823822.119     3112597.696    13823749.121
     3112525.237    13823715.022     3112478.351    13823672.398
     3112076.349    13823062.072
#Sta/Elev= 30
       0   43.56  106.33   42.87  134.16    41.9  162.91   40.44  177.98   40.48
  178.08   40.48  178.08   22.67  193.08   22.67  193.08   37.67  194.08   37.67
  194.08   22.67  209.08   22.67  209.08   40.64  209.18   40.64  289.49   41.43
  307.45   42.15  343.38    44.7   379.8   43.38  422.81   43.47   455.3   46.11
  487.07   44.32  516.14   41.38   531.1   40.64   606.9   43.27   680.4   42.15
  720.57   41.76  757.07    40.3  814.57   40.18  843.32   41.01  958.32   42.83
#Mann= 9 ,-1 , 0
       0      99       0  134.16    .016       0  162.91      99       0
  177.98    .011       0  209.18      99       0   680.4     .03       0
  757.07    .013       0  814.57     .03       0  843.32    .016       0
#XS Ineff= 4 ,-1
       0  134.16      60  153.33  177.98      60  209.18  718.74      60
  900.82  958.32      60
Permanent Ineff=
       F       F       F       F
#Block Obstruct= 3 ,-1
       0  134.16      85  162.91  178.08      85  209.08   680.4      85
#XS Lid=2
  178.08      85   37.67  209.08      85   37.67
Bank Sta=178.08,209.08
XS Rating Curve= 0 ,0
Exp/Cntr=0.3,0.1

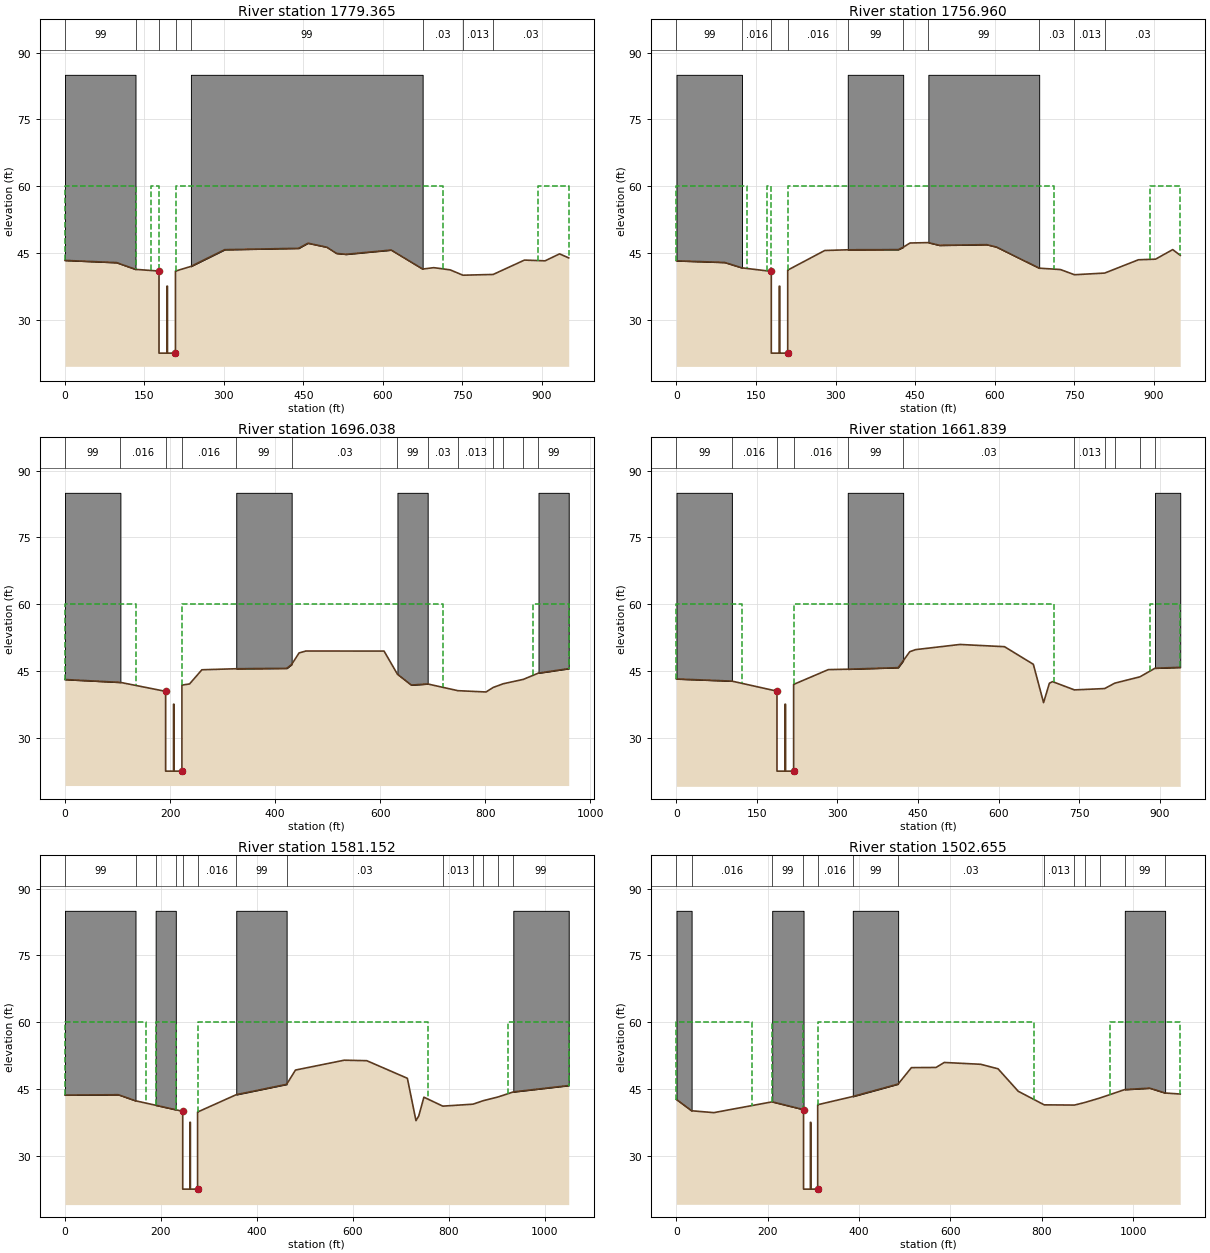
Type RM Length L Ch R = 1 ,1779.365,17.02,22.41,16.36
XS GIS Cut Line= 5
     3112658.113    13823812.736     3112601.959    13823721.415
     3112569.991    13823670.267     3112499.663    13823619.119
     3112107.527    13823043.703
#Sta/Elev= 30
       0   43.42   97.39   42.92  133.11   41.41  177.42   41.03  177.52   41.03
  177.52   22.64  192.52   22.64  192.52   37.64  193.52   37.64  193.52   22.64
  208.52   22.64  208.52   41.02  208.62   41.02   237.7   42.07  301.49   45.82
  441.09   46.13  458.57   47.28  494.36   46.37  512.55   44.98  530.35   44.78
   615.7   45.74  675.08   41.48  696.07   41.79  727.02    41.3  751.14    40.1
  808.19   40.27  867.27   43.49  906.14   43.32  933.56   44.88  950.81   43.98
#Mann= 8 ,-1 , 0
       0      99       0  133.11    .016       0  177.42    .011       0
  208.62    .016       0   237.7      99       0  675.08     .03       0
  751.14    .013       0  808.19     .03       0
#XS Ineff= 4 ,-1
       0  133.11      60  161.64  177.42      60  208.62  713.11      60
  893.76  950.81      60
Permanent Ineff=
       F       F       F       F
#Block Obstruct= 2 ,-1
       0  133.11      85   237.7  675.08      85
#XS Lid=5
  177.52   41.03   37.64   180.4   41.06   37.64  190.16   41.21   37.64
  198.95    41.1   37.64  208.52   41.02   37.64
Bank Sta=177.52,208.52
XS Rating Curve= 0 ,0
Exp/Cntr=0.3,0.1

Type RM Length L Ch R = 1 ,1756.960,61.78,60.92,59.3
XS GIS Cut Line= 5
     3112667.497    13823803.353     3112606.221    13823702.235
     3112589.172     13823657.48     3112508.187    13823597.807
     3112120.314    13823035.178
#Sta/Elev= 30
       0   43.32   90.89   42.95  123.51   41.74   178.7   40.95   178.8   40.95
   178.8   22.63   193.8   22.63   193.8   37.63   194.8   37.63   194.8   22.63
   209.8   22.63   209.8   41.24   209.9   41.24  279.61   45.63  323.03   45.79
  418.28   45.83  427.54   46.36  440.47   47.31  475.05    47.4  495.77   46.79
  585.18   46.94  603.39   46.41  684.07   41.67  724.22   41.36  750.57    40.2
  807.58   40.57  871.22   43.55  903.58   43.69  935.93   45.83  950.09   44.55
#Mann= 10 ,-1 , 0
       0      99       0  123.51    .016       0   178.7    .011       0
   209.9    .016       0  323.03      99       0  427.54     .03       0
  475.05      99       0  684.07     .03       0  750.57    .013       0
  807.58     .03       0
#XS Ineff= 4 ,-1
       0  133.01      60  171.02   178.7      60   209.9  712.57      60
  893.09  950.09      60
Permanent Ineff=
       F       F       F       F
#Block Obstruct= 3 ,-1
       0  123.51      85  323.03  427.54      85  475.05  684.07      85
#XS Lid=6
   178.8   40.95   37.63  202.66   41.04   37.63  202.87   41.04   37.63
  202.89   41.04   37.63  202.98   41.04   37.63   209.8   41.24   37.63
Bank Sta=178.8,209.8
XS Rating Curve= 0 ,0
Exp/Cntr=0.3,0.1

Type RM Length L Ch R = 1 ,1696.038,38.87,34.2,68.18
XS GIS Cut Line= 5
     3112717.541    13823775.203     3112661.632    13823680.923
     3112644.582    13823627.644     3112542.286    13823542.397
       3112167.2    13822998.948
#Sta/Elev= 30
       0   43.13  105.49   42.49  191.56   40.48  191.66   40.48  191.66   22.59
  206.66   22.59  206.66   37.59  207.66   37.59  207.66   22.59  222.66   22.59
  222.66   41.88  222.76   41.88  237.16   42.14  260.67   45.32  326.07   45.55
  422.37   45.65  431.57   46.52  445.72    49.1  458.83   49.53  607.47   49.51
  632.96   44.32  659.31   41.89   690.5   42.14  748.05   40.63  801.56   40.34
  815.18   41.35  834.36   42.18  872.72   43.17  901.49   44.58  959.03   45.57
#Mann= 13 ,-1 , 0
       0      99       0  105.49    .016       0  191.56    .011       0
  222.76    .016       0  326.07      99       0  431.57     .03       0
  632.96      99       0   690.5     .03       0  748.05    .013       0
  815.18     .03       0  834.36    .016       0  872.72     .03       0
  901.49      99       0
#XS Ineff= 3 ,-1
       0  134.26      60  222.76  719.28      60   891.9  959.03      60
Permanent Ineff=
       F       F       F
#Block Obstruct= 4 ,-1
       0  105.49      85  326.07  431.57      85  632.96   690.5      85
  901.49  959.03      85
#XS Lid=6
  191.66   40.48   37.59  198.11   40.54   37.59  199.26   40.55   37.59
  199.95   40.58   37.59  220.25   41.81   37.59  222.66   41.88   37.59
Bank Sta=191.66,222.66
XS Rating Curve= 0 ,0
Exp/Cntr=0.3,0.1

Type RM Length L Ch R = 1 ,1661.839,82.55,80.69,81.53
XS GIS Cut Line= 4
     3112755.074    13823743.925     3112670.624    13823609.431
     3112595.558    13823537.492     3112226.482    13822971.367
#Sta/Elev= 30
       0   43.25  103.24   42.77  187.14   40.52  187.24   40.52  187.24   22.58
  202.24   22.58  202.24   37.58  203.24   37.58  203.24   22.58  218.24   22.58
  218.24   42.03  218.34   42.03  282.91   45.35  319.12   45.44  412.98   45.79
  422.36   47.31  434.66   49.37   445.5   49.83  528.24   50.99   611.2   50.49
  664.92   46.54  683.97   37.94  694.81   42.29  700.73   42.65  741.48    40.8
   797.8    41.1  816.57   42.31   863.5   43.73  891.66   45.66  938.59   45.86
#Mann= 11 ,-1 , 0
       0      99       0  103.24    .016       0  187.14    .011       0
  218.34    .016       0  319.12      99       0  422.36     .03       0
  741.48    .013       0   797.8     .03       0  816.57    .016       0
   863.5     .03       0  891.66      99       0
#XS Ineff= 3 ,-1
       0  122.02      60  218.34  703.94      60  882.27  938.59      60
Permanent Ineff=
       F       F       F
#Block Obstruct= 3 ,-1
       0  103.24      85  319.12  422.36      85  891.66  938.59      85
#XS Lid=5
  187.24   40.52   37.58  187.97   40.52   37.58  197.61   40.75   37.58
  207.67   41.37   37.58  218.24   42.03   37.58
Bank Sta=187.24,218.24
XS Rating Curve= 0 ,0
Exp/Cntr=0.3,0.1

Type RM Length L Ch R = 1 ,1581.152,75.24,78.5,65.08
XS GIS Cut Line= 4
     3112845.779    13823740.797     3112739.435    13823562.515
     3112664.369    13823493.704     3112257.759    13822874.406
#Sta/Elev= 30
       0   43.64  111.29   43.72  147.04   42.36  189.05   41.36  231.06   40.35
  245.39   39.99  245.49   39.99  245.49   22.53  260.49   22.53  260.49   37.53
  261.49   37.53  261.49   22.53  276.49   22.53  276.49   39.84  276.59   39.84
  357.09   43.73  462.12   46.05  480.59   49.26  582.35   51.47  629.24   51.36
  713.86   47.41  731.81   37.91  737.57   38.96   748.4   43.17  787.71   41.16
  850.72    41.6  871.73   42.37  903.24   43.23  934.74   44.35 1050.27   45.78
#Mann= 13 ,-1 , 0
       0      99       0  147.04    .016       0  189.05      99       0
  231.06    .016       0  245.39    .011       0  276.59    .016       0
  357.09      99       0  462.12     .03       0  787.71    .013       0
  850.72     .03       0  871.73    .016       0  903.24     .03       0
  934.74      99       0
#XS Ineff= 4 ,-1
       0  168.04      60  189.05  231.06      60  276.59   756.2      60
  924.24 1050.27      60
Permanent Ineff=
       F       F       F       F
#Block Obstruct= 4 ,-1
       0  147.04      85  189.05  231.06      85  357.09  462.12      85
  934.74 1050.27      85
#XS Lid=5
  245.49   39.99   37.53   248.1   39.93   37.53  254.79   39.85   37.53
  266.79   39.74   37.53  276.49   39.84   37.53
Bank Sta=245.49,276.49
XS Rating Curve= 0 ,0
Exp/Cntr=0.3,0.1

Type RM Length L Ch R = 1 ,1502.655,17.15,20.6,41.68
XS GIS Cut Line= 4
     3112917.168    13823721.765     3112801.991    13823518.726
      3112676.88    13823390.487     3112295.293    13822814.979
#Sta/Elev= 30
       0   42.61   33.09   40.09   81.79   39.67  209.59    42.1  278.13   40.35
  278.23   40.35  278.23   22.49  293.23   22.49  293.23   37.49  294.23   37.49
  294.23   22.49  309.23   22.49  309.23   41.45  309.33   41.45  386.09   43.29
  485.37   46.09  514.42   49.78  568.41   49.82  586.41   50.94  666.19   50.53
  704.12   49.52  748.39   44.47  805.27   41.42  871.46   41.37  893.52   41.93
  926.61   42.94  981.77   44.85 1036.35   45.17 1070.02   44.08 1103.11   43.85
#Mann= 13 ,-1 , 0
       0      99       0   33.09    .016       0  209.59      99       0
  278.13    .011       0  309.33    .016       0  386.09      99       0
  485.37     .03       0  805.27    .013       0  871.46     .03       0
  893.52    .016       0  926.61     .03       0  981.77      99       0
 1070.02     .03       0
#XS Ineff= 4 ,-1
       0  165.47      60  209.59  278.13      60  309.33  783.21      60
  948.68 1103.11      60
Permanent Ineff=
       F       F       F       F
#Block Obstruct= 4 ,-1
       0   33.09      85  209.59  278.23      85  386.09  485.37      85
  981.77 1070.02      85
#XS Lid=8
  278.23      85   37.49  279.68      85   37.49  286.81      85   37.49
  286.81   40.28   37.49  290.37   40.25   37.49  300.64    41.2   37.49
  300.98   41.22   37.49  309.23   41.45   37.49
Bank Sta=278.23,309.23
XS Rating Curve= 0 ,0
Exp/Cntr=0.3,0.1

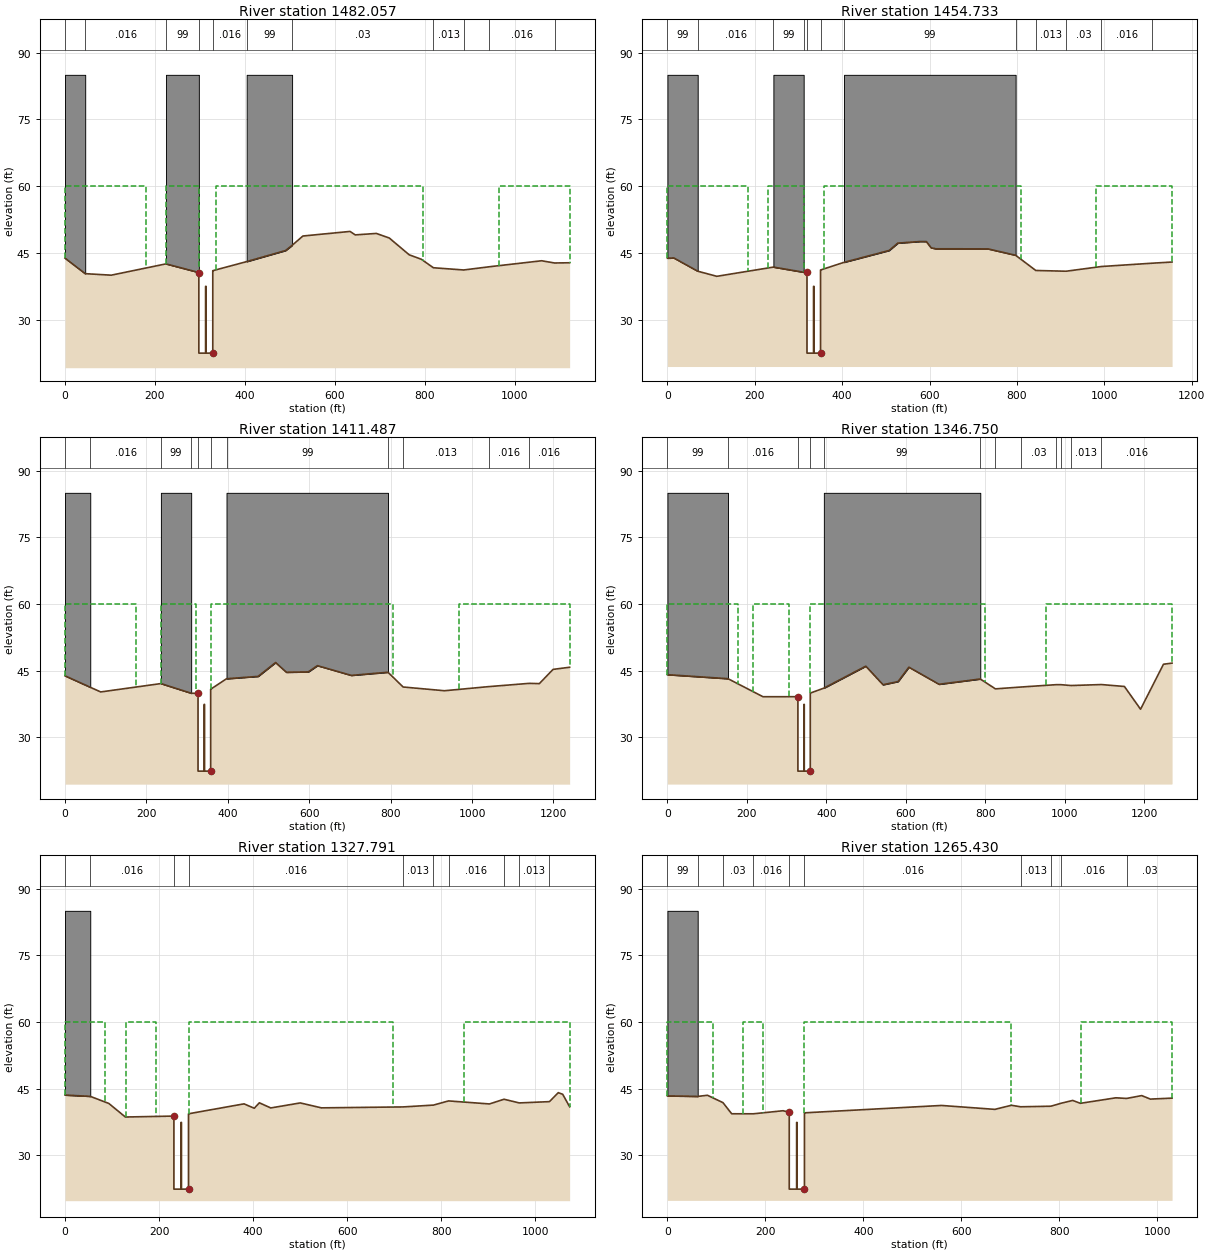
Type RM Length L Ch R = 1 ,1482.057,30.46,27.32,25.77
XS GIS Cut Line= 4
     3112947.076    13823722.915     3112808.246    13823499.959
     3112686.263     13823359.21     3112335.954    13822783.701
#Sta/Elev= 30
       0   43.81   44.91   40.33  102.83   39.99  224.53   42.53  297.62   40.59
  297.72   40.59  297.72   22.48  312.72   22.48  312.72   37.48  313.72   37.48
  313.72   22.48  328.72   22.48  328.72      41  328.82      41  404.15   43.04
  490.62   45.53  505.19   46.69   529.2   48.79  634.09   49.82  645.59   49.04
  692.56   49.37  721.41   48.34  765.66   44.57   792.6   43.57  819.53   41.66
  886.89   41.16  943.02   41.87 1060.39   43.23 1088.96   42.73 1122.64   42.78
#Mann= 11 ,-1 , 0
       0      99       0   44.91    .016       0  224.53      99       0
  297.62    .011       0  328.82    .016       0  404.15      99       0
  505.19     .03       0  819.53    .013       0  886.89     .03       0
  943.02    .016       0 1088.96     .03       0
#XS Ineff= 4 ,-1
       0  179.62      60  224.53  297.72      60  336.79  797.07      60
  965.47 1122.64      60
Permanent Ineff=
       F       F       F       F
#Block Obstruct= 3 ,-1
       0   44.91      85  224.53  297.72      85  404.15  505.19      85
#XS Lid=9
  297.72      85   37.48  301.47      85   37.48  303.11      85   37.48
  303.11   40.59   37.48  321.03   40.82   37.48  321.32   40.82   37.48
  321.43   40.82   37.48  321.69   40.83   37.48  328.72      41   37.48
Bank Sta=297.72,328.72
XS Rating Curve= 0 ,0
Exp/Cntr=0.3,0.1

Type RM Length L Ch R = 1 ,1454.733,39.3,43.25,50.64
XS GIS Cut Line= 4
     3112975.833    13823719.464     3112820.757    13823459.298
     3112767.585    13823424.893     3112345.337    13822758.679
#Sta/Elev= 30
       0    43.8   14.66   43.85    69.3   40.88  113.13   39.73  242.54    41.8
  311.84   40.64  319.34    40.7  319.44    40.7  319.44   22.47  334.44   22.47
  334.44   37.47  335.44   37.47  335.44   22.47  350.44   22.47  350.44   41.15
  350.54   41.15  404.24   42.87  507.42   45.53  527.29   47.19  578.46   47.55
  592.51   47.54  603.38   46.14  613.97   45.92  733.81   45.89  796.93   44.46
  843.12   41.04  912.42   40.87  993.27   41.93 1108.77   42.67 1154.96   42.94
#Mann= 12 ,-1 , 0
       0      99       0    69.3    .016       0  242.54      99       0
  311.84    .016       0  319.34    .011       0  350.54    .016       0
  404.24      99       0  796.93     .03       0  843.12    .013       0
  912.42     .03       0  993.27    .016       0 1108.77     .03       0
#XS Ineff= 4 ,-1
       0  184.79      60  230.99  311.84      60  358.04  808.48      60
  981.72 1154.96      60
Permanent Ineff=
       F       F       F       F
#Block Obstruct= 3 ,-1
       0    69.3      85  242.54  311.84      85  404.24  796.93      85
#XS Lid=5
  319.44    40.7   37.47  328.11   40.77   37.47  333.27    40.8   37.47
  337.26   40.87   37.47  350.44   41.15   37.47
Bank Sta=319.44,350.44
XS Rating Curve= 0 ,0
Exp/Cntr=0.3,0.1

Type RM Length L Ch R = 1 ,1411.487,68.34,64.74,42.59
XS GIS Cut Line= 5
     3113008.423    13823697.008     3112855.163    13823440.532
      3112789.48    13823377.976      3112395.36    13822736.386
     3112342.357    13822654.883
#Sta/Elev= 30
       0   43.86   61.98   41.29   87.68   40.24  235.54   42.12  309.92   39.95
  326.71   39.92  326.81   39.92  326.81   22.44  341.81   22.44  341.81   37.44
  342.81   37.44  342.81   22.44  357.81   22.44  357.81   40.86  357.91   40.86
   396.7    43.2   474.4   43.74  517.25   46.85   543.8   44.66  597.63   44.75
  620.14   46.15  703.25   43.96  793.39   44.67  830.59   41.35  932.11   40.51
 1041.33   41.44  1140.5   42.17 1165.26   42.11 1198.93   45.31 1239.68   45.79
#Mann= 11 ,-1 , 0
       0      99       0   61.98    .016       0  235.54      99       0
  309.92    .016       0  326.71    .011       0  357.91    .016       0
   396.7      99       0  793.39     .03       0  830.59    .013       0
 1041.33    .016       0  1140.5    .016       0
#XS Ineff= 4 ,-1
       0  173.56      60  235.54  322.32      60  359.51  805.79      60
  966.95 1239.68      60
Permanent Ineff=
       F       F       F       F
#Block Obstruct= 3 ,-1
       0   61.98      85  235.54  309.92      85   396.7  793.39      85
#XS Lid=5
  326.81   39.92   37.44  334.12   40.04   37.44  342.15   40.16   37.44
  354.83   40.61   37.44  357.81   40.86   37.44
Bank Sta=326.81,357.81
XS Rating Curve= 0 ,0
Exp/Cntr=0.3,0.1

Type RM Length L Ch R = 1 ,1346.750,16.69,18.96,25.94
XS GIS Cut Line= 5
     3113058.467    13823646.964     3112908.335    13823396.743
     3112817.629    13823321.677     3112419.276    13822705.761
      3112353.66    13822596.954
#Sta/Elev= 30
       0    44.1  152.41    43.2  240.64   39.14   328.4   39.15   328.5   39.15
   328.5   22.41   343.5   22.41   343.5   37.41   344.5   37.41   344.5   22.41
   359.5   22.41   359.5   39.96   359.6   39.96  393.74   41.07   499.3   46.02
  542.69   41.83   580.6   42.56  607.78   45.79  683.71   41.94  787.47   43.13
  825.58   40.91  889.08   41.32  977.99   41.85  990.69   41.85 1016.09   41.66
  1092.3   41.88 1150.22   41.45 1190.89   36.33 1248.57   46.45 1270.12    46.7
#Mann= 12 ,-1 , 0
       0      99       0  152.41    .016       0   328.4    .011       0
   359.6    .016       0  393.74      99       0  787.47     .03       0
  825.58    .013       0  889.08     .03       0  977.99    .016       0
  990.69     .03       0 1016.09    .013       0  1092.3    .016       0
#XS Ineff= 4 ,-1
       0  177.82      60  215.92  304.83      60   359.6  800.17      60
  952.59 1270.12      60
Permanent Ineff=
       F       F       F       F
#Block Obstruct= 2 ,-1
       0  152.41      85  393.74  787.47      85
#XS Lid=5
   328.5   39.15   37.41  331.62   39.18   37.41  335.63   39.29   37.41
  342.69   39.32   37.41   359.5   39.96   37.41
Bank Sta=328.5,359.5
XS Rating Curve= 0 ,0
Exp/Cntr=0.3,0.1

Type RM Length L Ch R = 1 ,1327.791,56.58,62.36,60.9
XS GIS Cut Line= 5
     3113020.934    13823550.004     3112911.462    13823371.721
     3112842.652    13823321.677     3112443.956    13822691.182
     3112427.284    13822662.908
#Sta/Elev= 30
       0   43.56   53.65   43.27   93.15   41.67  128.36   38.62   231.5   38.83
   231.6   38.83   231.6    22.4   246.6    22.4   246.6    37.4   247.6    37.4
   247.6    22.4   262.6    22.4   262.6   39.35   262.7   39.35  380.65   41.58
  402.39   40.59  413.26   41.82  437.52   40.66  500.24   41.79  545.24   40.68
  718.97   40.89  783.36    41.3  815.55   42.24  902.52   41.56  933.59   42.62
  965.79   41.79 1030.17   42.08  1048.9    44.1 1058.34   43.73 1073.09   40.92
#Mann= 10 ,-1 , 0
       0      99       0   53.65    .016       0   231.5    .011       0
   262.7    .016       0  718.97    .013       0  783.36     .03       0
  815.55    .016       0  933.59     .03       0  965.79    .013       0
 1030.17    .016       0
#XS Ineff= 4 ,-1
       0   85.85      60  128.77  193.16      60   262.7  697.51      60
  847.74 1073.09      60
Permanent Ineff=
       F       F       F       F
#Block Obstruct= 1 ,-1
       0   53.65      85
#XS Lid=4
   231.6   38.83    37.4  242.97   38.98    37.4  254.82   39.32    37.4
   262.6   39.35    37.4
Bank Sta=231.6,262.6
XS Rating Curve= 0 ,0
Exp/Cntr=0.3,0.1

Type RM Length L Ch R = 1 ,1265.430,23.74,27.59,36.79
XS GIS Cut Line= 4
     3113070.978    13823521.854     3112945.868    13823321.677
     3112870.801    13823262.249     3112504.853    13822667.974
#Sta/Elev= 30
       0   43.35   61.78   43.24   81.74   43.49  113.27   41.84  131.17   39.33
  175.05   39.32  236.06   40.01  248.52   39.69  248.62   39.69  248.62   22.37
  263.62   22.37  263.62   37.37  264.62   37.37  264.62   22.37  279.62   22.37
  279.62   39.54  279.72   39.54  559.19    41.2  668.13   40.32  701.96   41.24
   720.8    40.9  782.58   41.03  803.18   41.69  826.96   42.33  842.65   41.68
  915.04   42.92  937.04   42.78  967.88   43.42   985.5   42.63 1029.71   42.85
#Mann= 10 ,-1 , 0
       0      99       0   61.78    .016       0  113.27     .03       0
  175.05    .016       0  248.52    .011       0  279.72    .016       0
   720.8    .013       0  782.58     .03       0  803.18    .016       0
  937.04     .03       0
#XS Ineff= 4 ,-1
       0   92.67      60  154.46  195.65      60  279.72   700.2      60
  844.36 1029.71      60
Permanent Ineff=
       F       F       F       F
#Block Obstruct= 1 ,-1
       0   61.78      85
#XS Lid=5
  248.62   39.69   37.37  250.46   39.61   37.37  261.93   39.62   37.37
   269.6   39.55   37.37  279.62   39.54   37.37
Bank Sta=248.62,279.62
XS Rating Curve= 0 ,0
Exp/Cntr=0.3,0.1

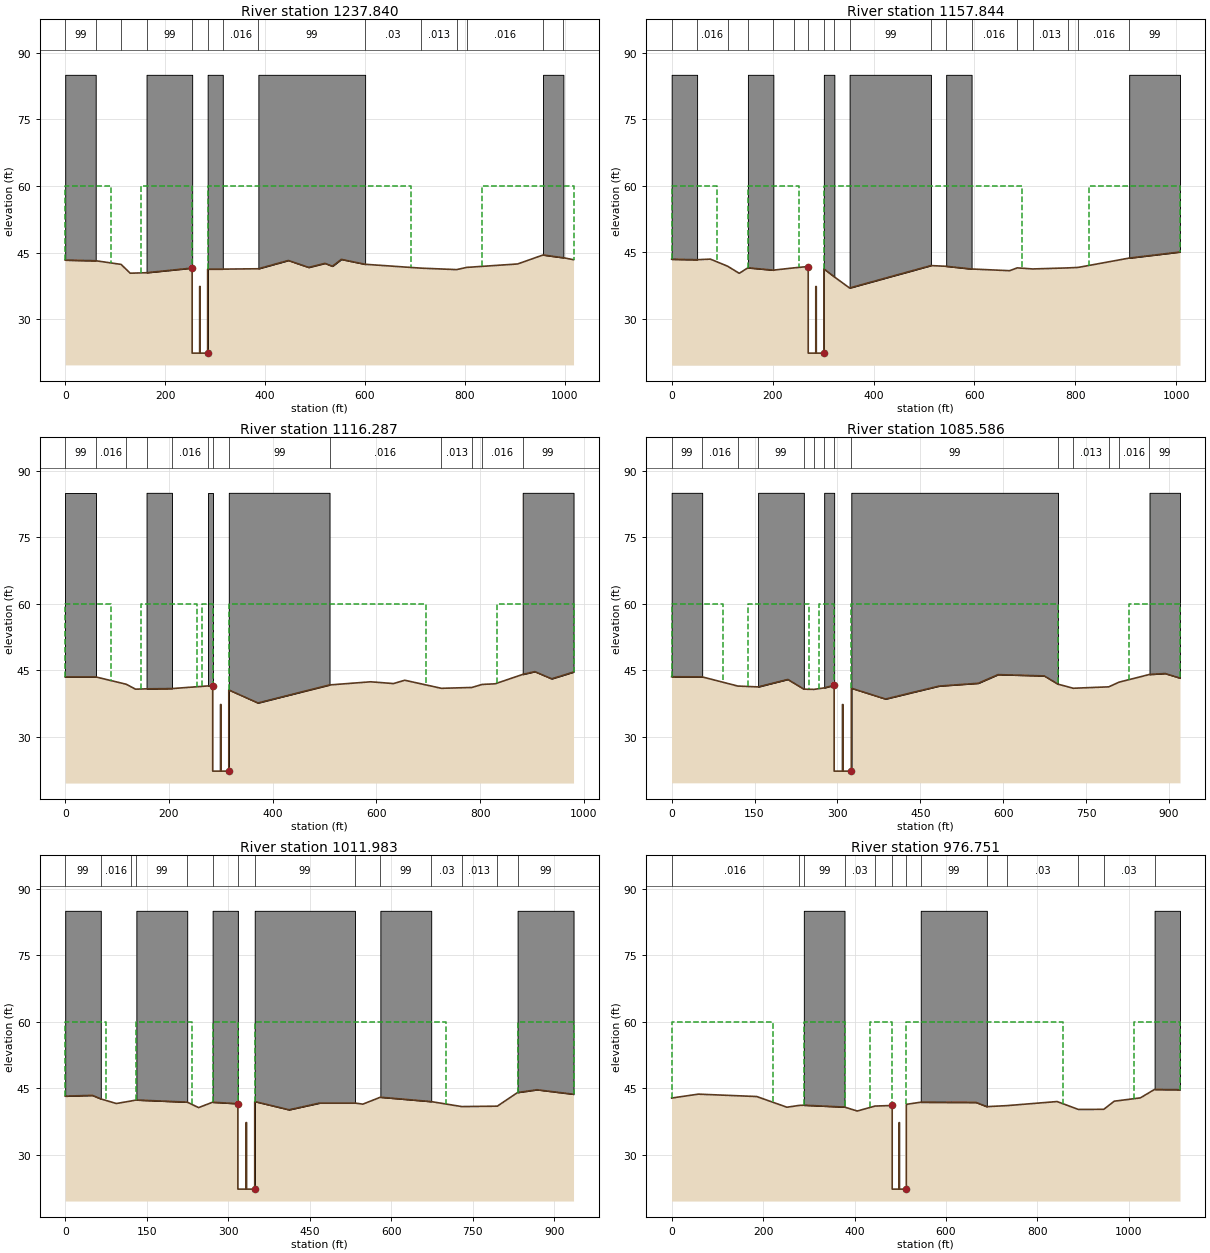
Type RM Length L Ch R = 1 ,1237.840,87.9,80,66.23
XS GIS Cut Line= 4
     3113089.745    13823509.343     3112967.762    13823309.166
     3112908.335    13823249.738     3112539.258    13822655.463
#Sta/Elev= 30
       0   43.29   61.08   43.15  111.98   42.32  130.17   40.34  162.88   40.45
  254.17    41.5  254.27    41.6  254.27   22.35  269.27   22.35  269.27   37.35
  270.27   37.35  270.27   22.35  285.27   22.35  285.27   41.26  285.37   41.26
  315.58   41.26  386.85   41.34  446.91   43.21  487.57   41.64  520.25   42.56
  535.19    41.9  552.92   43.45  600.63   42.35  712.61   41.48  783.87   41.15
  804.23   41.65     906   42.42  956.94   44.44  997.66   43.82 1018.02   43.38
#Mann= 14 ,-1 , 0
       0      99       0   61.08    .016       0  111.98     .03       0
  162.88      99       0  254.17    .011       0  285.37      99       0
  315.58    .016       0  386.85      99       0  600.63     .03       0
  712.61    .013       0  783.87     .03       0  804.23    .016       0
  956.94      99       0  997.66     .03       0
#XS Ineff= 4 ,-1
       0   91.62      60   152.7  254.17      60  285.37  692.25      60
  834.77 1018.02      60
Permanent Ineff=
       F       F       F       F
#Block Obstruct= 5 ,-1
       0   61.08      85  162.88  254.27      85  285.27  315.58      85
  386.85  600.63      85  956.94  997.66      85
#XS Lid=6
  254.27      85   37.35  264.68      85   37.35  264.68    41.5   37.35
  274.86   41.34   37.35  274.86      85   37.35  285.27      85   37.35
Bank Sta=254.27,285.27
XS Rating Curve= 0 ,0
Exp/Cntr=0.3,0.1

Type RM Length L Ch R = 1 ,1157.844,44.64,41.56,42.09
XS GIS Cut Line= 4
     3113158.556    13823459.298      3113055.34    13823277.888
     3112930.229    13823165.288     3112601.814    13822627.313
#Sta/Elev= 30
       0   43.46   50.37   43.35   76.73   43.49  110.81   41.89  133.95   40.29
   151.1   41.53  201.47      41  241.76   41.51  270.48   41.82  270.58   41.82
  270.58   22.31  285.58   22.31  285.58   37.31  286.58   37.31  286.58   22.31
  301.58   22.31  301.58   41.29  301.68   41.29  322.35   39.48  352.57   36.98
  513.74   42.03  543.96   41.87  594.33   41.26  669.55   40.88  684.99   41.52
  715.21   41.27  785.72   41.51  805.87   41.62   906.6   43.72 1007.33   45.09
#Mann= 18 ,-1 , 0
       0      99       0   50.37    .016       0  110.81     .03       0
   151.1      99       0  201.47    .016       0  241.76     .03       0
  270.48    .011       0  301.68      99       0  322.35     .03       0
  352.57      99       0  513.74    .016       0  543.96      99       0
  594.33    .016       0  684.99     .03       0  715.21    .013       0
  785.72     .03       0  805.87    .016       0   906.6      99       0
#XS Ineff= 4 ,-1
       0   90.66      60   151.1  251.83      60  301.68  695.06      60
  826.01 1007.33      60
Permanent Ineff=
       F       F       F       F
#Block Obstruct= 6 ,-1
       0   50.37      85   151.1  201.47      85  301.58  322.35      85
  352.57  513.74      85  543.96  594.33      85   906.6 1007.33      85
#XS Lid=4
  270.58   41.82   37.31  271.98   41.84   37.31  271.98      85   37.31
  301.58      85   37.31
Bank Sta=270.58,301.58
XS Rating Curve= 0 ,0
Exp/Cntr=0.3,0.1

Type RM Length L Ch R = 1 ,1116.287,23.67,30.7,30.26
XS GIS Cut Line= 4
     3113199.217    13823437.404     3113096.001    13823262.249
     3112964.634    13823137.139     3112651.858    13822630.441
#Sta/Elev= 30
       0   43.52   58.81   43.52  117.62   41.87  135.55   40.76  156.83   40.83
  205.84   40.89  274.45   41.48  284.34   41.48  284.44   41.48  284.44   22.29
  299.44   22.29  299.44   37.29  300.44   37.29  300.44   22.29  315.44   22.29
  315.44   40.58  315.54   40.58  371.69   37.65  509.69   41.71  589.32   42.42
  632.92   42.02  654.72   42.77  725.33   40.95  784.14   41.14  803.74   41.82
  829.11   41.97  882.16   44.08  905.41   44.71  938.11   43.09  980.17   44.61
#Mann= 13 ,-1 , 0
       0      99       0   58.81    .016       0  117.62     .03       0
  156.83      99       0  205.84    .016       0  274.45      99       0
  284.34    .011       0  315.54      99       0  509.69    .016       0
  725.33    .013       0  784.14     .03       0  803.74    .016       0
  882.16      99       0
#XS Ineff= 5 ,-1
       0   88.22      60  147.03  254.85      60  264.65  284.34      60
  315.54  695.92      60  833.15  980.17      60
Permanent Ineff=
       F       F       F       F       F
#Block Obstruct= 5 ,-1
       0   58.81      85  156.83  205.84      85  274.45  284.44      85
  315.44  509.69      85  882.16  980.17      85
#XS Lid=2
  284.44      85   37.29  315.44      85   37.29
Bank Sta=284.44,315.44
XS Rating Curve= 0 ,0
Exp/Cntr=0.3,0.1

Type RM Length L Ch R = 1 ,1085.586,71.69,73.6,61.94
XS GIS Cut Line= 4
     3113217.983    13823428.021     3113108.512    13823230.971
     3113005.295    13823134.011     3112708.158    13822667.974
#Sta/Elev= 30
       0   43.55   55.18   43.51  119.57   41.45  156.36   41.25  210.19   42.94
  239.13   40.75  257.53   40.69  275.92   41.03   293.9   41.63     294   41.63
     294   22.27     309   22.27     309   37.27     310   37.27     310   22.27
     325   22.27     325   40.96   325.1   40.96  386.98   38.52  483.72   41.44
  554.69   42.07  590.46   44.02  674.18   43.73     699   41.87  726.59   40.95
  790.97   41.27  809.37   42.32  864.55   44.06  892.88   44.27  919.74   43.24
#Mann= 14 ,-1 , 0
       0      99       0   55.18    .016       0  119.57     .03       0
  156.36      99       0  239.13     .03       0  257.53    .016       0
  275.92      99       0   293.9    .011       0   325.1      99       0
     699     .03       0  726.59    .013       0  790.97     .03       0
  809.37    .016       0  864.55      99       0
#XS Ineff= 5 ,-1
       0   91.97      60  137.96  248.33      60  266.72   293.9      60
   325.1     699      60  827.76  919.74      60
Permanent Ineff=
       F       F       F       F       F
#Block Obstruct= 5 ,-1
       0   55.18      85  156.36  239.13      85  275.92     294      85
     325     699      85  864.55  919.74      85
#XS Lid=2
     294      85   37.27     325      85   37.27
Bank Sta=294,325
XS Rating Curve= 0 ,0
Exp/Cntr=0.3,0.1

Type RM Length L Ch R = 1 ,1011.983,29.99,35.23,47.25
XS GIS Cut Line= 4
     3113283.666    13823393.615     3113155.428    13823174.672
     3113030.317    13823055.817     3112755.074    13822627.313
#Sta/Elev= 30
       0    43.2   49.83   43.38   65.49   42.58   94.16   41.54  121.63   42.12
  130.98   42.33  224.54   41.85  245.53   40.62  271.32   41.83  317.72   41.49
  317.82   41.49  317.82   22.23  332.82   22.23  332.82   37.23  333.82   37.23
  333.82   22.23  348.82   22.23  348.82   41.98  348.92   41.98  412.07   40.12
  468.13   41.64  533.29   41.64  547.95    41.4  580.07   42.96  673.62   41.97
  729.76   40.85  795.25   40.94  832.67   44.02  868.43   44.64  935.59   43.63
#Mann= 14 ,-1 , 0
       0      99       0   65.49    .016       0  121.63     .03       0
  130.98      99       0  224.54     .03       0  271.32      99       0
  317.72    .011       0  348.92      99       0  533.29    .016       0
  580.07      99       0  673.62     .03       0  729.76    .013       0
  795.25     .03       0  832.67      99       0
#XS Ineff= 5 ,-1
       0   74.85      60  130.98   233.9      60  271.32  317.72      60
  348.92  701.69      60  832.67  935.59      60
Permanent Ineff=
       F       F       F       F       F
#Block Obstruct= 6 ,-1
       0   65.49      85  130.98  224.54      85  271.32  317.82      85
  348.82  533.29      85  580.07  673.62      85  832.67  935.59      85
#XS Lid=2
  317.82      85   37.23  348.82      85   37.23
Bank Sta=317.82,348.82
XS Rating Curve= 0 ,0
Exp/Cntr=0.8,0.6

Type RM Length L Ch R = 1 ,976.751 ,20.03,23.36,51.62
XS GIS Cut Line= 5
     3113391.935    13823509.668     3113323.835    13823406.116
     3113177.322     13823149.65     3113080.362    13823052.689
     3112783.224    13822583.524
#Sta/Elev= 30
       0   42.76   58.33   43.64  186.06    43.1  252.03   40.69  277.94   41.09
  289.06   41.15     378   40.72  405.95   39.83  444.71   40.95  482.19   41.08
  482.29   41.08  482.29   22.21  497.29   22.21  497.29   37.21  498.29   37.21
  498.29   22.21  513.29   22.21  513.29   41.34  513.39   41.34  544.77   41.82
  665.41   41.78   689.3   40.82  733.77   41.05  842.96   41.97  889.42   40.19
     945   40.21  967.96   42.05 1025.15    42.8 1056.18   44.71 1111.77   44.65
#Mann= 13 ,-1 , 0
       0    .016       0  277.94     .03       0  289.06      99       0
     378     .03       0  444.71    .016       0  482.19    .011       0
  513.39    .016       0  544.77      99       0   689.3    .016       0
  733.77     .03       0  889.42    .013       0     945     .03       0
 1056.18      99       0
#XS Ineff= 5 ,-1
       0  222.35      60  289.06     378      60  433.59  482.19      60
  513.39  856.06      60 1011.71 1111.77      60
Permanent Ineff=
       F       F       F       F       F
#Block Obstruct= 3 ,-1
  289.06     378      85  544.77   689.3      85 1056.18 1111.77      85
#XS Lid=6
  482.29   41.08   37.21  486.83   41.07   37.21  491.27   40.97   37.21
  495.71    41.1   37.21  508.05   41.31   37.21  513.29   41.33   37.21
Bank Sta=482.29,513.29
XS Rating Curve= 0 ,0
Exp/Cntr=0.8,0.6