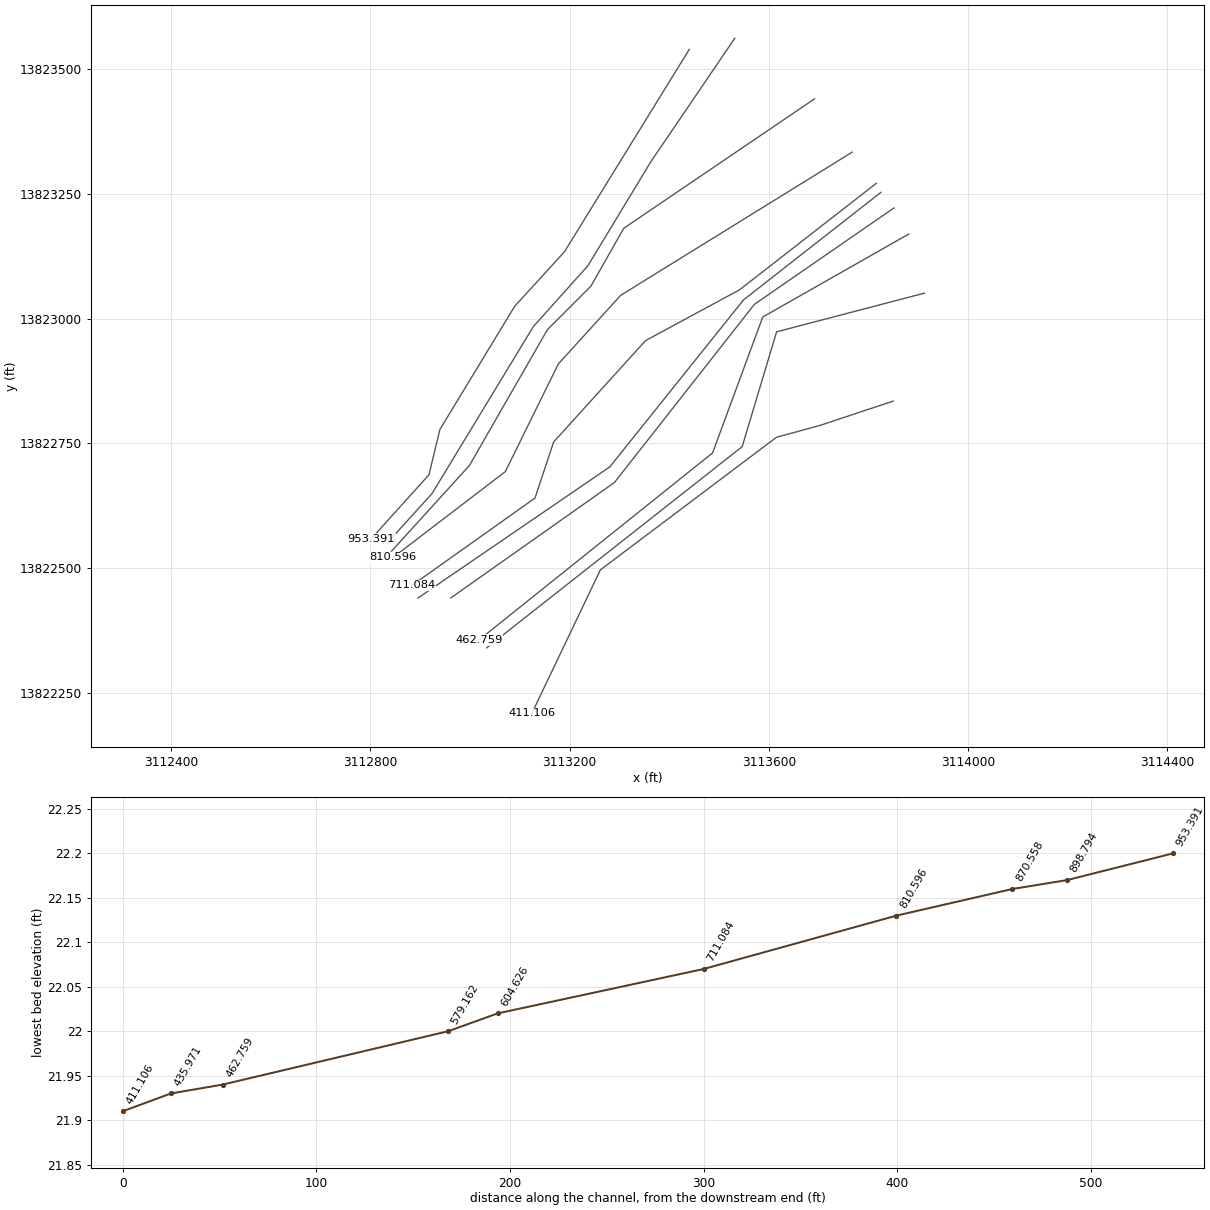
HEC-RAS study D109-00-00.prj: D109-00-00

--- D109-00-00.g01 (geometry) --- (continued)

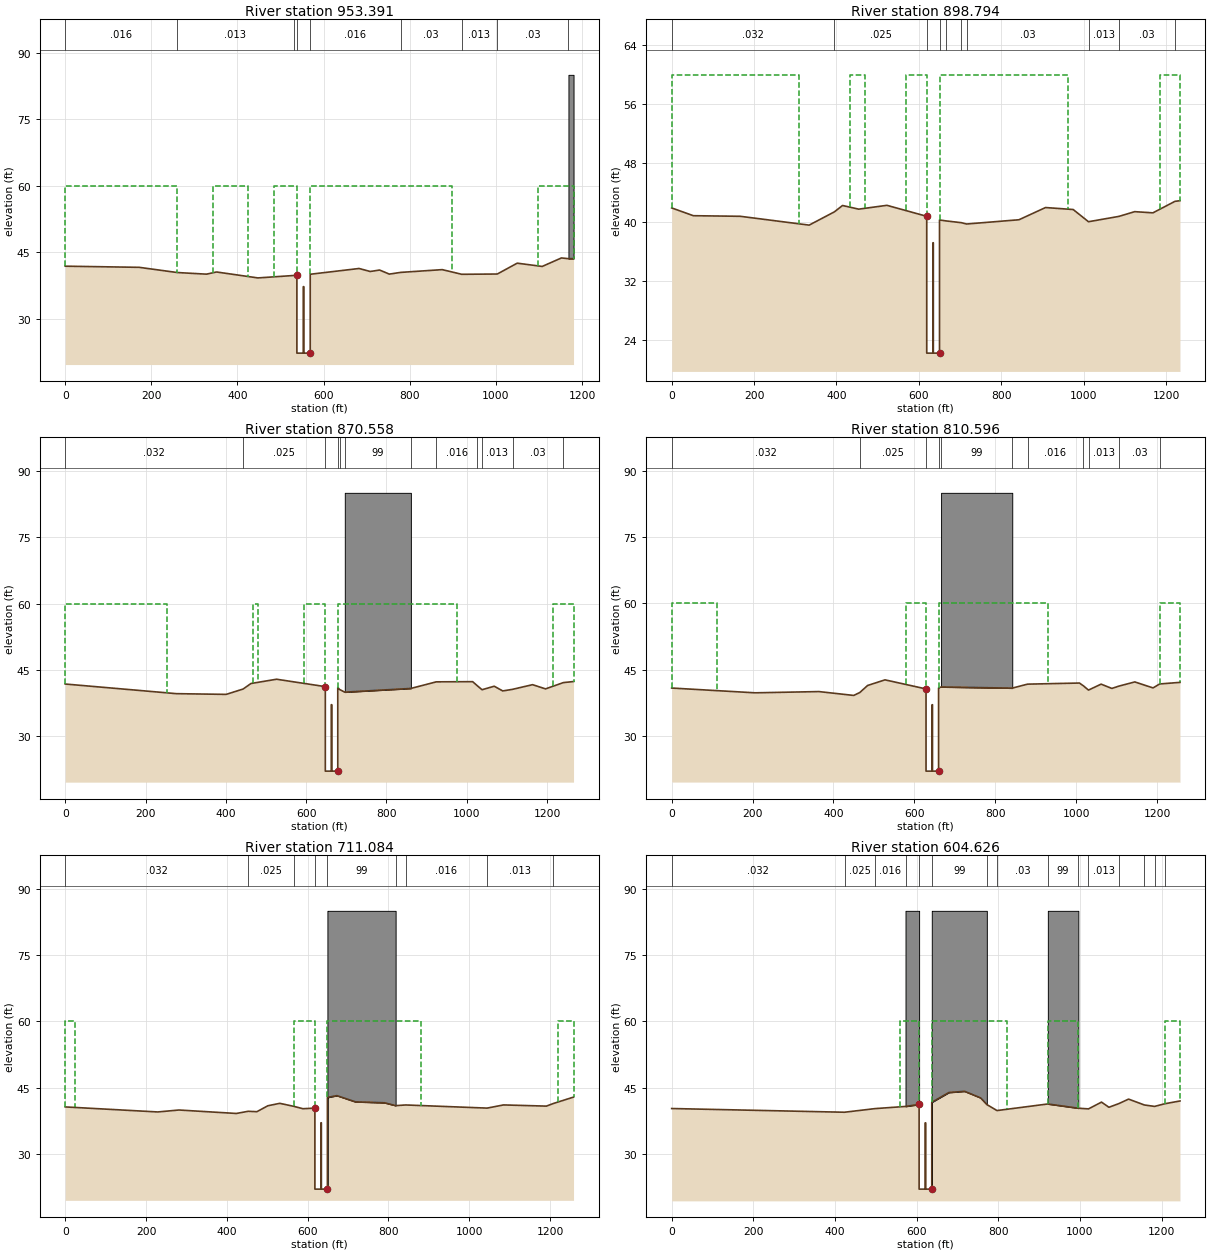
Type RM Length L Ch R = 1 ,953.391 ,58.09,54.6,44.42
XS GIS Cut Line= 6
     3113440.169    13823539.651     3113189.833    13823134.011
     3113089.745    13823024.539     3112939.612    13822777.446
     3112917.718     13822686.74     3112801.991    13822558.502
#Sta/Elev= 30
       0   41.82  171.91   41.56  259.67   40.39  328.06   40.02  351.48   40.51
  447.49   39.17  531.15   39.72  537.82   39.84  537.92   39.84  537.92    22.2
  552.92    22.2  552.92    37.2  553.92    37.2  553.92    22.2  568.92    22.2
  568.92      40  569.02      40  682.39    41.3  708.19   40.62  730.03   40.95
   752.6   40.03  779.02   40.42  875.46   41.04  920.66   39.99 1003.28   40.05
  1049.6    42.5 1107.55   41.76 1152.22   43.68 1168.52   43.51 1180.33   43.53
#Mann= 9 ,-1 , 0
       0    .016       0  259.67    .013       0  531.15    .016       0
  537.82    .011       0  569.02    .016       0  779.02     .03       0
  920.66    .013       0 1003.28     .03       0 1168.52      99       0
#XS Ineff= 5 ,-1
       0  259.67      60  342.29  424.92      60  483.93  537.82      60
  569.02  897.05      60  1097.7 1180.33      60
Permanent Ineff=
       F       F       F       F       F
#Block Obstruct= 1 ,-1
 1168.52 1180.33      85
#XS Lid=5
  537.92   39.84    37.2   543.9   39.85    37.2  552.95   39.85    37.2
  561.46   39.98    37.2  568.92      40    37.2
Bank Sta=537.92,568.92
XS Rating Curve= 0 ,0
Exp/Cntr=0.5,0.3

Type RM Length L Ch R = 1 ,898.794 ,39.32,28.24,28.39
XS GIS Cut Line= 6
     3113531.423    13823561.813      3113363.21    13823314.667
      3113236.75    13823105.861     3113127.278    13822983.878
     3112923.973    13822649.207     3112833.268    13822549.119
#Sta/Elev= 30
       0   41.91   52.57   40.85  166.44   40.77  333.68   39.57  394.82   41.37
  414.75   42.24  453.82   41.74  522.51   42.26  619.01   40.77  619.11   40.77
  619.11   22.17  634.11   22.17  634.11   37.17  635.11   37.17  635.11   22.17
  650.11   22.17  650.11   40.27  650.21   40.27  666.26   40.14  703.28    39.9
  715.61   39.72  842.98    40.3  907.47   41.96  974.62   41.69 1011.73   40.03
 1085.76   40.76 1123.83    41.4 1168.11   41.24 1221.48    42.8 1233.82   42.89
#Mann= 10 ,-1 , 0
       0    .032       0  394.82    .025       0  619.01    .011       0
  650.21    .016       0  666.26     .03       0  703.28    .013       0
  715.61     .03       0 1011.73    .013       0 1085.76     .03       0
 1221.48    .016       0
#XS Ineff= 5 ,-1
       0  308.45      60  431.84  468.85      60  567.56  619.01      60
  650.21  962.38      60 1184.46 1233.82      60
Permanent Ineff=
       F       F       F       F       F
#XS Lid=6
  619.11   40.77   37.17  636.17   40.47   37.17  636.84   40.44   37.17
  637.45   40.45   37.17   648.7   40.28   37.17  650.11   40.27   37.17
Bank Sta=619.11,650.11
XS Rating Curve= 0 ,0
Exp/Cntr=0.5,0.3

Type RM Length L Ch R = 1 ,870.558 ,112.63,59.96,49.51
XS GIS Cut Line= 6
     3113691.768    13823440.576     3113308.689    13823180.927
     3113243.006      13823065.2     3113155.428    13822977.622
      3112999.04    13822705.507     3112842.652     13822533.48
#Sta/Elev= 30
       0   41.83  277.16   39.65  400.95   39.49  443.12    40.7  462.78   41.95
  526.38   42.91  647.74   41.24  647.84   41.24  647.84   22.16  662.84   22.16
  662.84   37.16  663.84   37.16  663.84   22.16  678.84   22.16  678.84   41.03
  678.94   41.03  683.66   40.58  696.32   39.99  860.91   40.83  924.21   42.32
 1014.77   42.36  1025.5   41.51 1038.16   40.54 1068.49   41.33 1089.73   40.27
 1114.12   40.63 1164.06   41.68 1196.29   40.73 1240.72   42.15 1266.04   42.39
#Mann= 12 ,-1 , 0
       0    .032       0  443.12    .025       0  647.74    .011       0
  678.94    .016       0  683.66     .03       0  696.32      99       0
  860.91     .03       0  924.21    .016       0  1025.5     .03       0
 1038.16    .013       0 1114.12     .03       0 1240.72    .016       0
#XS Ineff= 5 ,-1
       0  253.21      60  468.44   481.1      60  595.04  647.74      60
  678.94  974.85      60  1215.4 1266.04      60
Permanent Ineff=
       F       F       F       F       F
#Block Obstruct= 1 ,-1
  696.32  860.91      85
#XS Lid=6
  647.84   41.24   37.16  665.15   41.02   37.16  671.41   41.01   37.16
  671.74      41   37.16  675.76   40.94   37.16  678.84   41.03   37.16
Bank Sta=647.84,678.84
XS Rating Curve= 0 ,0
Exp/Cntr=0.3,0.1

Type RM Length L Ch R = 1 ,810.596 ,110.43,99.51,75.35
XS GIS Cut Line= 5
     3113767.378    13823333.679     3113302.433    13823046.433
     3113177.322    13822908.812     3113070.978    13822692.996
     3112845.779    13822520.969
#Sta/Elev= 30
       0    40.9  206.27   39.82  363.91    40.1  449.97   39.23   464.9   39.88
  484.34   41.48  527.39   42.75  628.63    40.7  628.73    40.7  628.73   22.13
  643.73   22.13  643.73   37.13  644.73   37.13  644.73   22.13  659.73   22.13
  659.73   40.91  659.83   40.91  665.94   41.14  841.85   40.88  879.54   41.78
  1007.9   42.03 1017.76    41.4 1030.32   40.44 1061.41   41.78 1088.13   40.81
 1105.71   41.34 1144.75   42.28 1189.83   40.93 1206.23   41.82 1256.49   42.18
#Mann= 11 ,-1 , 0
       0    .032       0   464.9    .025       0  628.63    .011       0
  659.83     .03       0  665.94      99       0  841.85     .03       0
  879.54    .016       0 1017.76     .03       0 1030.32    .013       0
 1105.71     .03       0 1206.23    .016       0
#XS Ineff= 4 ,-1
       0  113.08      60  577.99  628.63      60  659.83   929.8      60
 1206.23 1256.49      60
Permanent Ineff=
       F       F       F       F
#Block Obstruct= 1 ,-1
  665.94  841.85      85
#XS Lid=7
  628.73    40.7   37.13   630.2   40.63   37.13  634.06   40.38   37.13
  642.22   39.79   37.13   647.4   40.02   37.13   655.3   40.65   37.13
  659.73   40.91   37.13
Bank Sta=628.73,659.73
XS Rating Curve= 0 ,0
Exp/Cntr=0.3,0.1

Type RM Length L Ch R = 1 ,711.084 ,61.29,106.46,31.39
XS GIS Cut Line= 6
     3113815.612    13823271.105     3113541.048    13823057.497
     3113352.477    13822955.728     3113167.939    13822752.423
     3113130.406    13822639.824     3112883.312    13822464.669
#Sta/Elev= 30
       0   40.66  229.12   39.52  281.66   39.96  423.41   39.18     453   39.67
  474.54   39.58  501.64   40.92  531.07   41.47  566.26   40.78  588.61   40.25
     618   40.39   618.1   40.39   618.1   22.07   633.1   22.07   633.1   37.07
   634.1   37.07   634.1   22.07   649.1   22.07   649.1    42.8   649.2    42.8
  672.64   43.21  718.11   41.81  790.56   41.59  817.93   40.95  843.09    41.1
 1044.43   40.39 1085.19   41.11 1191.16   40.84 1208.01   41.42 1258.35   42.88
#Mann= 9 ,-1 , 0
       0    .032       0     453    .025       0  566.26    .016       0
     618    .011       0   649.2      99       0  817.93     .03       0
  843.09    .016       0 1044.43    .013       0 1208.01     .03       0
#XS Ineff= 4 ,-1
       0   25.17      60  566.26     618      60   649.2  880.84      60
  1220.6 1258.35      60
Permanent Ineff=
       F       F       F       F
#Block Obstruct= 1 ,-1
   649.1  817.93      85
#XS Lid=8
   618.1   40.39   37.07  620.97   40.44   37.07  627.18   40.57   37.07
   631.6   40.87   37.07  635.49   41.56   37.07  641.88   42.29   37.07
  641.88      85   37.07   649.1      85   37.07
Bank Sta=618.1,649.1
XS Rating Curve= 0 ,0
Exp/Cntr=0.3,0.1

Type RM Length L Ch R = 1 ,604.626 ,23.59,25.47,34.77
XS GIS Cut Line= 4
     3113824.737    13823252.855     3113549.151     13823037.39
     3113280.539    13822702.379     3112895.824    13822439.647
#Sta/Elev= 30
       0   40.26  423.33   39.42  498.04   40.24  572.74   40.73     606   41.18
   606.1   41.18   606.1   22.02   621.1   22.02   621.1   37.02   622.1   37.02
   622.1   22.02   637.1   22.02   637.1   41.67   637.2   41.67  678.93   43.88
  717.38   44.16  756.78   42.66  771.95   41.16  796.86    39.8  921.36   41.29
  996.07   40.33 1020.97   40.18 1052.85   41.71 1071.02   40.54 1095.68   41.39
 1119.24   42.39 1157.93   41.06 1182.83   40.74 1207.74   41.34 1245.09   41.97
#Mann= 15 ,-1 , 0
       0    .032       0  423.33    .025       0  498.04    .016       0
  572.74      99       0     606    .011       0   637.2      99       0
  771.95    .016       0  796.86     .03       0  921.36      99       0
  996.07     .03       0 1020.97    .013       0 1095.68    .016       0
 1157.93     .03       0 1182.83    .013       0 1207.74     .03       0
#XS Ineff= 4 ,-1
  560.29     606      60   637.2  821.76      60  921.36  996.07      60
 1207.74 1245.09      60
Permanent Ineff=
       F       F       F       F
#Block Obstruct= 3 ,-1
  572.74   606.1      85   637.1  771.95      85  921.36  996.07      85
#XS Lid=2
   606.1      85   37.02   637.1      85   37.02
Bank Sta=606.1,637.1
XS Rating Curve= 0 ,0
Exp/Cntr=0.3,0.1

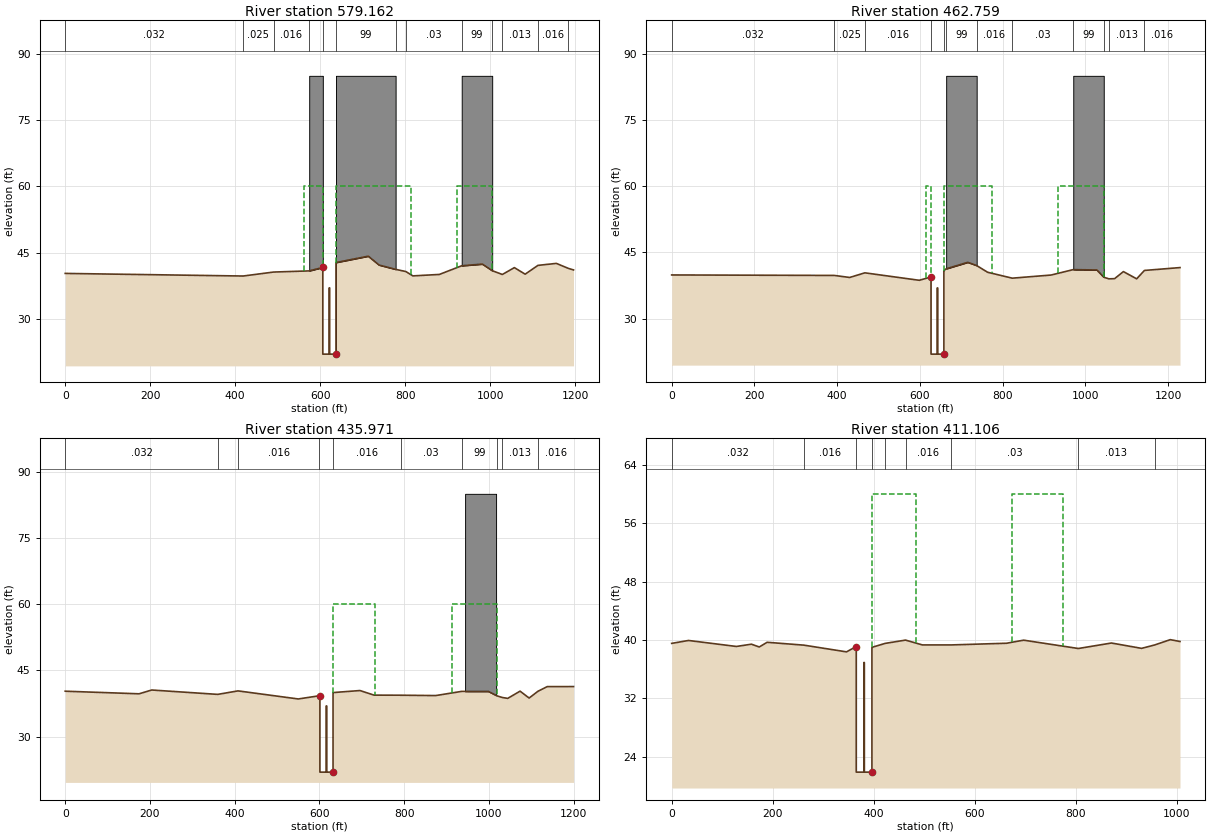
Type RM Length L Ch R = 1 ,579.162 ,58.23,116.4,92.14
XS GIS Cut Line= 4
      3113850.81    13823221.568     3113570.856    13823028.377
     3113289.922    13822671.101     3112961.507    13822439.647
#Sta/Elev= 30
       0   40.27  418.75   39.68  490.53   40.58  574.28   40.84  606.23   41.62
  606.33   41.62  606.33      22  621.33      22  621.33      37  622.33      37
  622.33      22  637.33      22  637.33   42.73  637.43   42.73  713.34   44.17
  738.58   42.17  777.67   41.19   801.6    40.7  818.26   39.71  880.71   40.04
  933.21      42  981.82   42.38 1004.99   40.89 1028.92   40.03 1057.17   41.58
 1082.57    40.1 1112.67   42.09 1155.97   42.54 1184.46    41.4 1196.42   41.06
#Mann= 13 ,-1 , 0
       0    .032       0  418.75    .025       0  490.53    .016       0
  574.28      99       0  606.23    .011       0  637.43      99       0
  777.67    .016       0   801.6     .03       0  933.21      99       0
 1004.99     .03       0 1028.92    .013       0 1112.67    .016       0
 1184.46     .03       0
#XS Ineff= 3 ,-1
  562.32  606.23      60  637.43  813.57      60  921.25 1004.99      60
Permanent Ineff=
       F       F       F
#Block Obstruct= 3 ,-1
  574.28  606.33      85  637.33  777.67      85  933.21 1004.99      85
#XS Lid=2
  606.33      85      37  637.33      85      37
Bank Sta=606.33,637.33
XS Rating Curve= 0 ,0
Exp/Cntr=0.3,0.1

Type RM Length L Ch R = 1 ,462.759 ,41.87,26.79,23.33
XS GIS Cut Line= 4
     3113880.793    13823169.423     3113587.658    13823002.975
     3113486.971    13822730.529     3113017.806    13822355.197
#Sta/Elev= 30
       0   39.88  393.08   39.77  430.22   39.31  466.78   40.36  598.21   38.67
  626.68   39.42  626.78   39.42  626.78   21.94  641.78   21.94  641.78   36.94
  642.78   36.94  642.78   21.94  657.78   21.94  657.78   40.86  657.88   40.86
  663.32   41.27  715.45   42.74  737.03   42.01  763.47   40.49  823.01   39.15
  916.78   39.86  970.42   41.09 1027.61      41 1044.12   39.37  1056.4      39
  1070.3   39.04 1091.64   40.64 1123.65      39 1142.39    40.9 1228.38   41.55
#Mann= 12 ,-1 , 0
       0    .032       0  393.08    .025       0  466.78    .016       0
  626.68    .011       0  657.88    .016       0  663.32      99       0
  737.03    .016       0  823.01     .03       0  970.42      99       0
 1044.12     .03       0  1056.4    .013       0 1142.39    .016       0
#XS Ineff= 3 ,-1
  614.19  626.68      60  657.88  773.88      60  933.57 1044.12      60
Permanent Ineff=
       F       F       F
#Block Obstruct= 2 ,-1
  663.32  737.03      85  970.42 1044.12      85
#XS Lid=6
  626.78   39.42   36.94  632.75   39.68   36.94  643.42   39.87   36.94
  643.43   39.87   36.94   643.5   39.88   36.94  657.78   40.86   36.94
Bank Sta=626.78,657.78
XS Rating Curve= 0 ,0
Exp/Cntr=0.3,0.1

Type RM Length L Ch R = 1 ,435.971 ,145.29,24.86,81.22
XS GIS Cut Line= 4
      3113912.08    13823050.794     3113615.477    13822973.302
     3113546.399     13822743.04     3113033.445    13822339.558
#Sta/Elev= 30
       0   40.27  174.28   39.68  204.14   40.54  359.88   39.55  407.86   40.34
  549.98   38.51  599.94   39.24  601.04   39.24  601.04   21.93  616.04   21.93
  616.04   36.93  617.04   36.93  617.04   21.93  632.04   21.93  632.04   39.96
  632.14   39.96   695.6   40.42   728.8   39.38  791.73   39.36  874.37   39.28
  935.68   40.23  998.63   40.22 1019.65   39.19 1031.64   38.84  1044.2   38.64
  1073.4   40.28 1094.76   38.72 1115.61   40.25 1137.49   41.31 1199.58   41.32
#Mann= 10 ,-1 , 0
       0    .032       0  359.88    .025       0  407.86    .016       0
  599.94    .011       0  632.14    .016       0  791.73     .03       0
  935.68      99       0 1019.65     .03       0 1031.64    .013       0
 1115.61    .016       0
#XS Ineff= 2 ,-1
  632.14  731.75      60  911.68 1019.65      60
Permanent Ineff=
       F       F
#Block Obstruct= 1 ,-1
   943.7 1016.81      85
#XS Lid=5
  601.04   39.24   36.93  603.39   39.29   36.93  607.48   39.46   36.93
  619.48   39.83   36.93  632.04   39.96   36.93
Bank Sta=601.04,632.04
XS Rating Curve= 0 ,0
Exp/Cntr=0.3,0.1

Type RM Length L Ch R = 1 ,411.106 ,72.93,48.62,88.19
XS GIS Cut Line= 5
     3113849.506    13822834.393     3113703.018    13822785.755
      3113615.21    13822761.807     3113261.772    13822495.947
      3113124.15    13822208.192
#Sta/Elev= 30
       0   39.53   33.38   39.93  128.03   39.11  157.92   39.42  173.47   39.04
  189.02   39.68  261.72   39.29  346.27   38.37  365.45    39.1  365.55    39.1
  365.55   21.91  380.55   21.91  380.55   36.91  381.55   36.91  381.55   21.91
  396.55   21.91  396.55   38.99  396.65   38.99  422.77   39.53  463.04   39.98
  496.43   39.32  553.63   39.32  663.22   39.55  697.03   39.97  805.28   38.83
  870.89   39.58  930.53   38.85  956.27   39.31  987.29   40.04  1006.6   39.79
#Mann= 9 ,-1 , 0
       0    .032       0  261.72    .016       0  365.45    .011       0
  396.65    .016       0  422.77     .03       0  463.04    .016       0
  553.63     .03       0  805.28    .013       0  956.27    .032       0
#XS Ineff= 2 ,-1
  396.65  483.17      60  674.43  775.09      60
Permanent Ineff=
       F       F
#XS Lid=4
  365.55    39.1   36.91  375.21   39.13   36.91  383.81   38.98   36.91
  396.55   38.99   36.91
Bank Sta=365.55,396.55
XS Rating Curve= 0 ,0
Exp/Cntr=0.3,0.1