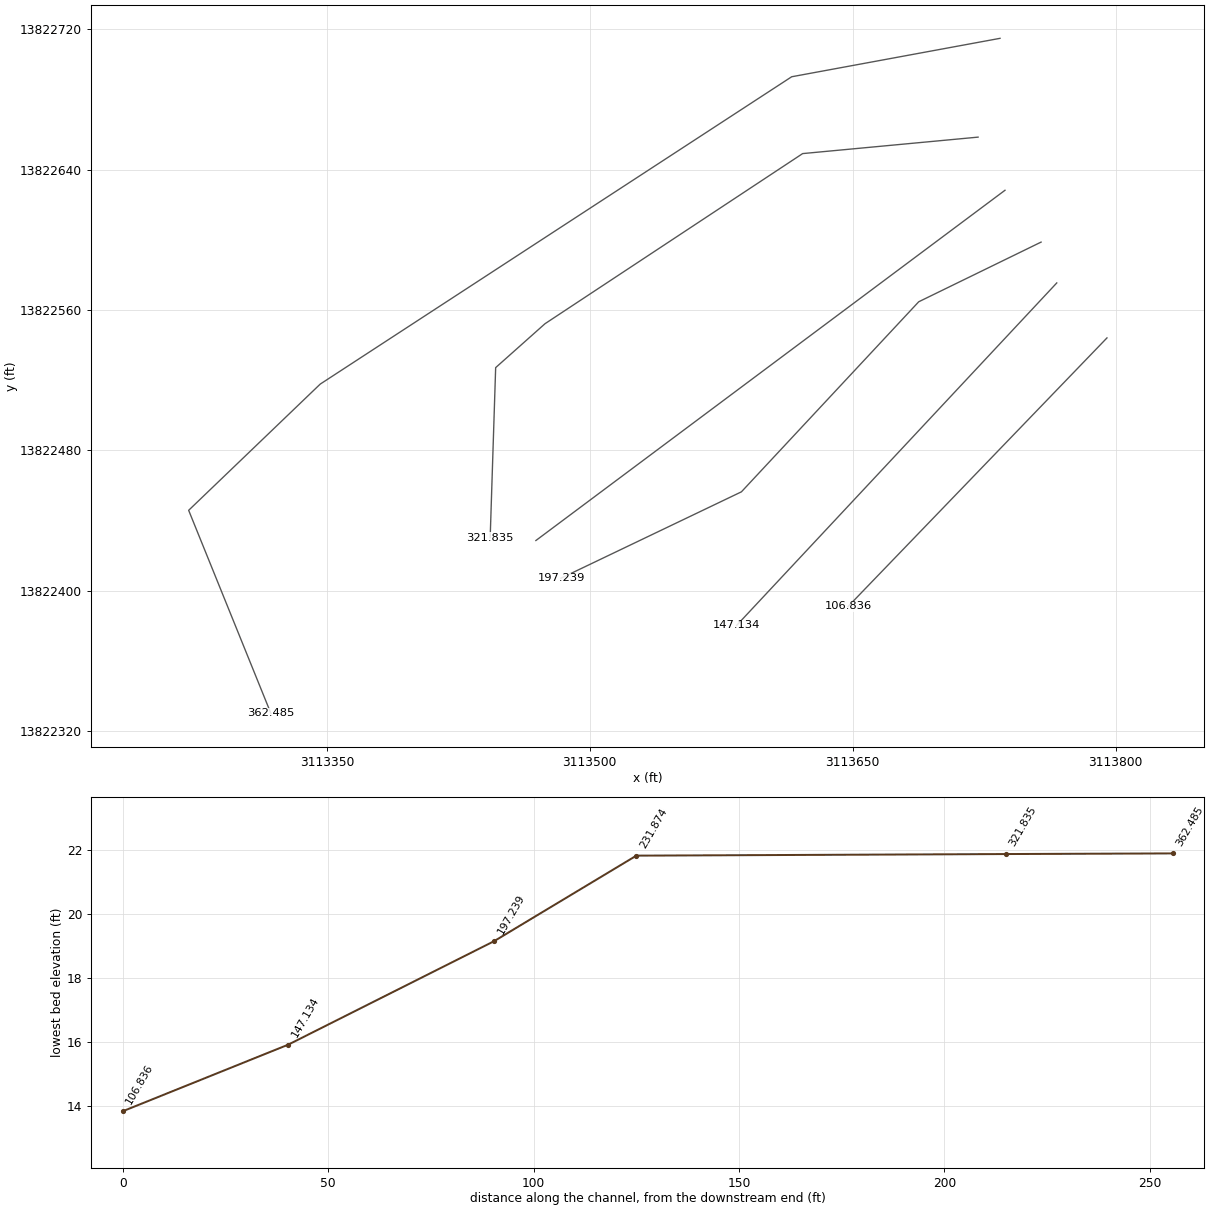
HEC-RAS study D109-00-00.prj: D109-00-00

--- D109-00-00.g01 (geometry) --- (continued)

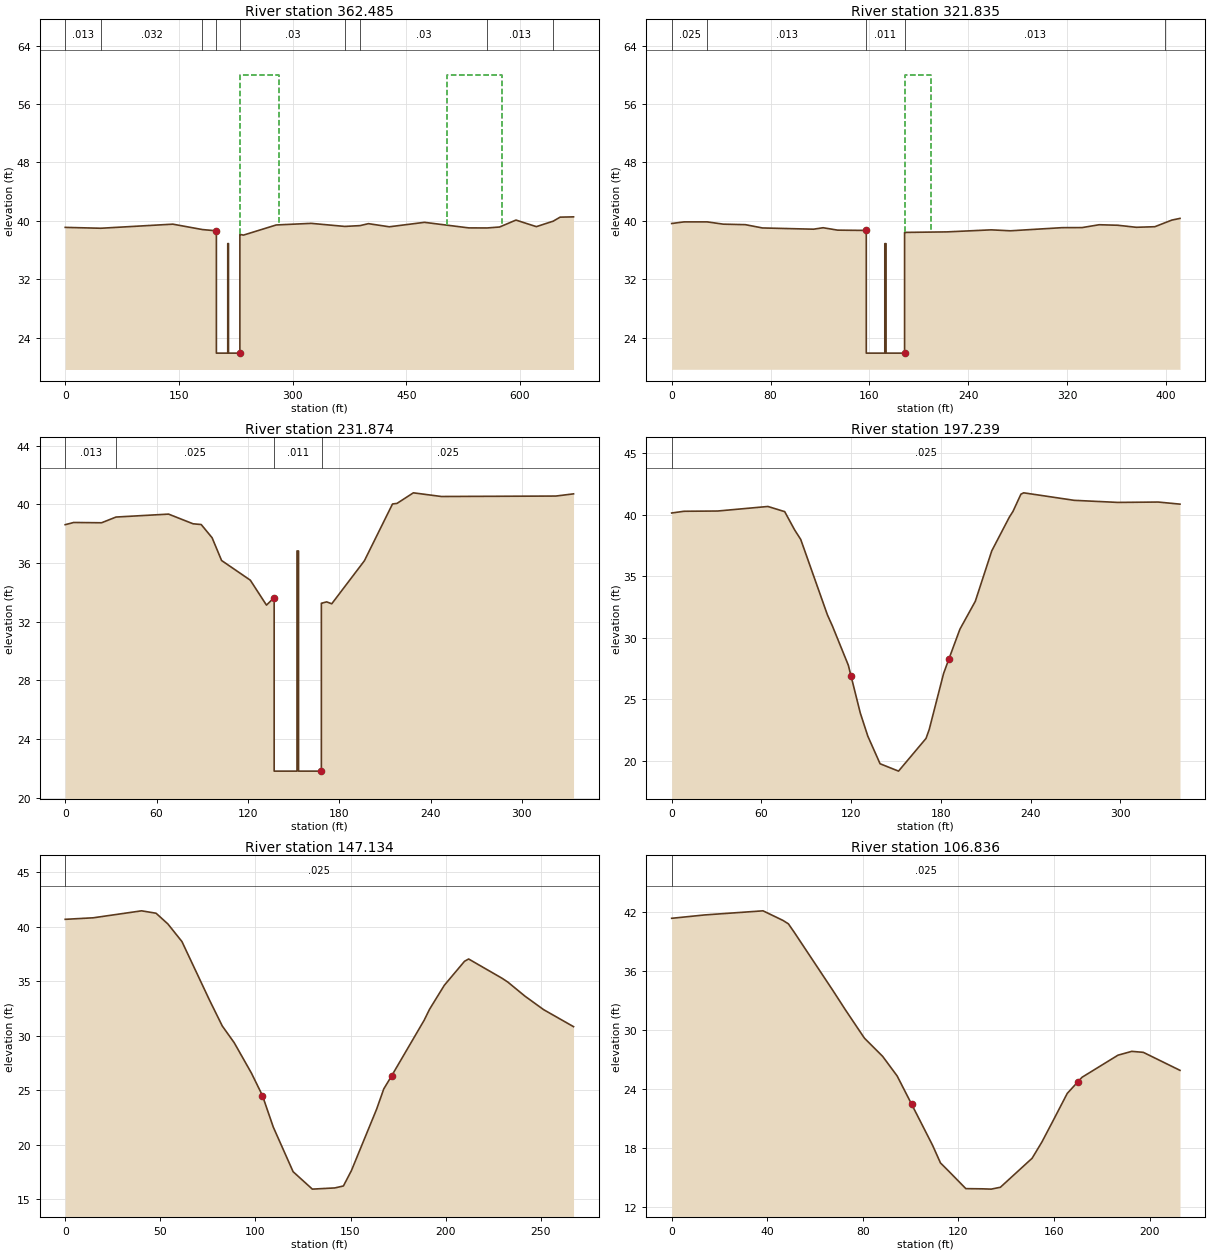
Type RM Length L Ch R = 1 ,362.485 ,49.75,40.65,191.81
XS GIS Cut Line= 5
     3113734.065     13822714.89      3113615.21    13822692.996
     3113346.222    13822517.841     3113271.155    13822445.902
     3113318.072    13822330.175
#Sta/Elev= 30
       0   39.11   46.95   38.99     142   39.55  181.09   38.81  199.36   38.64
  199.46   38.64  199.46   21.89  214.46   21.89  214.46   36.89  215.46   36.89
  215.46   21.89  230.46   21.89  230.46   38.15  230.56   38.15  235.16   38.05
  278.41   39.44  324.48   39.66  368.88   39.24     389   39.35   400.1   39.62
  427.59   39.19  473.96    39.8  532.38   39.04  556.67   39.03   573.1   39.16
  594.72   40.11  621.65   39.21  643.86   39.96  653.02   40.51  670.69   40.55
#Mann= 9 ,-1 , 0
       0    .013       0   46.95    .032       0  181.09    .016       0
  199.36    .011       0  230.56     .03       0  368.88    .016       0
     389     .03       0  556.67    .013       0  643.86    .025       0
#XS Ineff= 2 ,-1
  230.56  281.69      60   503.2  576.79      60
Permanent Ineff=
       F       F
#XS Lid=6
  199.46   38.64   36.89  202.53   38.58   36.89  217.08    38.2   36.89
  221.33   38.24   36.89  224.21   38.27   36.89  230.46   38.15   36.89
Bank Sta=199.46,230.46
XS Rating Curve= 0 ,0
Exp/Cntr=0.3,0.1

Type RM Length L Ch R = 1 ,321.835 ,148.69,89.96,202.21
XS GIS Cut Line= 5
     3113721.554     13822658.59     3113621.465    13822649.207
      3113474.46    13822552.246      3113446.31    13822527.224
     3113443.182    13822430.264
#Sta/Elev= 30
       0   39.63    9.99   39.85   28.79   39.85    41.7   39.54   59.64   39.47
   73.42   39.02  114.77   38.85  122.53   39.05  134.28   38.72  157.46   38.68
  157.46   21.87  172.46   21.87  172.46   36.87  173.46   36.87  173.46   21.87
  188.46   21.87  188.46   38.41  188.56   38.41  222.59   38.48  258.53   38.76
  274.11   38.63   315.9   39.06  332.07   39.07  345.91   39.46  360.92   39.39
  375.93   39.11  390.94   39.19  398.96   39.72  404.76    40.1   411.3   40.33
#Mann= 5 ,-1 , 0
       0    .025       0   28.79    .013       0  157.46    .011       0
  188.56    .013       0  398.96    .025       0
#XS Ineff= 1 ,-1
  188.56  209.76      60
Permanent Ineff=
       F
#XS Lid=6
  157.46   38.68   36.87  165.84   38.63   36.87  168.68   38.65   36.87
  182.54   38.46   36.87  186.65   38.42   36.87  188.46   38.41   36.87
Bank Sta=157.46,188.46
XS Rating Curve= 0 ,0
Exp/Cntr=0.3,0.1

Type RM Length L Ch R = 1 ,231.874 ,33.85,34.63,35.24
XS GIS Cut Line= 2
     3113736.904      13822628.3     3113469.264    13822428.689
#Sta/Elev= 30
       0   38.61    5.61   38.76   23.88   38.74   33.39   39.13   67.89   39.33
   83.99   38.67   89.33   38.62   96.48   37.72  102.71   36.17  121.57   34.83
   132.2   33.13  137.15   33.63  137.25   33.63  137.25   21.82  152.25   21.82
  152.25   36.82  153.25   36.82  153.25   21.82  168.25   21.82  168.25   33.26
  168.35   33.26  171.75   33.35  175.07   33.22  196.51   36.15  214.98   40.02
  217.95   40.06  228.67   40.78  247.02   40.53  322.29   40.56  333.88   40.71
#Mann= 4 ,-1 , 0
       0    .013       0   33.39    .025       0  137.15    .011       0
  168.35    .025       0
#XS Lid=11
   83.99   38.08      32  137.25   38.08      32  137.25   38.08   36.82
  140.13   38.08   36.82  142.92   38.08   36.82  146.66   38.08   36.82
  158.84   38.08   36.82  164.36   38.08   36.82  168.25   38.08   36.82
  168.25   38.08      32  214.98   38.08      32
Bank Sta=137.25,168.25
XS Rating Curve= 0 ,0
Exp/Cntr=0.3,0.1

Type RM Length L Ch R = 1 ,197.239 ,50.11,50.1,50.13
XS GIS Cut Line= 4
     3113757.492    13822598.762     3113687.673    13822564.747
     3113586.525    13822456.438     3113483.586    13822407.207
#Sta/Elev= 30
       0   40.14    8.27   40.28   30.71    40.3   64.37   40.67   75.59   40.25
   82.21   38.77   86.31   37.99  104.18   31.85  107.54   30.94  118.15   27.76
  120.01   26.86  126.16   23.87   131.2   21.99  139.38   19.75  151.72   19.15
  170.11   21.81  172.25   22.54  181.83   27.08  185.28   28.23  192.77   30.69
  203.06   32.96  214.07   37.06  225.86   39.81  228.27   40.27  233.57   41.67
  235.43   41.78  269.18   41.17  298.43      41  325.42   41.03  339.96   40.86
#Mann= 1 ,-1 , 0
       0    .025       0
Bank Sta=120.01,185.28
XS Rating Curve= 0 ,0
Exp/Cntr=0.3,0.1

Type RM Length L Ch R = 1 ,147.134 ,40.37,40.3,40.23
XS GIS Cut Line= 2
     3113766.443    13822575.489     3113583.839    13822380.353
#Sta/Elev= 30
       0   40.68   14.74   40.82   40.14   41.46   47.75   41.24   53.96   40.26
   61.37   38.64   75.91   33.25   82.59   30.89   88.84   29.36   97.87   26.58
  103.69   24.51  109.38   21.62  119.82   17.52  129.93   15.92  141.77   16.03
  146.27   16.21  150.47   17.62  163.73   23.26  167.49   25.12  171.57    26.3
  188.72   31.42  191.56   32.43  199.33   34.63  209.94   36.83   212.1   37.04
  229.59   35.28  232.64   34.93  241.78   33.62  251.54   32.39  267.25   30.83
#Mann= 1 ,-1 , 0
       0    .025       0
Bank Sta=103.69,171.57
XS Rating Curve= 0 ,0
Exp/Cntr=0.3,0.1

Type RM Length L Ch R = 1 ,106.836 ,103.68,106.84,106.14
XS GIS Cut Line= 2
     3113795.087    13822544.159     3113647.393    13822391.094
#Sta/Elev= 29
       0   41.36   13.73    41.7   38.23   42.12   46.61   41.14   48.83    40.8
   51.15   39.99   67.45   34.03   72.75   32.04   80.66   29.18   88.29   27.33
   94.35   25.34   100.4   22.47  109.14   18.31  112.48    16.5  115.95   15.66
  123.09   13.89  129.98   13.87   133.7   13.84  137.55   14.03  150.83   16.98
  154.92   18.63  159.16   20.59  165.53   23.57  169.95   24.74  171.67    25.2
  186.74   27.45  192.52   27.84  197.35   27.74   212.7   25.91
#Mann= 1 ,-1 , 0
       0    .025       0
Bank Sta=100.4,169.95
XS Rating Curve= 0 ,0
Exp/Cntr=0.3,0.1

Chan Stop Cuts=-1
Use User Specified Reach Order=0